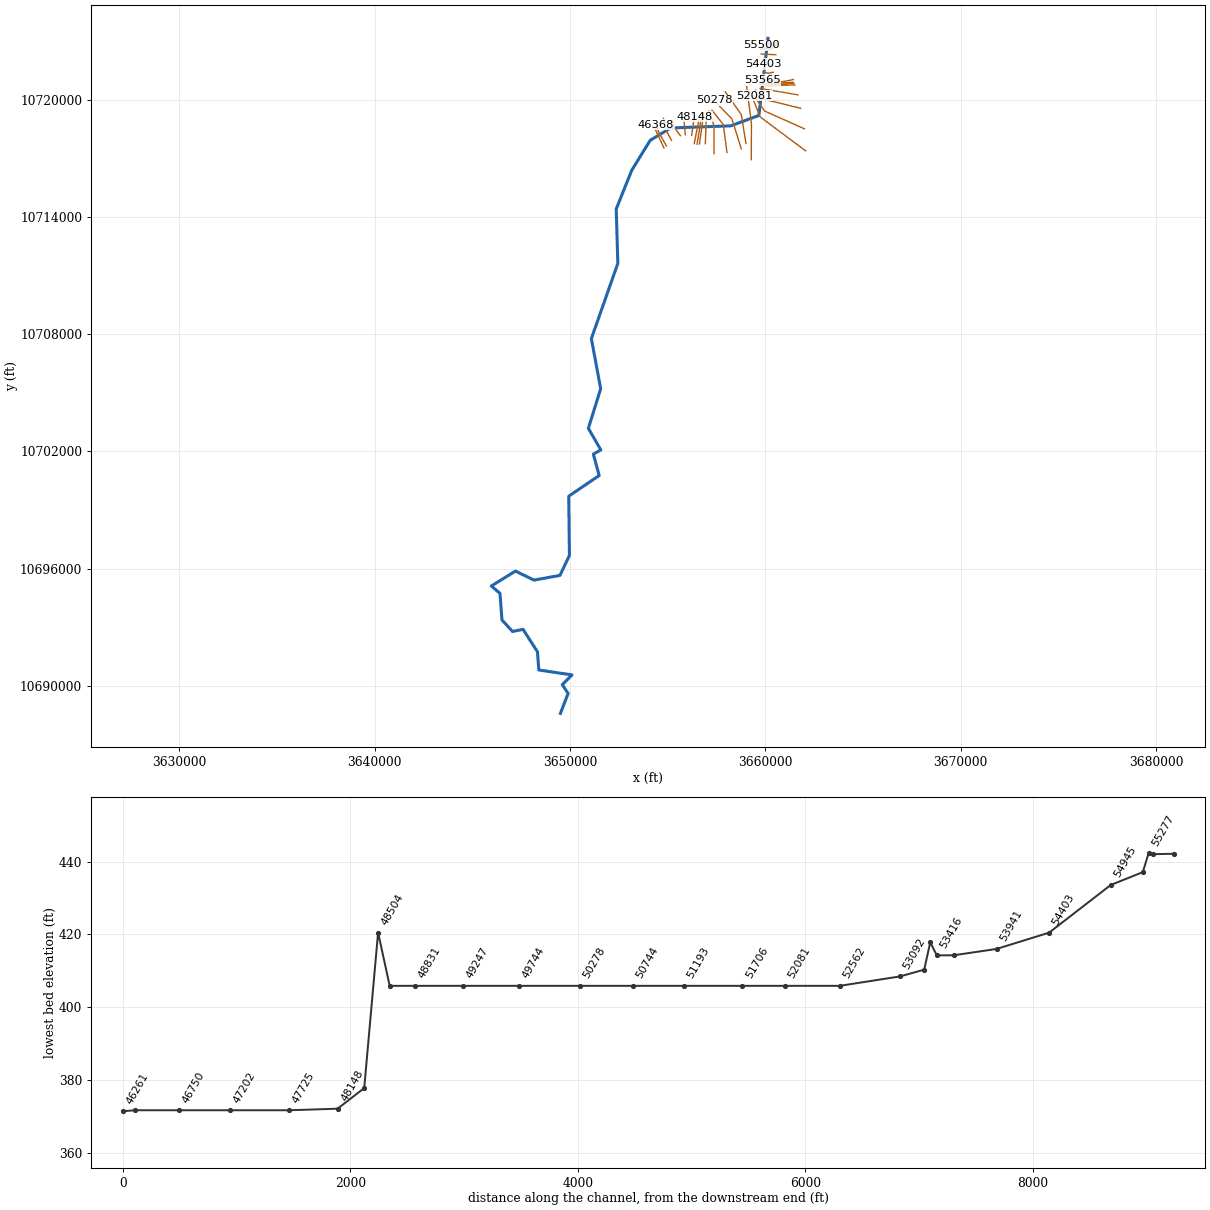
--- MITCHELL BRANCH.prj (project) ---

Proj Title=MITCHELL BRANCH Base Level Engineering
Current Plan=p01
Default Exp/Contr=0.3,0.1
English Units
Geom File=g01
Flow File=f01
Plan File=p01
Y Axis Title=Elevation
X Axis Title(PF)=Main Channel Distance
X Axis Title(XS)=Station
BEGIN DESCRIPTION:
MITCHELL BRANCH
END DESCRIPTION:
DSS Export Rating Curves= 0
DSS Export Rating Curve Sorted= 0
DSS Export Volume Flow Curves= 0
DXF OffsetX= 0
DXF OffsetY= 0
DXF ScaleX= 1
DXF ScaleY= 10

--- MITCHELL BRANCH.p01 (plan) ---

Plan Title=Multiple Run
Short Identifier=Multiple
Geom File=g01
Flow File=f01
Subcritical Flow
K Sum by GR= 0
Std Step Tol= 0.01
Critical Tol= 0.01
Num of Std Step Trials= 20
Max Error Tol= 0.3
Flow Tol Ratio= 0.001
Split Flow NTrial= 30
Split Flow Tol= 0.02
Split Flow Ratio= 0.02
Log Output Level= 0
Friction Slope Method= 1
Unsteady Friction Slope Method= 2
Unsteady Bridges Friction Slope Method= 1
Parabolic Critical Depth
Global Vel Dist=  1 , 1 , 1
Global Log Level= 0
CheckData=True
Encroach Param= -1, 0, 0, 0
BEGIN DESCRIPTION:
Multiple Run
END DESCRIPTION:

--- MITCHELL BRANCH.f01 (steady flow) ---

Flow Title=Multiple
Program Version=4.10
Number of Profiles= 7
Profile Names=10-year,25-year,50-year,1pct_min,100-year,1pct_plu,500-year
River Rch & RM=MITCHELL BRANCH,Reach-1         ,55500
     541     727     879     780    1054    1426    1521
River Rch & RM=MITCHELL BRANCH,Reach-1         ,50744
     961    1336    1653    1497    2025    2739    3052
River Rch & RM=MITCHELL BRANCH,Reach-1         ,42775
    1160    1624    2018    1836    2483    3358    3777
River Rch & RM=MITCHELL BRANCH,Reach-1         ,36149
    1341    1890    2359    2155    2914    3941    4469
River Rch & RM=MITCHELL BRANCH,Reach-1         ,31270
    1412    1990    2483    2267    3065    4145    4696
River Rch & RM=MITCHELL BRANCH,Reach-1         ,25154
    1573    2223    2777    2538    3433    4642    5271
River Rch & RM=MITCHELL BRANCH,Reach-1         ,22947
    1595    2252    2813    2569    3475    4699    5332
River Rch & RM=MITCHELL BRANCH,Reach-1         ,17298
    1922    2726    3415    3127    4229    5719    6519
Boundary for River Rch & Prof#=MITCHELL BRANCH,Reach-1         , 1
Up Type= 0
Dn Type= 3
Dn Slope=0.003
Boundary for River Rch & Prof#=MITCHELL BRANCH,Reach-1         , 2
Up Type= 0
Dn Type= 3
Dn Slope=0.003
Boundary for River Rch & Prof#=MITCHELL BRANCH,Reach-1         , 3
Up Type= 0
Dn Type= 3
Dn Slope=0.003
Boundary for River Rch & Prof#=MITCHELL BRANCH,Reach-1         , 4
Up Type= 0
Dn Type= 3
Dn Slope=0.003
Boundary for River Rch & Prof#=MITCHELL BRANCH,Reach-1         , 5
Up Type= 0
Dn Type= 3
Dn Slope=0.003
Boundary for River Rch & Prof#=MITCHELL BRANCH,Reach-1         , 6
Up Type= 0
Dn Type= 3
Dn Slope=0.003
Boundary for River Rch & Prof#=MITCHELL BRANCH,Reach-1         , 7
Up Type= 0
Dn Type= 3
Dn Slope=0.003
DSS Import GetInterval= 0
DSS Import GetPeak= 0
DSS Import FillOption= 0

--- MITCHELL BRANCH.g01 (geometry) ---

Geom Title=Existing Conditions
Program Version=4.10

River Reach=MITCHELL BRANCH ,Reach-1
Reach XY= 30
      3660132.71     10723144.67       3659665.5       10719198.
      3658227.25       10718665.      3655148.75       10718558.
        3654103.       10717924.      3653159.75       10716395.
        3652363.       10714409.      3652445.75       10711625.
       3651090.5       10707773.       3651567.5       10705206.
       3650936.5       10703183.      3651573.75       10702078.
       3651193.5       10701860.      3651490.25       10700765.
      3649932.75       10699708.        3649967.       10696676.
       3649484.5       10695654.        3648155.       10695412.
        3647204.       10695874.       3645969.5       10695110.
      3646413.25       10694733.      3646514.25       10693373.
      3647055.25       10692781.      3647590.75       10692894.
        3648331.       10691744.      3648399.61     10690810.19
      3650099.61     10690560.19      3649599.61     10690060.19
      3649899.61     10689610.19      3649507.56     10688589.91

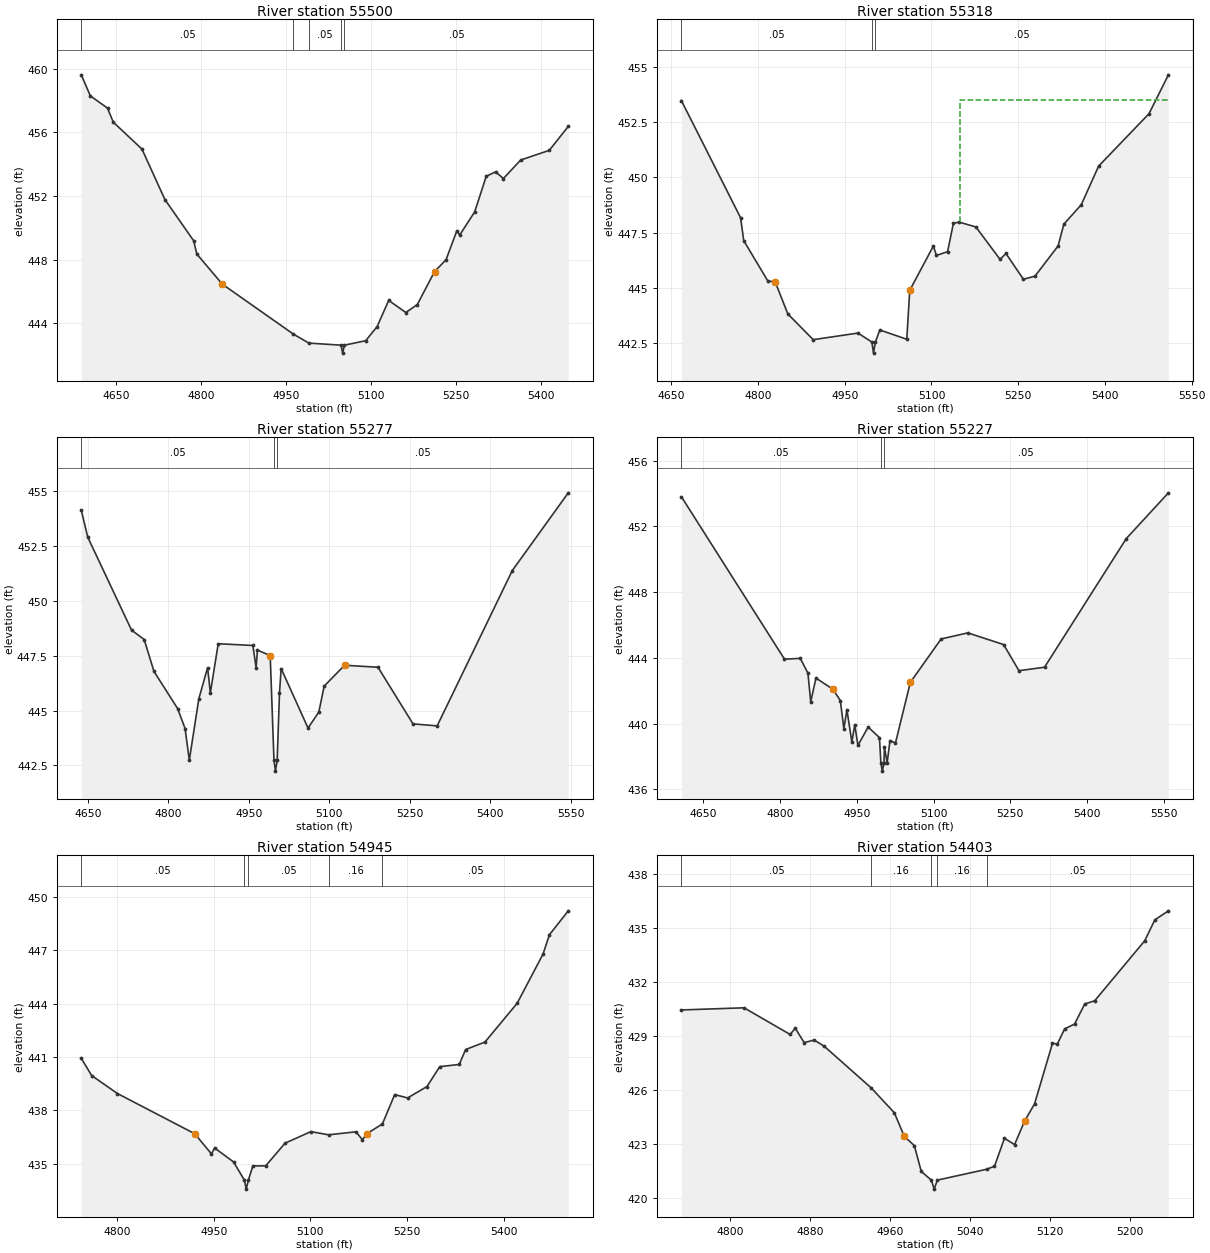
Type RM Length L Ch R = 1 ,55500   ,182,182,182
BEGIN DESCRIPTION:
MITCHELL BRANCH 88.0
END DESCRIPTION:
XS GIS Cut Line= 2
      3660655.41     10722916.17      3659806.53     10722785.97
#Sta/Elev= 30
  4588.9  459.61  4604.9  458.29  4635.2  457.52  4645.3  456.64  4695.9  454.95
  4736.4  451.78    4787   449.2  4792.7  448.36  4837.6  446.47  4963.1  443.33
  4990.2  442.77    5047  442.64  5049.8  442.14    5053  442.64  5090.5  442.92
  5110.7  443.81    5131  445.45  5161.3  444.69  5181.5  445.19  5211.9  447.26
  5232.1     448  5251.2  449.82  5256.2  449.55  5282.7  451.01    5303  453.24
  5319.5  453.52  5333.3   453.1  5363.7  454.26  5414.2  454.87  5447.7  456.37
#Mann= 5 ,-1 , 0
  4588.9     .05       0  4963.1     .07       0  4990.2     .05       0
    5047     .03       0    5053     .05       0
Bank Sta=4837.6,5211.9
XS Rating Curve= 0 ,0
Exp/Cntr=0.3,0.1

Type RM Length L Ch R = 1 ,55318   ,41,41,41
BEGIN DESCRIPTION:
Mapping XS 7042e58d
END DESCRIPTION:
XS GIS Cut Line= 6
      3660548.75     10722845.34      3660347.99     10722759.61
      3660321.95     10722689.08      3660273.12     10722673.89
      3660035.49     10722645.68      3659779.02     10722656.52
#Sta/Elev= 30
  4667.6  453.48  4769.9  448.17  4775.4  447.13  4817.1   445.3  4829.8  445.26
  4851.6  443.81  4895.5  442.64    4973  442.94    4997  442.53  4999.8  442.03
    5003  442.53  5010.7  443.08  5057.3  442.66  5062.5  444.88  5103.4  446.89
  5108.5  446.46  5127.9  446.63    5138  447.92  5148.1  447.97  5176.9  447.75
  5218.7  446.28  5228.8  446.55    5259  445.38    5279  445.52    5319  446.89
    5329  447.88  5359.1  448.76  5389.1  450.51  5476.3  452.89  5509.8  454.65
#Mann= 3 ,-1 , 0
  4667.6     .05       0    4997     .03       0    5003     .05       0
#XS Ineff= 2 , 0
                         5149.58          453.53
Permanent Ineff=
       F       F
Bank Sta=4829.8,5062.5
XS Rating Curve= 0 ,0
Exp/Cntr=0.3,0.1

Type RM Length L Ch R = 1 ,55277   ,50,50,50
BEGIN DESCRIPTION:
Mapping XS f6a2156f
END DESCRIPTION:
XS GIS Cut Line= 6
      3660574.76     10722820.37      3660379.46     10722736.82
      3660357.76     10722666.29      3660320.87     10722642.42
      3660034.61     10722615.19      3659745.18     10722612.24
#Sta/Elev= 30
  4637.8  454.12  4649.9  452.89  4731.5  448.66  4755.1  448.23  4773.3  446.78
  4817.4  445.09  4831.3  444.18  4839.2  442.74    4857  445.54  4873.3  446.95
  4878.4   445.8  4893.1  448.04  4957.7  447.96  4963.7  446.95  4966.2  447.75
    4990   447.5    4997  442.74  4999.8  442.24    5003  442.74  5007.3   445.8
  5010.4  446.91  5060.5   444.2  5080.6  444.93  5090.6  446.11  5128.6  447.06
  5190.9  446.97  5256.2  444.39  5301.2   444.3  5441.2  451.37  5545.6  454.91
#Mann= 3 ,-1 , 0
  4637.8     .05       0    4997     .03       0    5003     .05       0
Bank Sta=4990,5128.6
XS Rating Curve= 0 ,0
Exp/Cntr=0.3,0.1

Type RM Length L Ch R = 1 ,55227   ,282,282,282
BEGIN DESCRIPTION:
Mapping XS 6805d297
END DESCRIPTION:
XS GIS Cut Line= 6
      3660592.17     10722804.11       3660413.1     10722709.69
      3660398.99     10722636.99      3660275.29     10722581.66
       3660173.3     10722564.29      3659737.37     10722561.46
#Sta/Elev= 30
  4606.9   453.8  4808.5  443.92  4839.4  443.97  4854.3  443.07  4859.8  441.33
    4870  442.77  4903.3  442.09  4917.7   441.4  4924.6  439.69  4930.5  440.85
  4940.2  438.89  4945.9  439.92  4952.1  438.68  4972.1  439.79  4994.2  439.15
    4997  437.61  4999.8  437.11    5003  437.61  5003.9  438.58  5009.2  437.61
  5014.8  438.97  5025.5  438.82  5054.6  442.51  5114.8  445.15  5166.9  445.52
    5237  444.81    5267  443.22    5317  443.43    5477  451.26  5559.3  454.04
#Mann= 3 ,-1 , 0
  4606.9     .05       0    4997     .03       0    5003     .05       0
Bank Sta=4903.3,5054.6
XS Rating Curve= 0 ,0
Exp/Cntr=0.3,0.1

Type RM Length L Ch R = 1 ,54945   ,542,542,542
BEGIN DESCRIPTION:
Mapping XS 466afc51
END DESCRIPTION:
XS GIS Cut Line= 2
      3660535.66      10722306.8      3659780.41     10722338.05
#Sta/Elev= 30
  4744.3  440.93  4760.4  439.96  4800.4  438.95  4920.5  436.69  4946.3  435.56
  4951.3  435.89  4980.6  435.11  4997.6  434.08  5000.3  433.58  5003.6  434.08
  5010.6  434.88  5030.6  434.89  5060.6  436.16  5100.7  436.81  5128.3  436.63
  5170.7   436.8  5180.7  436.35  5187.4  436.69  5211.7  437.24  5230.8  438.89
  5250.8   438.7  5280.8  439.34  5300.8  440.46  5330.9  440.58  5340.9  441.42
  5370.9  441.84  5420.9  444.02    5461  446.78    5471  447.87  5500.2  449.21
#Mann= 5 ,-1 , 0
  4744.3     .05       0  4997.6     .03       0  5003.6     .05       0
  5128.3     .16       0  5211.7     .05       0
Bank Sta=4920.5,5187.4
XS Rating Curve= 0 ,0
Exp/Cntr=0.3,0.1

Type RM Length L Ch R = 1 ,54403   ,462,462,462
BEGIN DESCRIPTION:
MITCHELL BRANCH 87.0
END DESCRIPTION:
XS GIS Cut Line= 2
      3660362.11     10721796.87      3659876.01     10721833.76
#Sta/Elev= 30
  4751.2  430.44  4813.9  430.56  4860.1  429.08  4865.1  429.43  4874.1  428.63
  4884.1  428.77  4894.1  428.43  4941.3  426.11  4964.3  424.74  4974.3  423.43
  4984.4  422.91  4991.3  421.48  5001.4     421  5004.2   420.5  5007.4     421
  5056.6   421.6  5064.6  421.77  5074.6  423.32  5084.7  422.97  5094.7  424.27
  5104.7  425.23  5122.6  428.58  5127.6  428.56  5134.8  429.39  5144.8  429.66
  5154.9  430.77  5164.9  430.95    5215  434.28  5225.1  435.44  5238.7  435.94
#Mann= 5 ,-1 , 0
  4751.2     .05       0  4941.3     .16       0  5001.4     .07       0
  5007.4     .16       0  5056.6     .05       0
Bank Sta=4974.3,5094.7
XS Rating Curve= 0 ,0
Exp/Cntr=0.3,0.1

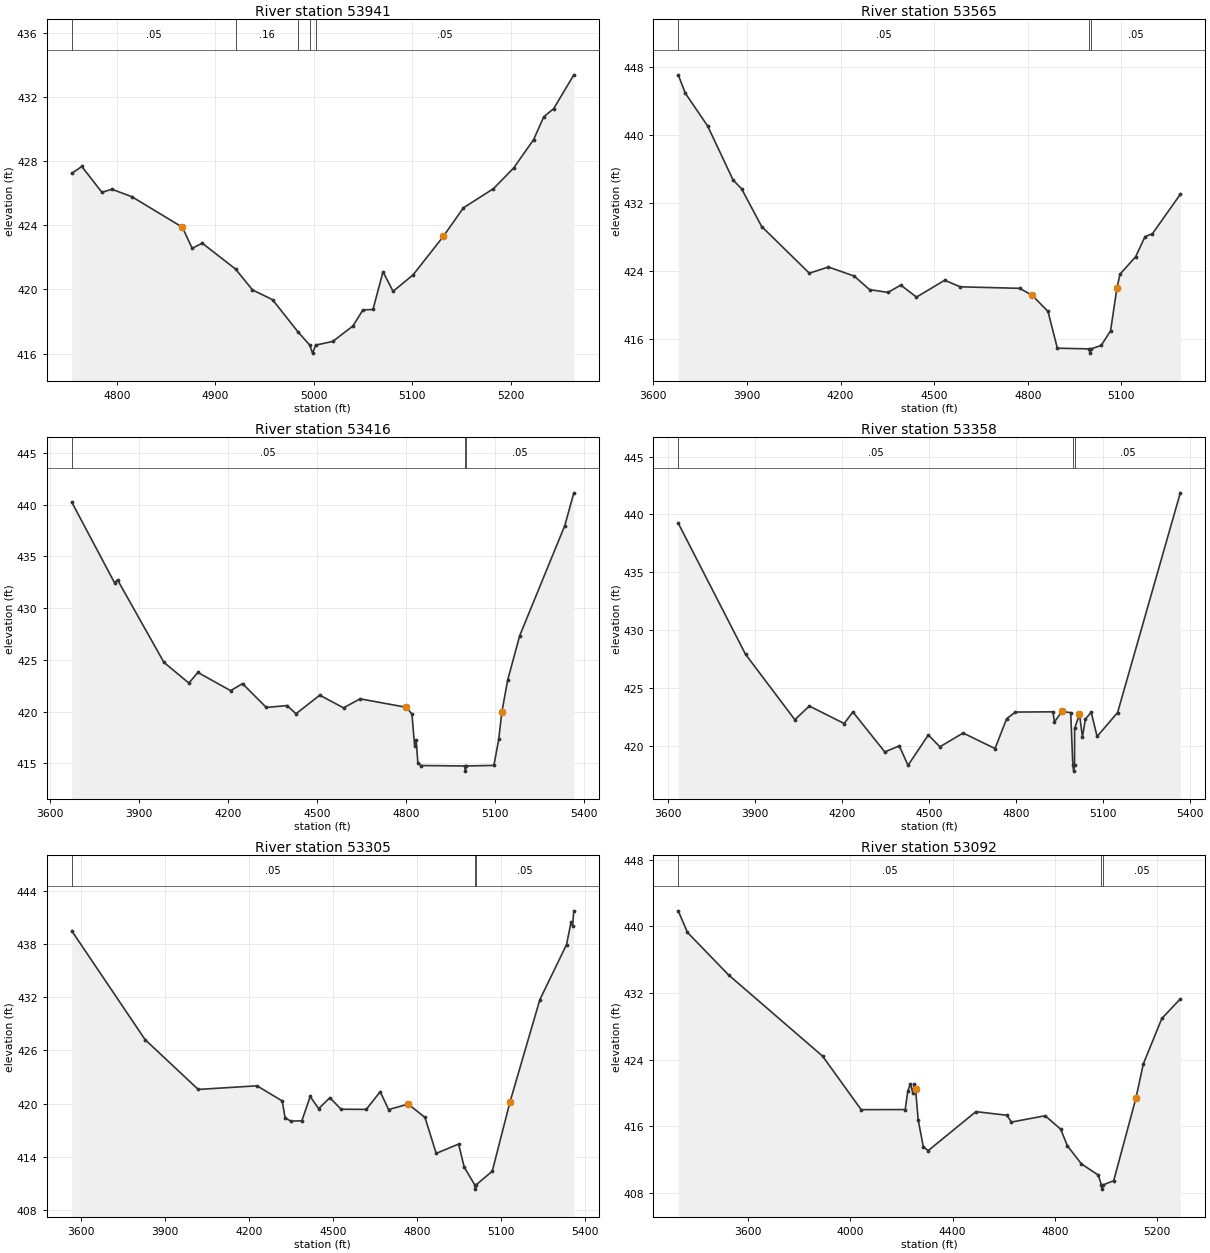
Type RM Length L Ch R = 1 ,53941   ,376,376,376
BEGIN DESCRIPTION:
MITCHELL BRANCH 86.0
END DESCRIPTION:
XS GIS Cut Line= 3
      3660399.58     10721410.18      3660149.61     10721360.19
      3659899.58     10721410.19
#Sta/Elev= 30
  4754.3  427.23  4764.5  427.66  4784.9  426.05  4795.1  426.24  4815.5  425.77
  4866.5  423.88  4876.6  422.56  4886.8  422.88  4920.6  421.27  4937.8  419.97
  4958.2  419.36  4984.1  417.35    4996  416.53  4998.8  416.03    5002  416.53
  5019.4  416.76  5039.8  417.72    5050  418.72  5060.2  418.75  5070.4   421.1
  5080.6  419.88    5101  420.91  5131.6   423.3    5152  425.08  5182.6  426.28
    5203  427.56  5223.4  429.34  5233.6  430.75  5243.8  431.27  5264.2  433.37
#Mann= 5 ,-1 , 0
  4754.3     .05       0  4920.6     .16       0  4984.1     .05       0
    4996    .033       0    5002     .05       0
Bank Sta=4866.5,5131.6
XS Rating Curve= 0 ,0
Exp/Cntr=0.3,0.1

Type RM Length L Ch R = 1 ,53565   ,149,149,149
BEGIN DESCRIPTION:
MITCHELL BRANCH 85.0
END DESCRIPTION:
XS GIS Cut Line= 3
        3661432.     10721034.77      3660878.54      10720925.9
      3659836.91      10721012.7
#Sta/Elev= 30
  3679.8  447.03  3702.6  444.86    3774  441.02  3855.5  434.67  3882.9  433.62
  3947.2  429.19  4100.1   423.7  4161.2  424.43  4243.9  423.36    4293  421.77
  4351.9  421.44  4393.3   422.3  4443.5  420.89  4533.8  422.87    4584   422.1
  4774.6  421.92  4814.8  421.08  4864.9  419.21    4895  414.88    4997   414.8
  4999.8   414.3    5003   414.8  5035.5   415.2  5065.6  416.93  5085.7  421.91
  5095.7  423.58  5145.9  425.64    5176     428  5199.9  428.35  5289.1  432.98
#Mann= 3 ,-1 , 0
  3679.8     .05       0    4997    .033       0    5003     .05       0
Bank Sta=4814.8,5085.7
XS Rating Curve= 0 ,0
Exp/Cntr=0.3,0.1

Type RM Length L Ch R = 1 ,53416   ,58,58,58
BEGIN DESCRIPTION:
Mapping XS c66b3c87
END DESCRIPTION:
XS GIS Cut Line= 4
      3661423.25     10720898.05       3660876.5     10720857.82
       3660227.2     10720823.09      3659739.32     10720894.28
#Sta/Elev= 30
  3673.7  440.23  3817.7  432.45  3827.8  432.73  3984.2  424.76  4068.4  422.76
  4098.5  423.79  4208.8  422.03  4248.9  422.71    4329  420.41  4399.1  420.59
  4429.1   419.8  4509.2  421.59  4589.3  420.37    4645  421.24  4799.6  420.43
  4819.7  419.78  4828.8   416.7  4833.8  417.29  4839.7  415.09  4849.7   414.8
    4997  414.76  4999.8  414.26    5003  414.76  5095.8  414.81  5112.3  417.36
  5122.4  419.93  5142.6  423.09    5183  427.35  5334.6  437.96  5365.2  441.13
#Mann= 3 ,-1 , 0
  3673.7     .05       0    4997    .033       0    5003     .05       0
Bank Sta=4799.6,5122.4
XS Rating Curve= 0 ,0
Exp/Cntr=0.3,0.1

Type RM Length L Ch R = 1 ,53358   ,53,53,53
BEGIN DESCRIPTION:
Mapping XS 9f437348
END DESCRIPTION:
XS GIS Cut Line= 4
      3661451.47     10720830.77      3660803.59     10720797.05
      3660195.95     10720769.27      3659725.48     10720838.71
#Sta/Elev= 30
  3635.3  439.25  3867.5  427.93  4037.7  422.28  4087.8  423.46  4207.9  421.95
    4238  422.95  4348.1   419.5  4398.2  420.02  4428.2  418.34  4498.3  420.96
  4538.3  419.94  4618.4  421.13  4728.5  419.79  4768.5  422.36  4798.6  422.94
  4928.4  422.96  4933.5  422.08  4959.4  422.99  4989.7  422.89    4997  418.34
  4999.8  417.84    5003  418.34  5003.1  421.53    5020  422.75  5030.2  420.78
  5040.3  422.34  5060.5  422.92  5080.7  420.83  5151.5   422.9  5367.9  441.87
#Mann= 3 ,-1 , 0
  3635.3     .05       0    4997     .03       0    5003     .05       0
Bank Sta=4959.4,5020
XS Rating Curve= 0 ,0
Exp/Cntr=0.3,0.1

Type RM Length L Ch R = 1 ,53305   ,213,213,213
BEGIN DESCRIPTION:
Mapping XS 627d983a
END DESCRIPTION:
XS GIS Cut Line= 3
      3661511.44     10720755.67      3660092.15     10720729.63
      3659723.95     10720796.77
#Sta/Elev= 30
    3567  439.47  3828.9  427.21  4018.9  421.59  4228.9     422    4319  420.29
    4329  418.41    4349  418.02    4389  418.05    4419   420.8    4449  419.42
    4489  420.66    4529  419.36    4619  419.34    4669  421.33    4699  419.32
    4769  419.94    4829  418.43    4869  414.38  4949.1  415.43  4969.1  412.83
  5006.4  410.85  5009.2  410.35  5012.4  410.85  5069.3  412.37  5132.8   420.2
  5239.3  431.71  5334.7  437.92    5351  440.49  5356.1  440.05  5360.8  441.73
#Mann= 3 ,-1 , 0
    3567     .05       0  5006.4     .03       0  5012.4     .05       0
Bank Sta=4769,5132.8
XS Rating Curve= 0 ,0
Exp/Cntr=0.3,0.1

Type RM Length L Ch R = 1 ,53092   ,530,530,530
BEGIN DESCRIPTION:
MITCHELL BRANCH 84.0
END DESCRIPTION:
XS GIS Cut Line= 2
      3661665.23     10720251.75      3659728.33     10720578.68
#Sta/Elev= 30
  3326.3  441.86  3362.4  439.27  3523.4  434.17  3891.3  424.43  4041.9  418.02
  4214.3  418.03  4224.5  420.25  4234.6  421.11  4243.9  420.05    4249  421.06
  4254.9  420.48    4265  416.79  4285.3  413.56  4304.4  413.11  4490.9  417.78
  4611.8  417.35  4630.1  416.53  4761.9  417.29  4822.8  415.67  4848.6  413.69
  4903.9  411.51  4969.5  410.18  4982.1  408.99  4984.8  408.49  4988.1  408.99
    5030   409.5  5116.9  419.39  5145.8   423.5  5218.3  428.95  5290.6   431.3
#Mann= 3 ,-1 , 0
  3326.3     .05       0  4982.1     .03       0  4988.1     .05       0
Bank Sta=4254.9,5116.9
XS Rating Curve= 0 ,0
Exp/Cntr=0.3,0.1

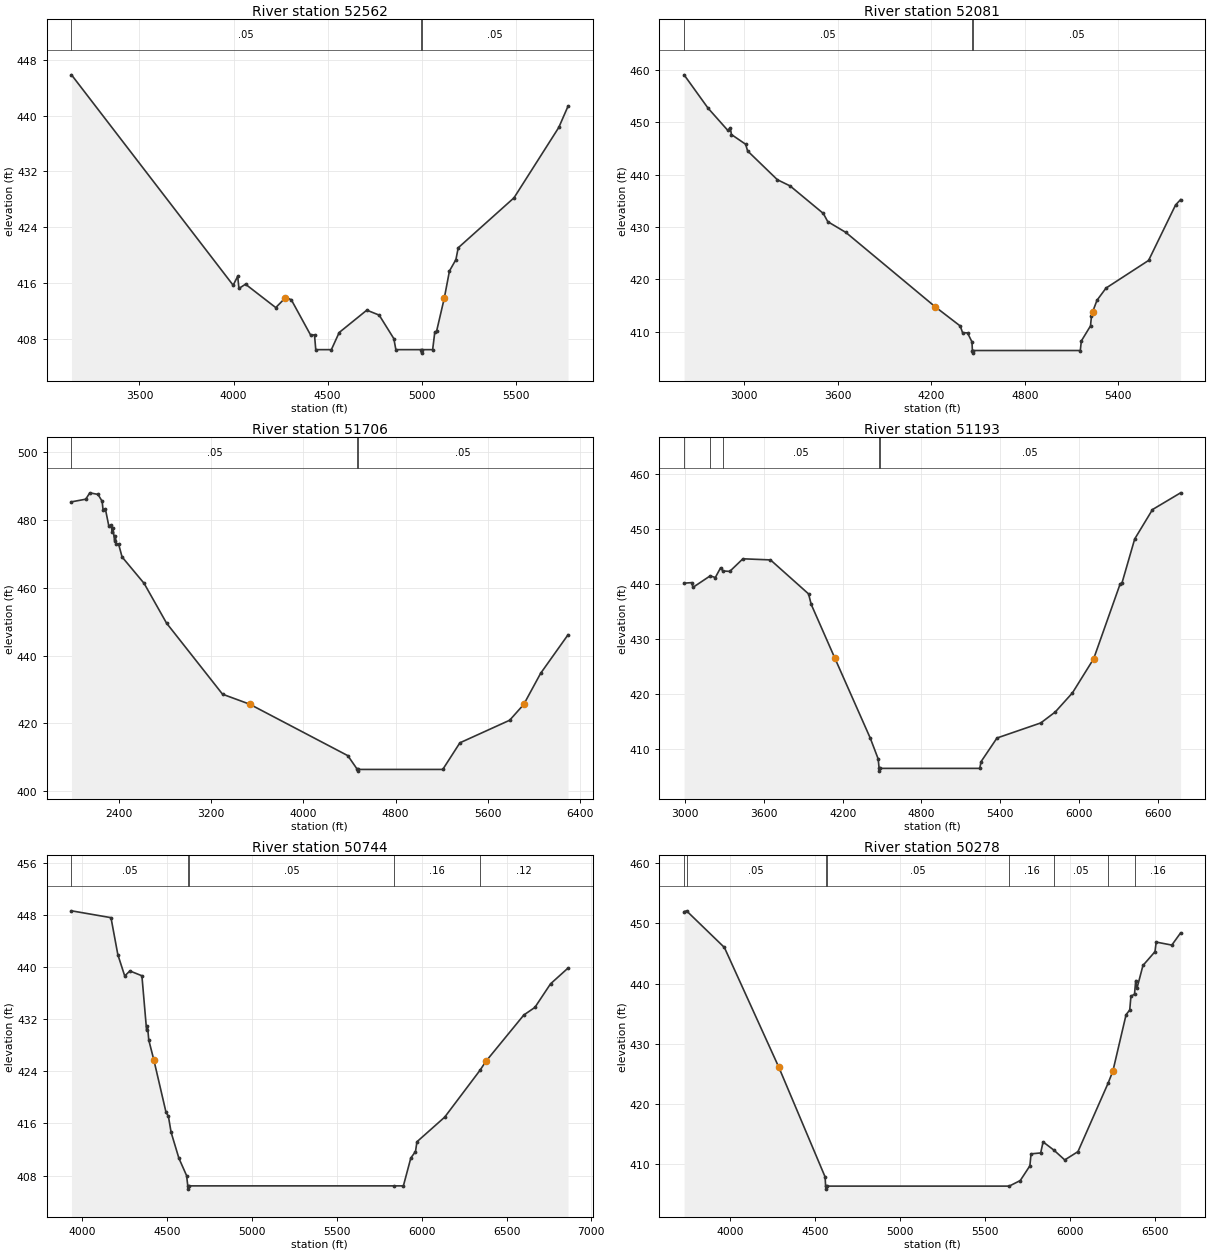
Type RM Length L Ch R = 1 ,52562   ,481,481,481
BEGIN DESCRIPTION:
MITCHELL BRANCH 83.0
END DESCRIPTION:
XS GIS Cut Line= 3
      3661804.12     10719564.25      3659658.92     10720092.57
      3659496.22     10720491.13
#Sta/Elev= 30
  3138.6  445.88  3998.1  415.66  4022.3  416.95  4028.9   415.2  4063.8  415.81
  4224.6  412.45  4276.4  413.87    4307  413.59    4410   408.5  4430.6  408.53
  4437.3  406.41  4520.3  406.41  4561.8  408.87  4708.7  412.08  4774.5  411.37
  4852.4  407.99  4863.2  406.41    4997  406.41  4999.8  405.91    5003  406.41
  5058.8  406.41  5070.2  408.94  5079.4  409.02  5120.6   413.8  5148.1  417.71
  5182.4  419.34  5194.7  421.04  5491.4  428.22  5729.3  438.32  5778.4  441.37
#Mann= 3 ,-1 , 0
  3138.6     .05       0    4997    .033       0    5003     .05       0
Bank Sta=4276.4,5120.6
XS Rating Curve= 0 ,0
Exp/Cntr=0.3,0.1

Type RM Length L Ch R = 1 ,52081   ,375,375,375
BEGIN DESCRIPTION:
MITCHELL BRANCH 82.0
END DESCRIPTION:
XS GIS Cut Line= 3
      3662000.35     10718510.41       3659958.4     10719424.16
        3659417.     10720203.12
#Sta/Elev= 30
  2613.2  459.05  2766.9  452.69  2893.8  448.44  2909.8  448.91    2917  447.65
  3008.4  445.79  3020.7  444.52  3211.8  439.02  3293.3  437.84  3506.6  432.58
  3535.3  431.01  3651.2  428.96  4224.5  414.76  4385.5  411.08  4399.8  409.83
  4431.9  409.77  4460.5  408.05    4463  406.41  4465.8  405.91    4469  406.41
  5155.4  406.41  5162.1  408.23  5220.9  411.11    5227  412.99  5235.1  413.84
  5262.7  416.01  5320.4  418.33  5593.6  423.61  5766.5  434.19  5798.9  435.23
#Mann= 3 ,-1 , 0
  2613.2     .05       0    4463    .033       0    4469     .05       0
Bank Sta=4224.5,5235.1
XS Rating Curve= 0 ,0
Exp/Cntr=0.3,0.1

Type RM Length L Ch R = 1 ,51706   ,513,513,513
BEGIN DESCRIPTION:
MITCHELL BRANCH 81.0
END DESCRIPTION:
XS GIS Cut Line= 3
      3662052.44     10717390.61      3659724.02     10719129.02
      3659214.25     10720431.32
#Sta/Elev= 30
  1989.8  485.34  2113.2  486.12  2148.6     488  2219.5  487.53  2255.4  485.51
  2263.3  483.05  2284.1  483.16  2313.3  478.23  2334.1  478.53  2342.5  476.33
  2348.7   477.7  2363.3  473.91  2369.6  475.25  2377.9  473.05  2398.8  472.81
    2428   469.1  2619.7  461.27  2813.6  449.58  3299.3   428.6  3534.9  425.65
  4385.5  410.47  4467.9  406.41  4470.7  405.91  4473.9  406.41  5208.3  406.41
  5356.8  414.26  5788.2  420.92  5910.3  425.58  6056.6  434.75  6294.1  446.12
#Mann= 3 ,-1 , 0
  1989.8     .05       0  4467.9    .033       0  4473.9     .05       0
Bank Sta=3534.9,5910.3
XS Rating Curve= 0 ,0
Exp/Cntr=0.3,0.1

Type RM Length L Ch R = 1 ,51193   ,449,449,449
BEGIN DESCRIPTION:
MITCHELL BRANCH 80.0
END DESCRIPTION:
XS GIS Cut Line= 3
      3659276.37     10716932.25      3659285.66      10718781.8
      3659036.96     10720696.55
#Sta/Elev= 30
  2992.4  440.07  3050.3  440.17  3060.3  439.31  3191.4   441.4  3230.3   441.1
  3270.3  442.86  3289.5  442.29  3340.3  442.21  3440.3   444.5  3650.3   444.3
  3940.3  438.12  3960.3  436.22  4140.3  426.45  4410.4  411.89  4470.4  408.12
  4477.4  406.41  4480.1  405.91  4483.4  406.41  5243.7  406.41  5253.8  407.64
  5374.8  411.93  5708.4  414.67  5818.5  416.66  5949.6  420.14  6110.9  426.33
  6312.6  439.94  6326.5   440.1  6423.5  448.11  6558.9  453.45  6772.8  456.49
#Mann= 5 ,-1 , 0
  2992.4     .05       0  3191.4     .08       0  3289.5     .05       0
  4477.4    .033       0  4483.4     .05       0
Bank Sta=4140.3,6110.9
XS Rating Curve= 0 ,0
Exp/Cntr=0.3,0.1

Type RM Length L Ch R = 1 ,50744   ,466,466,466
BEGIN DESCRIPTION:
MITCHELL BRANCH 79.0
END DESCRIPTION:
XS GIS Cut Line= 3
      3659005.54     10717760.39      3658765.95      10719244.8
      3657943.01     10720406.29
#Sta/Elev= 30
  3935.5  448.68  4168.3  447.63  4208.8  441.94  4249.3  438.67  4279.7  439.44
  4350.6   438.7  4378.3  430.31  4383.4  431.02  4391.1  428.82  4421.5  425.71
  4492.4  417.76  4506.9  417.09  4522.8  414.64  4568.7  410.66    4614  407.99
  4621.1  406.41  4623.8  405.91  4627.1  406.41  5835.8  406.41  5892.1  406.41
    5936   410.7  5963.5  411.69  5972.1  413.19  6135.8  416.98  6343.3  424.16
  6379.4  425.58  6602.1  432.67  6667.4  433.84  6759.6  437.46  6862.6  439.88
#Mann= 5 ,-1 , 0
  3935.5     .05       0  4621.1    .033       0  4627.1     .05       0
  5835.8     .16       0  6343.3     .12       0
Bank Sta=4421.5,6379.4
XS Rating Curve= 0 ,0
Exp/Cntr=0.3,0.1

Type RM Length L Ch R = 1 ,50278   ,534,534,534
BEGIN DESCRIPTION:
MITCHELL BRANCH 78.0
END DESCRIPTION:
XS GIS Cut Line= 3
      3658765.94     10717489.62      3658281.58     10719026.05
      3657370.12     10719963.54
#Sta/Elev= 30
  3729.9  451.91  3744.3  452.05  3966.8  445.98  4286.2  426.16  4558.8  407.94
  4561.9  406.41  4564.7  405.91  4567.9  406.41  5640.9  406.41  5705.9  407.33
  5762.5  409.77  5769.5  411.76    5826  411.91  5840.2  413.74  5904.4  412.36
  5967.5  410.75  6045.2  412.13  6222.1  423.46  6250.4  425.48  6328.1  434.84
  6349.5  435.61  6356.4  437.87  6377.6  438.24  6384.7  440.49  6391.9   439.2
  6427.2  442.99  6497.9  445.28  6504.9  446.87  6596.9  446.37  6648.4  448.39
#Mann= 8 ,-1 , 0
  3729.9     .08       0  3744.3     .05       0  4561.9    .033       0
  4567.9     .05       0  5640.9     .16       0  5904.4     .05       0
  6222.1      .1       0  6377.6     .16       0
Bank Sta=4286.2,6250.4
XS Rating Curve= 0 ,0
Exp/Cntr=0.3,0.1

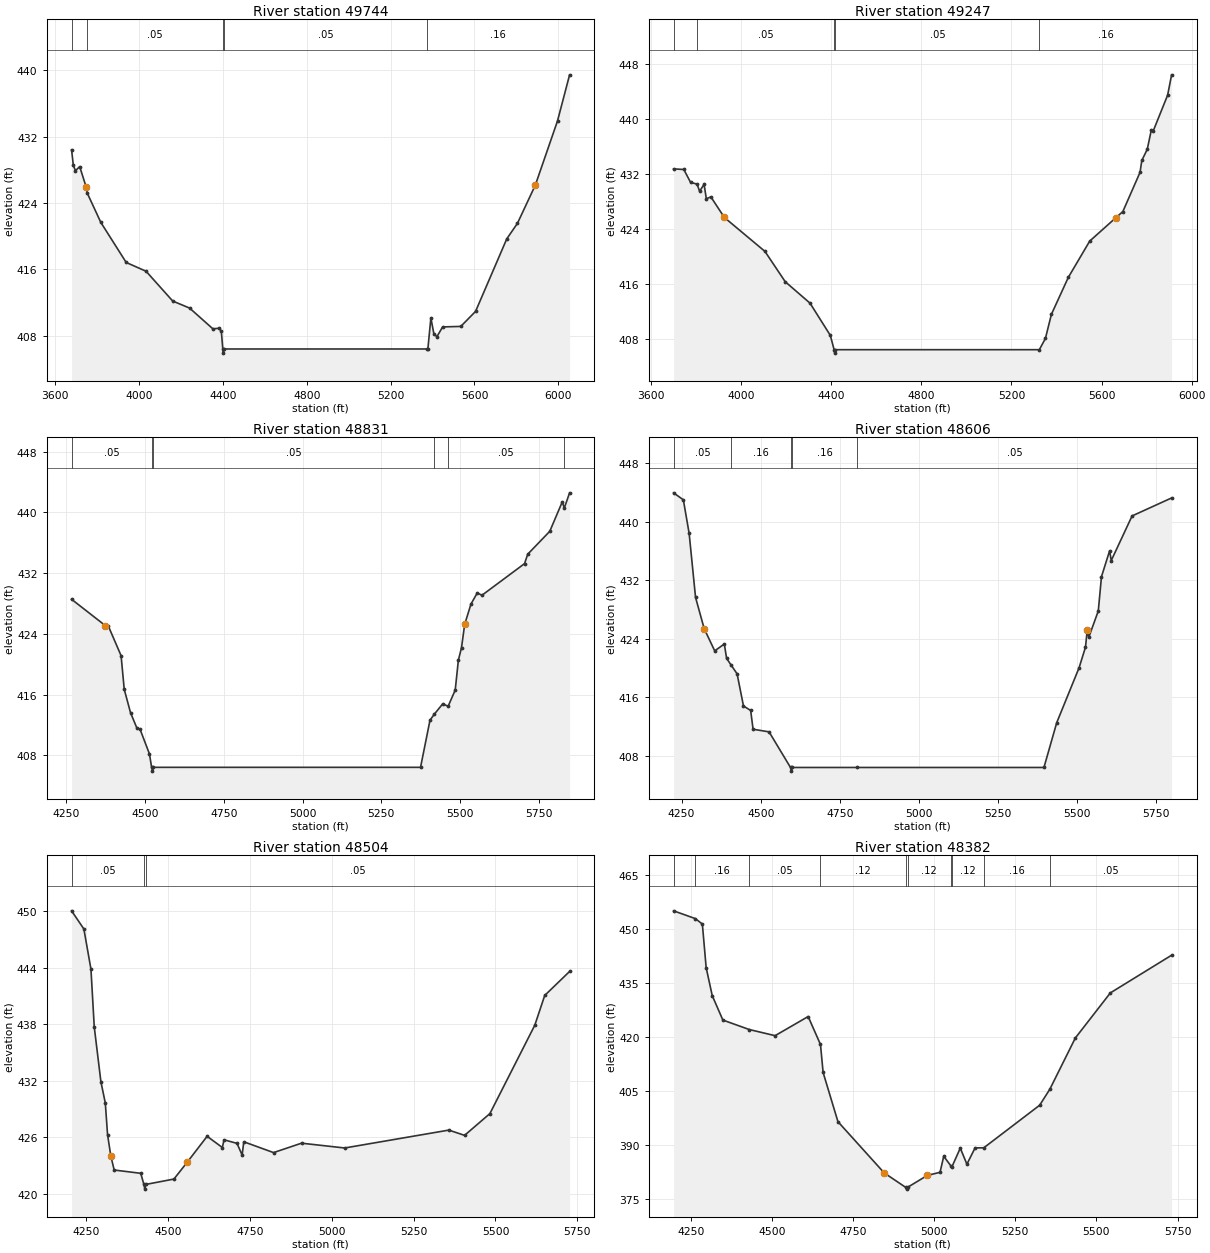
Type RM Length L Ch R = 1 ,49744   ,497,497,497
BEGIN DESCRIPTION:
MITCHELL BRANCH 77.0
END DESCRIPTION:
XS GIS Cut Line= 3
      3658031.32     10717301.77      3657840.34      10718738.4
      3657264.81     10719465.39
#Sta/Elev= 30
  3677.3  430.43  3685.8  428.54  3695.9  427.91  3716.1  428.39  3746.3  425.99
  3752.7  425.17  3816.9  421.67    3938  416.84  4032.8  415.78  4159.9  412.19
  4240.6  411.34  4351.6  408.84  4381.9  408.91    4392  408.53    4399  406.41
  4401.8  405.91    4405  406.41  5373.6  406.41  5377.5  406.41  5391.9  410.15
  5406.4   408.2  5420.8   407.9    5448  409.07  5534.6  409.13  5605.1  410.94
  5754.1  419.69  5804.8  421.55  5890.4  426.17  5996.1   433.9  6053.8  439.46
#Mann= 5 ,-1 , 0
  3677.3     .08       0  3752.7     .05       0    4399    .033       0
    4405     .05       0  5373.6     .16       0
Bank Sta=3746.3,5890.4
XS Rating Curve= 0 ,0
Exp/Cntr=0.3,0.1

Type RM Length L Ch R = 1 ,49247   ,416,416,416
BEGIN DESCRIPTION:
MITCHELL BRANCH 76.0
END DESCRIPTION:
XS GIS Cut Line= 3
      3657370.12      10717244.8      3657364.91     10718666.67
      3657120.37      10719415.9
#Sta/Elev= 30
    3701  432.71  3746.4  432.62  3776.4  430.75  3805.3  430.49  3816.4  429.46
  3836.4  430.46  3846.4  428.36  3866.4  428.64  3926.4  425.64  4106.4  420.71
  4196.4   416.3  4306.4  413.18  4396.4   408.5  4413.4  406.41  4416.1  405.91
  4419.4  406.41  5324.1  406.41  5351.1  408.05  5377.7  411.56  5452.7  416.93
  5547.7  422.21  5663.1  425.59  5694.6   426.5    5771  432.21  5778.8  433.93
  5802.9  435.55  5820.8  438.33  5829.5  438.23  5893.3  443.43    5911  446.39
#Mann= 5 ,-1 , 0
    3701     .16       0  3805.3     .05       0  4413.4    .033       0
  4419.4     .05       0  5324.1     .16       0
Bank Sta=3926.4,5663.1
XS Rating Curve= 0 ,0
Exp/Cntr=0.3,0.1

Type RM Length L Ch R = 1 ,48831   ,225,225,225
BEGIN DESCRIPTION:
MITCHELL BRANCH 75.0
END DESCRIPTION:
XS GIS Cut Line= 2
      3656924.54     10717753.11      3656985.31     10719333.04
#Sta/Elev= 30
  4266.8  428.56    4374  425.09    4384  424.98    4424  421.13    4434  416.69
    4454  413.61    4474   411.6    4484  411.45  4514.1  408.17  4520.9  406.41
  4523.6  405.91  4526.9  406.41  5374.7  406.41  5404.7  412.62  5418.7  413.43
  5444.8  414.76  5462.4  414.47  5484.8  416.59  5494.8  420.53  5504.8  422.19
  5514.8  425.25  5534.8  427.93  5554.8   429.4  5569.7  429.09  5704.9  433.26
    5715   434.5    5785  437.52  5824.8  441.41    5831  440.57  5847.9  442.59
#Mann= 6 ,-1 , 0
  4266.8     .05       0  4520.9    .033       0  4526.9     .05       0
  5418.7     .16       0  5462.4     .05       0    5831     .16       0
Bank Sta=4374,5514.8
XS Rating Curve= 0 ,0
Exp/Cntr=0.3,0.1

Type RM Length L Ch R = 1 ,48606   ,102,102,102
BEGIN DESCRIPTION:
Mapping XS 3770a1f0
END DESCRIPTION:
XS GIS Cut Line= 2
      3656620.72     10717731.44      3656842.08     10719289.59
#Sta/Elev= 30
  4224.6  443.98  4255.5  443.02  4273.8  438.43    4294  429.68  4321.3   425.4
  4354.6  422.36  4384.9   423.3  4392.2  421.33  4407.2  420.37  4425.3  419.22
  4445.5  414.82  4468.2  414.21  4475.8  411.64  4526.4  411.28  4594.1  406.41
  4596.8  405.91  4600.1  406.41  4804.5  406.41    5395  406.41  5435.4  412.54
  5506.1  420.06  5526.3  422.87  5531.7  425.16  5536.7  424.22  5566.7  427.82
  5576.8  432.51  5602.6  436.06  5607.6  434.71  5673.5  440.82  5798.4  443.28
#Mann= 5 ,-1 , 0
  4224.6     .05       0  4407.2     .16       0  4594.1    .033       0
  4600.1     .16       0  4804.5     .05       0
Bank Sta=4321.3,5531.7
XS Rating Curve= 0 ,0
Exp/Cntr=0.3,0.1

Type RM Length L Ch R = 1 ,48504   ,122,122,122
BEGIN DESCRIPTION:
MITCHELL BRANCH 74.0
END DESCRIPTION:
XS GIS Cut Line= 3
      3656497.73     10717731.86      3656625.66     10718489.03
      3656727.72     10719235.48
#Sta/Elev= 30
  4205.1  450.07  4242.7  448.14  4264.3  443.88  4274.4  437.74  4294.7  431.92
  4308.2  429.65    4315   426.3  4325.1  424.01  4335.3  422.54  4416.4  422.19
    4426  421.01  4428.8  420.51    4432  421.01  4517.8  421.58  4558.4  423.37
  4619.2  426.12  4665.7  424.93  4670.8  425.75  4710.5  425.37  4726.1  424.13
  4731.2  425.54  4822.1  424.39  4907.5  425.39  5039.4  424.88  5357.7  426.78
  5405.6  426.22  5482.9  428.53  5620.1  437.92  5650.4  441.08  5726.4  443.63
#Mann= 3 ,-1 , 0
  4205.1     .05       0    4426     .04       0    4432     .05       0
Bank Sta=4325.1,4558.4
XS Rating Curve= 0 ,0
Exp/Cntr=0.3,0.1

Type RM Length L Ch R = 1 ,48382   ,234,234,234
BEGIN DESCRIPTION:
Mapping XS 6670fead
END DESCRIPTION:
XS GIS Cut Line= 2
      3656355.97     10717753.18      3656651.11     10719259.23
#Sta/Elev= 30
  4197.1  455.08  4264.2  452.92  4285.8  451.41  4297.5  439.31  4316.3  431.53
    4349  424.77  4430.1  422.15  4509.9  420.44  4611.8  425.75  4649.8  417.99
  4657.9  410.23  4703.6  396.58  4846.2  382.36  4912.2  378.36    4915  377.86
  4918.2  378.36  4978.7  381.65  5018.2  382.53  5029.6  386.98  5052.2  384.24
  5054.7  384.02  5080.6  389.24    5101  384.78  5126.2   389.3  5153.1  389.33
  5325.2  401.14  5356.5  405.57  5435.1  419.79  5543.1  432.31  5731.8  442.77
#Mann= 10 ,-1 , 0
  4197.1     .05       0  4264.2     .16       0  4430.1     .05       0
  4649.8     .12       0  4912.2     .07       0  4918.2     .12       0
  5052.2     .16       0  5054.7     .12       0  5153.1     .16       0
  5356.5     .05       0
Bank Sta=4846.2,4978.7
XS Rating Curve= 0 ,0
Exp/Cntr=0.3,0.1

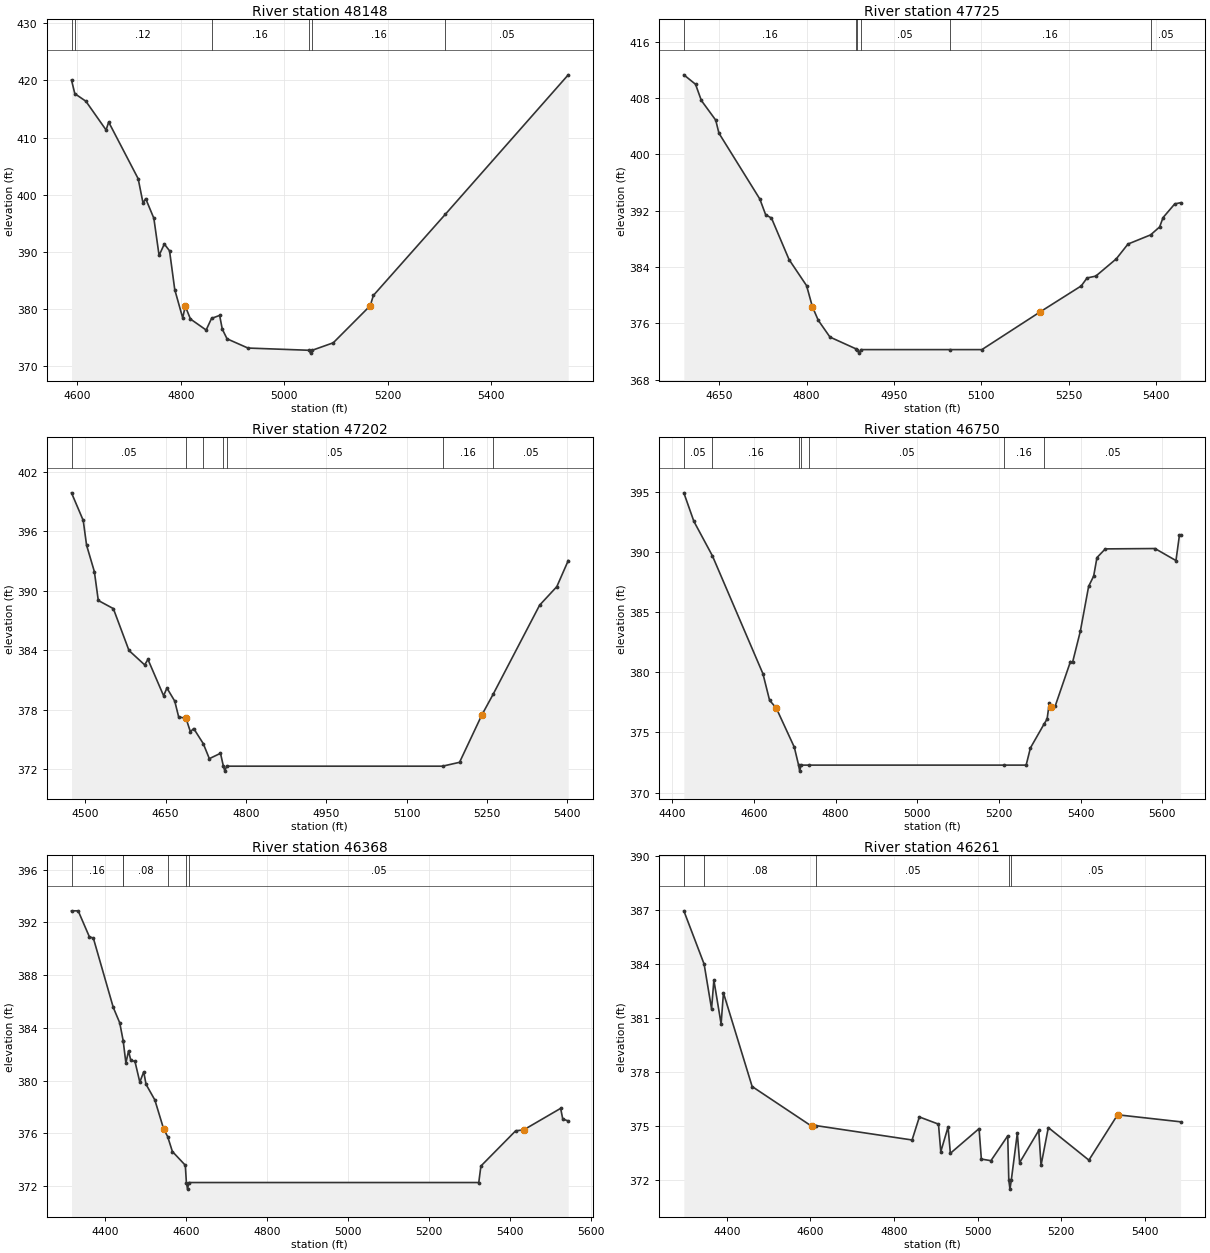
Type RM Length L Ch R = 1 ,48148   ,423,423,423
BEGIN DESCRIPTION:
MITCHELL BRANCH 73.0
END DESCRIPTION:
XS GIS Cut Line= 2
      3656224.87     10718182.61      3656357.68     10719133.08
#Sta/Elev= 30
  4588.9  420.07  4595.3  417.69  4616.7  416.36  4655.7  411.32  4660.7  412.71
  4717.7  402.78  4727.1  398.51  4732.2  399.29    4748  395.85  4758.1  389.33
  4768.2  391.33  4778.3  390.15  4788.4  383.33  4803.7  378.39  4808.7  380.44
  4818.7  378.19    4849  376.26  4859.5   378.3  4875.1  378.82  4880.2  376.42
  4889.4  374.72  4929.8   373.1  5047.9  372.71  5050.7  372.21  5053.9  372.71
  5094.6  374.02  5166.1  380.53  5172.1  382.32  5310.9  396.52  5548.6  420.99
#Mann= 6 ,-1 , 0
  4588.9     .16       0  4595.3     .12       0  4859.5     .16       0
  5047.9     .07       0  5053.9     .16       0  5310.9     .05       0
Bank Sta=4808.7,5166.1
XS Rating Curve= 0 ,0
Exp/Cntr=0.3,0.1

Type RM Length L Ch R = 1 ,47725   ,523,523,523
BEGIN DESCRIPTION:
MITCHELL BRANCH 72.0
END DESCRIPTION:
XS GIS Cut Line= 2
      3655899.61     10718210.19      3655821.23     10719060.18
#Sta/Elev= 30
  4588.9  411.28    4609  409.94    4619  407.64  4643.7  404.85  4649.2     403
  4719.5  393.65  4729.5  391.42  4739.5  390.95  4769.7  385.06  4799.8  381.36
  4809.8  378.37  4819.9  376.44    4840  374.06  4884.6  372.39  4887.2  372.28
  4889.9  371.78  4893.2  372.28  5045.5  372.28  5101.1  372.28  5201.5  377.65
  5271.8  381.32  5281.8  382.45  5296.8  382.71    5332  385.16  5352.1  387.26
  5390.9  388.56  5406.5  389.69  5412.4  391.02  5432.5  392.96  5442.5  393.13
#Mann= 6 ,-1 , 0
  4588.9     .16       0  4884.6     .05       0  4887.2    .033       0
  4893.2     .05       0  5045.5     .16       0  5390.9     .05       0
Bank Sta=4809.8,5201.5
XS Rating Curve= 0 ,0
Exp/Cntr=0.3,0.1

Type RM Length L Ch R = 1 ,47202   ,452,452,452
BEGIN DESCRIPTION:
MITCHELL BRANCH 71.0
END DESCRIPTION:
XS GIS Cut Line= 3
      3655649.62     10718160.18      3655349.61     10718560.19
      3655199.61     10718960.17
#Sta/Elev= 30
  4474.5  399.88  4496.4  397.09  4502.6   394.6  4517.2  391.92  4524.5  389.01
  4552.6  388.19  4581.8  383.96    4611  382.51  4617.2  383.06  4646.4  379.39
  4652.6  380.17  4667.2  378.85  4674.5  377.26  4687.5  377.11  4688.1  377.13
  4696.4  375.76  4702.6  376.08  4720.4  374.56  4731.8  373.04  4752.6  373.58
    4758  372.28  4760.7  371.78    4764  372.28  5167.1  372.28  5198.8  372.67
  5240.6  377.47  5261.5  379.54  5348.3  388.54  5380.4  390.41  5401.7  393.04
#Mann= 7 ,-1 , 0
  4474.5     .05       0  4687.5     .16       0  4720.4     .05       0
    4758    .033       0    4764     .05       0  5167.1     .16       0
  5261.5     .05       0
Bank Sta=4688.1,5240.6
XS Rating Curve= 0 ,0
Exp/Cntr=0.3,0.1

Type RM Length L Ch R = 1 ,46750   ,382,382,382
BEGIN DESCRIPTION:
MITCHELL BRANCH 70.0
END DESCRIPTION:
XS GIS Cut Line= 3
      3655191.53     10717918.43      3654892.05     10718491.36
      3654783.54     10719051.26
#Sta/Elev= 30
  4428.2  394.91  4452.8  392.54  4498.1  389.68    4622  379.87  4638.2  377.67
  4654.6  377.02  4698.8  373.77  4709.3  372.28    4712  371.78  4715.3  372.28
    4735  372.28  5212.1  372.28  5266.7  372.28  5277.2  373.71  5311.2  375.73
    5318   376.1  5323.5  377.46  5328.6  377.08  5338.3  377.23  5375.3  380.89
  5380.4  380.82  5399.4   383.4  5419.8  387.14  5432.1  387.99  5440.2  389.53
  5460.6  390.25  5582.3  390.28  5633.7  389.28  5642.2  391.39    5645  391.39
#Mann= 7 ,-1 , 0
  4428.2     .05       0  4498.1     .16       0  4709.3    .033       0
  4715.3     .16       0    4735     .05       0  5212.1     .16       0
  5311.2     .05       0
Bank Sta=4654.6,5328.6
XS Rating Curve= 0 ,0
Exp/Cntr=0.3,0.1

Type RM Length L Ch R = 1 ,46368   ,107,107,107
BEGIN DESCRIPTION:
MITCHELL BRANCH 69.0
END DESCRIPTION:
XS GIS Cut Line= 3
      3654933.89     10717632.95      3654556.28      10718305.7
      3654398.33     10718733.49
#Sta/Elev= 30
  4316.1  392.87  4332.6  392.87    4360  390.92  4370.2  390.79  4419.3  385.55
  4435.3  384.38  4443.7  383.04  4443.8  383.02  4450.5  381.34    4457  382.25
  4462.7  381.54  4472.9  381.46  4484.9  379.89  4494.6  380.67  4500.3  379.72
    4522  378.54  4543.7  376.35  4553.7  375.76  4565.4  374.63  4597.3  373.59
    4600  372.28  4602.8  371.78    4606  372.28  5322.5  372.28  5327.8  373.53
  5413.7   376.2  5433.5  376.27  5524.8   377.9  5530.1  377.09  5543.6  376.95
#Mann= 6 ,-1 , 0
  4316.1     .16       0  4443.7     .05       0  4443.8     .08       0
  4553.7     .05       0    4600    .033       0    4606     .05       0
Bank Sta=4543.7,5433.5
XS Rating Curve= 0 ,0
Exp/Cntr=0.3,0.1

Type RM Length L Ch R = 1 ,46261   ,89,89,89
BEGIN DESCRIPTION:
Mapping XS ac89bf19
END DESCRIPTION:
XS GIS Cut Line= 3
      3654803.69     10717537.44      3654326.24     10718561.78
      3654309.84     10718616.84
#Sta/Elev= 30
  4297.5  386.97    4346  384.01  4363.8  381.52  4369.3  383.12  4386.6  380.69
  4392.2  382.41  4460.8  377.21  4603.5     375  4613.1  375.04  4843.2  374.24
  4860.6  375.52  4906.3  375.12  4911.8  373.59  4929.2  374.96  4934.7   373.5
  5003.3  374.87  5008.8  373.18  5031.7  373.09  5071.9  374.47  5074.4  372.01
  5077.2  371.51  5080.4  372.01  5094.8  374.62  5100.3  372.98    5146  374.77
  5151.5  372.83  5168.9  374.93  5265.9  373.12  5334.5  375.64  5485.1  375.25
#Mann= 5 ,-1 , 0
  4297.5     .16       0    4346     .08       0  4613.1     .05       0
  5074.4     .03       0  5080.4     .05       0
Bank Sta=4603.5,5334.5
XS Rating Curve= 0 ,0
Exp/Cntr=0.3,0.1