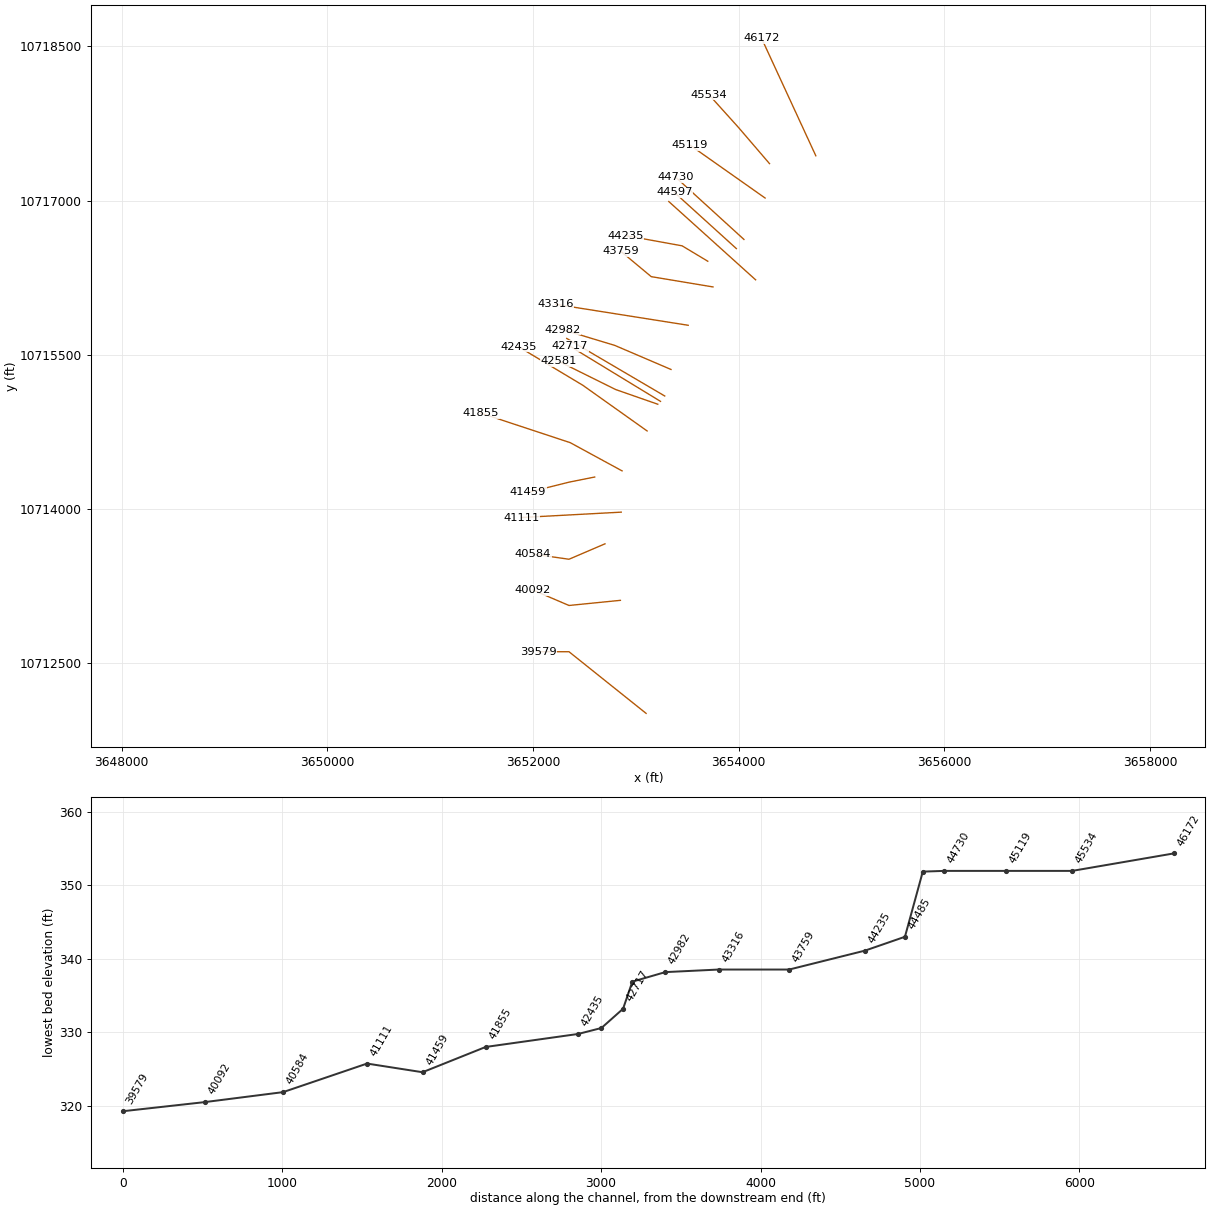
HEC-RAS study MITCHELL BRANCH.prj: MITCHELL BRANCH Base Level Engineering

--- MITCHELL BRANCH.g01 (geometry) --- (continued)

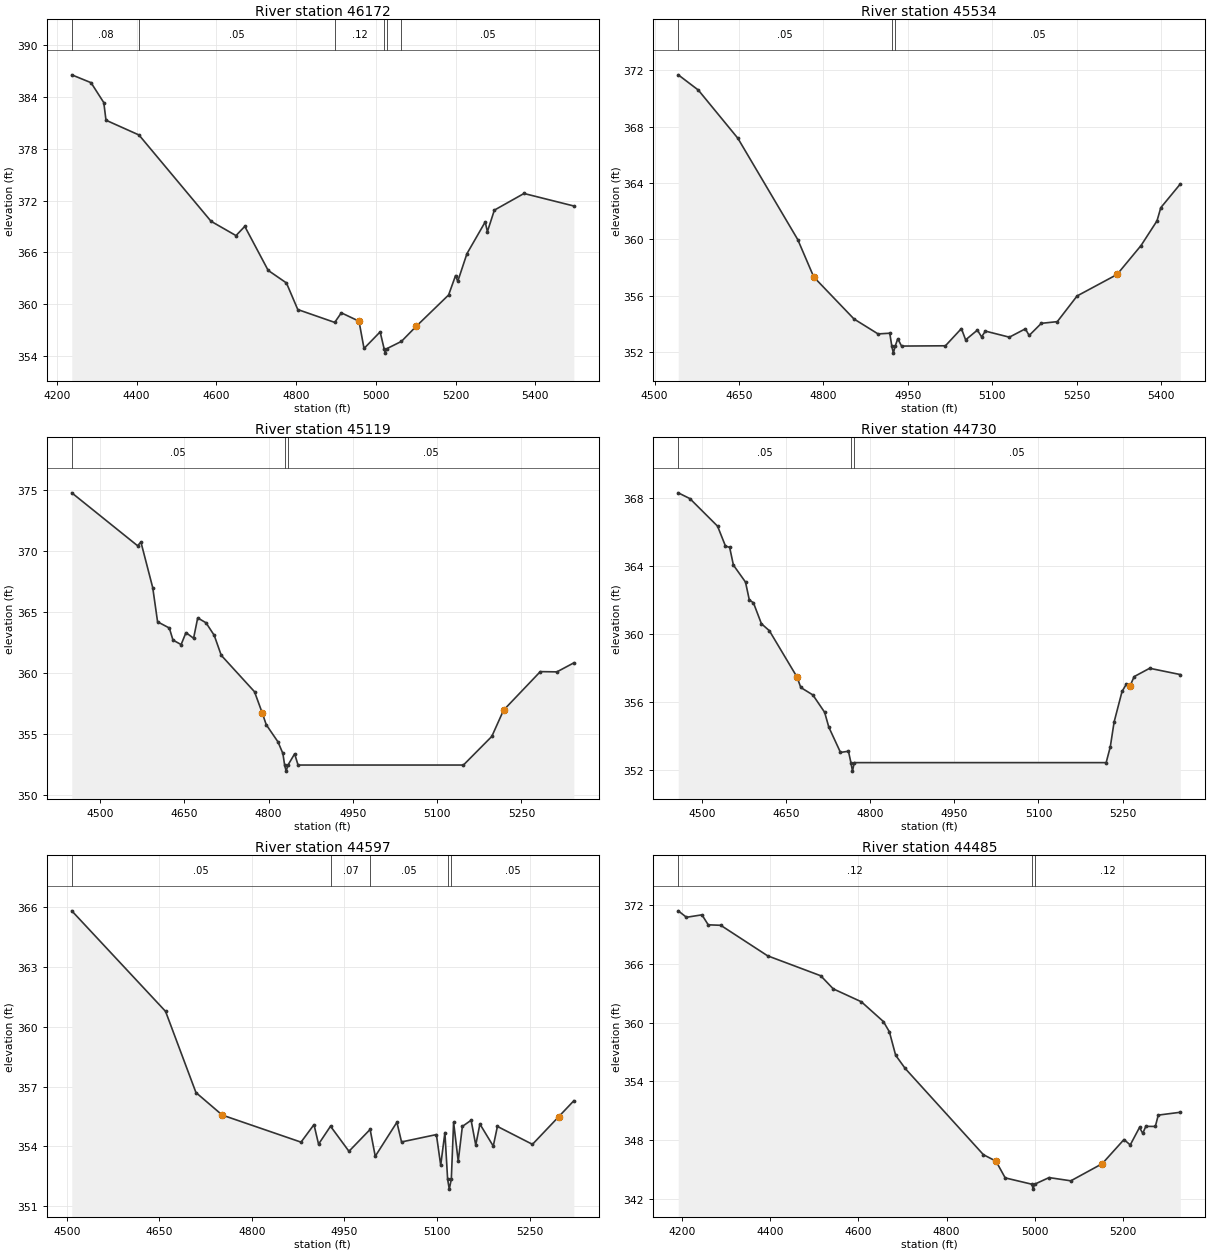
Type RM Length L Ch R = 1 ,46172   ,638,638,638
BEGIN DESCRIPTION:
MITCHELL BRANCH 68.0
END DESCRIPTION:
XS GIS Cut Line= 2
      3654750.07      10717436.3      3654222.58     10718579.36
#Sta/Elev= 30
  4237.6  386.58  4285.9  385.67  4317.9  383.36  4323.4  381.32  4406.1  379.61
  4586.8  369.61  4649.4  367.95  4671.4  369.02    4730  363.92  4775.9  362.46
  4804.3  359.38  4896.9  357.89  4913.5     359  4957.8  358.03  4970.4  354.87
  5010.8  356.79  5020.8  354.83  5023.6  354.33  5026.8  354.83  5064.2  355.69
  5100.9  357.42  5182.5  361.07  5199.9  363.32  5205.4  362.64  5228.4  365.85
  5274.2  369.53  5279.8  368.41  5297.2   370.9  5371.5  372.83  5496.5  371.38
#Mann= 6 ,-1 , 0
  4237.6     .08       0  4406.1     .05       0  4896.9     .12       0
  5020.8     .07       0  5026.8     .12       0  5064.2     .05       0
Bank Sta=4957.8,5100.9
XS Rating Curve= 0 ,0
Exp/Cntr=0.3,0.1

Type RM Length L Ch R = 1 ,45534   ,415,415,415
BEGIN DESCRIPTION:
MITCHELL BRANCH 67.0
END DESCRIPTION:
XS GIS Cut Line= 3
      3654299.63     10717360.17      3653999.61     10717710.19
      3653710.97     10718030.53
#Sta/Elev= 30
    4542  371.66  4577.7  370.58  4647.9  367.17  4754.4  359.99  4782.9  357.34
  4854.3  354.37  4897.1  353.31  4917.9  353.36  4921.5  352.45  4924.3  351.95
  4927.5  352.45  4932.2  352.97  4938.8  352.45  5016.8  352.47  5045.2  353.69
  5052.7  352.89  5073.6  353.58  5081.1   353.1  5087.8  353.51  5130.4  353.08
  5158.8  353.67  5165.6   353.2  5187.2  354.06  5215.6  354.18  5250.8     356
  5321.8  357.52  5364.4  359.57  5392.8  361.32  5399.5  362.25  5434.2  363.93
#Mann= 3 ,-1 , 0
    4542     .05       0  4921.5    .033       0  4927.5     .05       0
Bank Sta=4782.9,5321.8
XS Rating Curve= 0 ,0
Exp/Cntr=0.3,0.1

Type RM Length L Ch R = 1 ,45119   ,389,389,389
BEGIN DESCRIPTION:
MITCHELL BRANCH 66.0
END DESCRIPTION:
XS GIS Cut Line= 2
      3654256.79     10717025.33      3653526.48     10717540.09
#Sta/Elev= 30
  4449.8   374.8  4566.8  370.46  4572.9  370.75  4593.9  367.01  4602.5  364.21
  4623.4   363.7  4629.9  362.71  4644.4  362.34    4653  363.32  4666.6  362.86
  4673.9  364.53  4688.7  364.13  4703.3   363.1  4715.8  361.46    4775  358.47
  4788.9  356.71  4795.9  355.76  4816.8  354.35  4825.5   353.4  4828.6  352.45
  4831.3  351.95  4834.6  352.45  4846.4  353.37  4852.5  352.45  5146.8  352.45
  5197.3   354.8  5218.3  356.96  5283.6  360.12  5313.2   360.1  5343.3  360.84
#Mann= 3 ,-1 , 0
  4449.8     .05       0  4828.6    .033       0  4834.6     .05       0
Bank Sta=4788.9,5218.3
XS Rating Curve= 0 ,0
Exp/Cntr=0.3,0.1

Type RM Length L Ch R = 1 ,44730   ,133,133,133
BEGIN DESCRIPTION:
Mapping XS 9d66f430
END DESCRIPTION:
XS GIS Cut Line= 2
      3654051.17     10716622.22      3653388.95     10717226.36
#Sta/Elev= 30
  4456.8  368.32  4477.6  367.98    4527  366.36  4541.1  365.19  4548.6  365.11
  4555.3  364.07  4576.9  363.07  4583.7  362.02  4591.1  361.85  4605.3  360.62
  4619.5  360.21  4668.8  357.49  4675.6  356.87  4697.2  356.43  4718.2  355.41
  4725.6  354.54  4746.5  353.05  4760.7  353.12  4765.1  352.45  4767.9  351.95
  4771.1  352.45  5220.8  352.45  5228.2  353.38    5235  354.84  5249.2  356.64
  5256.6  357.05  5263.4  356.96  5270.8  357.51  5298.5     358  5353.2  357.63
#Mann= 3 ,-1 , 0
  4456.8     .05       0  4765.1    .033       0  4771.1     .05       0
Bank Sta=4668.8,5263.4
XS Rating Curve= 0 ,0
Exp/Cntr=0.3,0.1

Type RM Length L Ch R = 1 ,44597   ,112,112,112
BEGIN DESCRIPTION:
MITCHELL BRANCH 65.0
END DESCRIPTION:
XS GIS Cut Line= 2
      3653977.37     10716533.26      3653374.59     10717080.01
#Sta/Elev= 30
    4508  365.83    4660  360.78  4709.3   356.7  4751.9  355.57  4879.6  354.21
  4900.6  355.09    4908  354.11  4927.4  355.01  4957.3  353.75  4991.6  354.85
  4999.9   353.5    5035  355.21  5042.5  354.22    5099  354.59    5106  353.05
  5112.8  354.69  5117.2  352.35  5119.9  351.85  5123.2  352.35  5126.9  355.21
  5134.4  353.25  5141.1     355  5155.3  355.31  5162.8  354.06  5169.5  355.12
  5191.2  354.01  5197.9     355  5254.7   354.1  5297.3  355.49  5321.8  356.29
#Mann= 5 ,-1 , 0
    4508     .05       0  4927.4     .07       0  4991.6     .05       0
  5117.2     .03       0  5123.2     .05       0
Bank Sta=4751.9,5297.3
XS Rating Curve= 0 ,0
Exp/Cntr=0.3,0.1

Type RM Length L Ch R = 1 ,44485   ,250,250,250
BEGIN DESCRIPTION:
Mapping XS 69e2512d
END DESCRIPTION:
XS GIS Cut Line= 2
      3654164.55     10716229.29      3653320.32     10716991.05
#Sta/Elev= 30
  4192.2  371.44  4210.8  370.78  4245.9  371.03  4260.1  370.01  4288.5  369.96
  4394.6  366.84  4514.9   364.8  4543.3  363.46  4606.9  362.14  4656.8  360.12
  4670.4  359.07  4684.6  356.67  4706.2  355.32  4883.4   346.5  4911.8  345.84
  4932.7  344.13  4993.2  343.48    4996  342.98  4999.2  343.48  5032.1  344.16
  5081.4  343.83  5152.4  345.58  5201.7  348.05  5215.9   347.5  5236.9  349.29
  5244.3  348.68  5251.1   349.4  5272.7  349.39  5279.4  350.55  5329.3  350.84
#Mann= 3 ,-1 , 0
  4192.2     .12       0  4993.2     .03       0  4999.2     .12       0
Bank Sta=4911.8,5152.4
XS Rating Curve= 0 ,0
Exp/Cntr=0.3,0.1

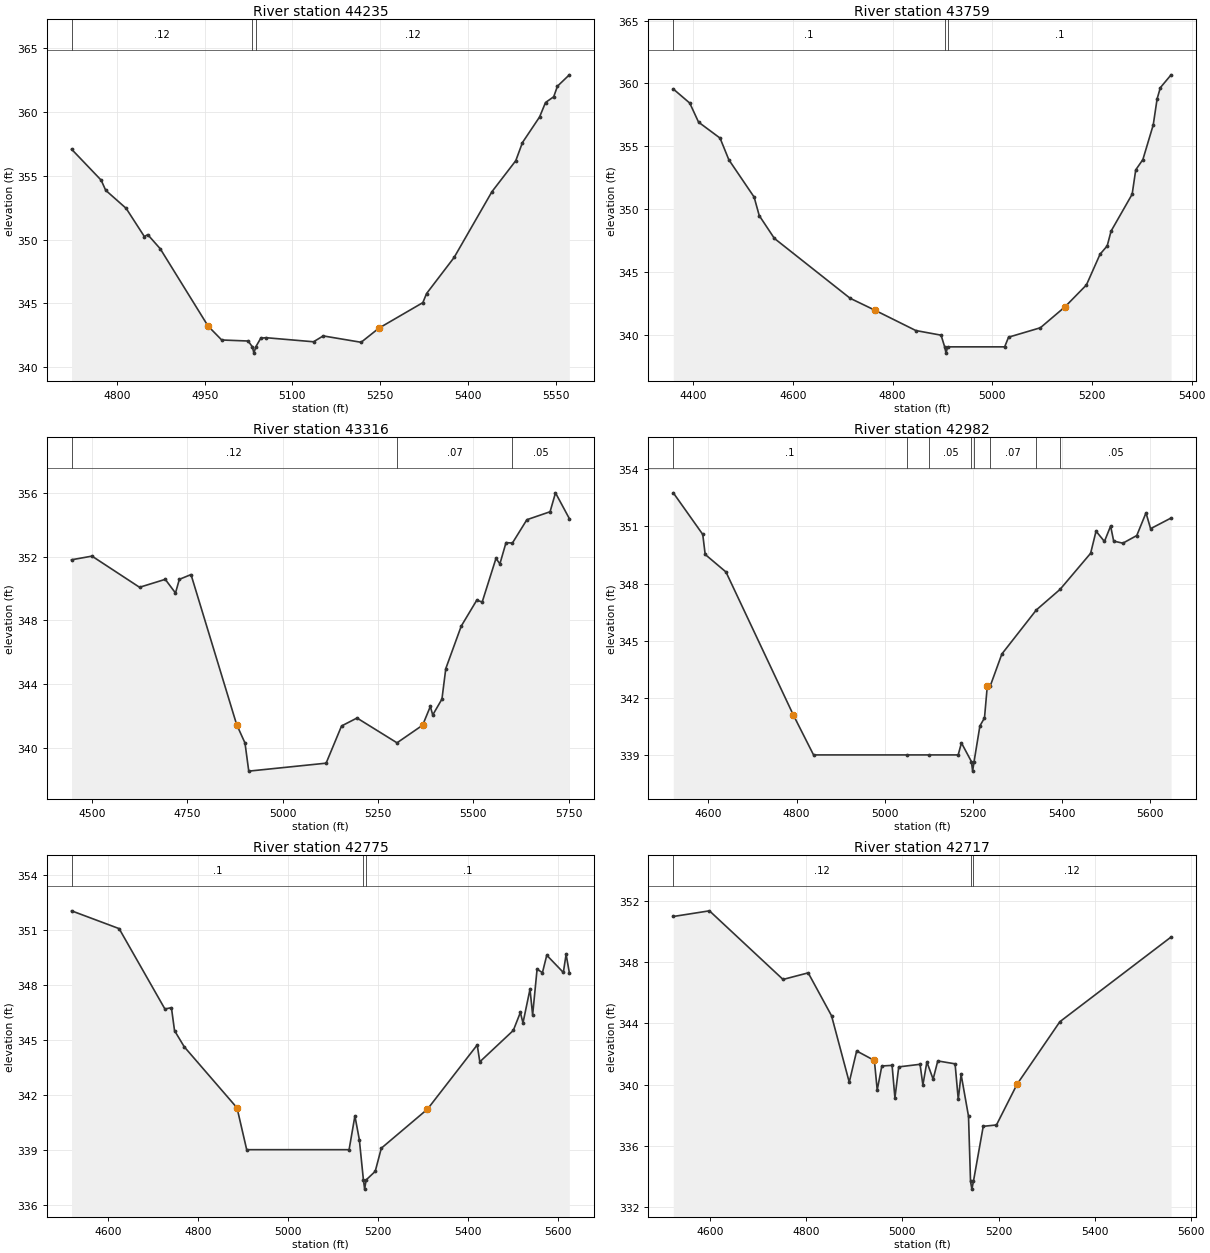
Type RM Length L Ch R = 1 ,44235   ,476,476,476
BEGIN DESCRIPTION:
MITCHELL BRANCH 64.0
END DESCRIPTION:
XS GIS Cut Line= 3
      3653699.62     10716410.18      3653449.61     10716560.19
      3652899.59     10716660.19
#Sta/Elev= 30
  4722.6  357.09  4773.2  354.66  4780.9  353.87  4815.9  352.45    4847  350.24
  4852.8  350.39  4874.2  349.28  4955.9  343.22  4979.2  342.13  5024.3  342.05
  5031.5   341.6  5034.2   341.1  5037.5   341.6  5045.9  342.27  5054.8  342.31
  5136.1  341.99  5152.6  342.45  5217.4  341.95  5247.9  343.06  5322.9  345.06
  5329.2  345.77  5376.3   348.6    5441  353.76  5481.7  356.19  5493.1  357.61
  5522.4  359.62  5532.5  360.75  5546.5   361.2  5552.9  362.03  5573.2  362.92
#Mann= 3 ,-1 , 0
  4722.6     .12       0  5031.5     .03       0  5037.5     .12       0
Bank Sta=4955.9,5247.9
XS Rating Curve= 0 ,0
Exp/Cntr=0.3,0.1

Type RM Length L Ch R = 1 ,43759   ,443,443,443
BEGIN DESCRIPTION:
MITCHELL BRANCH 63.0
END DESCRIPTION:
XS GIS Cut Line= 3
      3653749.63     10716160.19      3653149.61     10716260.19
      3652849.61     10716510.19
#Sta/Elev= 30
  4359.9  359.56  4392.9  358.44  4410.6  356.92  4453.7  355.65  4471.4  353.92
  4522.1  350.95  4532.3  349.48  4562.7  347.66  4714.7  342.89  4765.4  341.92
  4846.5  340.32  4897.2  339.95  4904.4  339.02  4907.1  338.52  4910.4  339.02
  5024.8  339.02  5032.6  339.79  5096.4  340.54  5145.9  342.21  5188.8  343.95
  5216.2   346.4  5230.5  347.06  5238.3  348.24  5280.6  351.18  5287.8  353.12
  5302.1  353.94  5322.9   356.7  5330.7  358.78  5337.2  359.67  5358.7  360.69
#Mann= 3 ,-1 , 0
  4359.9      .1       0  4904.4     .03       0  4910.4      .1       0
Bank Sta=4765.4,5145.9
XS Rating Curve= 0 ,0
Exp/Cntr=0.3,0.1

Type RM Length L Ch R = 1 ,43316   ,334,334,334
BEGIN DESCRIPTION:
MITCHELL BRANCH 62.0
END DESCRIPTION:
XS GIS Cut Line= 2
      3653508.77     10715787.01      3652219.71       10715991.
#Sta/Elev= 30
  4446.9  351.81  4500.5  352.04  4625.2  350.08  4692.6  350.58  4719.4  349.72
  4729.5  350.58  4760.1  350.88  4879.7  341.45  4901.6  340.29  4911.5  338.52
  5114.3  339.02  5154.8  341.36  5195.3  341.86  5300.2   340.3  5367.4  341.41
  5387.6  342.59  5393.8  342.05    5418  343.05  5428.1  344.97  5468.6  347.64
  5509.1  349.26  5523.6  349.16  5559.7   351.9  5569.9  351.55    5586  352.89
  5602.7  352.86  5640.7  354.33  5701.5  354.83  5715.7  356.02    5752   354.4
#Mann= 3 ,-1 , 0
  4446.9     .12       0  5300.2     .07       0  5602.7     .05       0
Bank Sta=4879.7,5367.4
XS Rating Curve= 0 ,0
Exp/Cntr=0.3,0.1

Type RM Length L Ch R = 1 ,42982   ,207,207,207
BEGIN DESCRIPTION:
MITCHELL BRANCH 61.0
END DESCRIPTION:
XS GIS Cut Line= 3
      3653341.55     10715357.02      3652794.58     10715591.31
      3652285.19     10715745.33
#Sta/Elev= 30
  4520.9  352.76  4587.6  350.58  4593.1  349.53  4640.2  348.61  4792.6  341.12
  4838.5  339.02  5049.6  339.02  5100.6  339.02    5166  339.02  5173.4  339.65
    5196  338.67  5198.7  338.17    5202  338.67  5215.2  340.54  5225.6  340.96
  5231.9  342.62  5238.4  342.62  5264.9  344.31    5343  346.62  5396.8   347.7
  5465.9  349.59  5478.2  350.75  5497.2  350.21  5511.2  351.02  5518.1  350.23
  5538.9  350.12  5570.4  350.52  5591.3  351.71  5601.7  350.88  5648.1  351.44
#Mann= 8 ,-1 , 0
  4520.9      .1       0  5049.6     .07       0  5100.6     .05       0
    5196     .03       0    5202     .05       0  5238.4     .07       0
    5343     .16       0  5396.8     .05       0
Bank Sta=4792.6,5231.9
XS Rating Curve= 0 ,0
Exp/Cntr=0.3,0.1

Type RM Length L Ch R = 1 ,42775   ,58,58,58
BEGIN DESCRIPTION:
Mapping XS c581ae92
END DESCRIPTION:
XS GIS Cut Line= 2
      3653280.77     10715098.79      3652328.11     10715658.66
#Sta/Elev= 30
  4519.5  352.04  4625.1  351.07  4726.7  346.69  4741.2  346.76  4748.1  345.51
  4769.6  344.63  4886.8   341.3  4908.3  339.02  5135.6  339.02  5148.5  340.86
  5158.3  339.57  5167.4  337.37  5170.1  336.87  5173.4  337.37  5193.6  337.84
  5207.1   339.1  5309.6  341.23    5420  344.73  5425.8  343.81  5500.1  345.52
  5515.8   346.5  5521.6  345.93  5537.2  347.77    5543  346.36  5552.9  348.86
  5564.8  348.67  5574.4  349.62  5611.2  348.68  5617.3  349.67  5624.5  348.67
#Mann= 3 ,-1 , 0
  4519.5      .1       0  5167.4    .033       0  5173.4      .1       0
Bank Sta=4886.8,5309.6
XS Rating Curve= 0 ,0
Exp/Cntr=0.3,0.1

Type RM Length L Ch R = 1 ,42717   ,136,136,136
BEGIN DESCRIPTION:
Mapping XS a0ad14ff
END DESCRIPTION:
XS GIS Cut Line= 2
      3653239.59     10715046.67      3652356.34     10715584.87
#Sta/Elev= 30
  4524.2  350.98  4599.3  351.35  4752.2  346.87  4804.5   347.3    4853   344.5
  4889.8  340.16  4905.2   342.2    4942  341.58  4947.9  339.65  4957.5  341.22
  4978.8  341.26  4984.7  339.13  4992.6  341.16  5036.9  341.33  5042.8  339.98
  5051.1  341.48  5064.1  340.36  5073.7  341.55  5109.7  341.36  5116.3  339.04
  5122.2  340.67  5137.6  337.94  5141.8  333.68  5144.6  333.18  5147.8  333.68
  5168.2  337.28  5195.7  337.37  5238.5  340.03  5327.4  344.11  5558.5  349.64
#Mann= 3 ,-1 , 0
  4524.2     .12       0  5141.8     .03       0  5147.8     .12       0
Bank Sta=4942,5238.5
XS Rating Curve= 0 ,0
Exp/Cntr=0.3,0.1

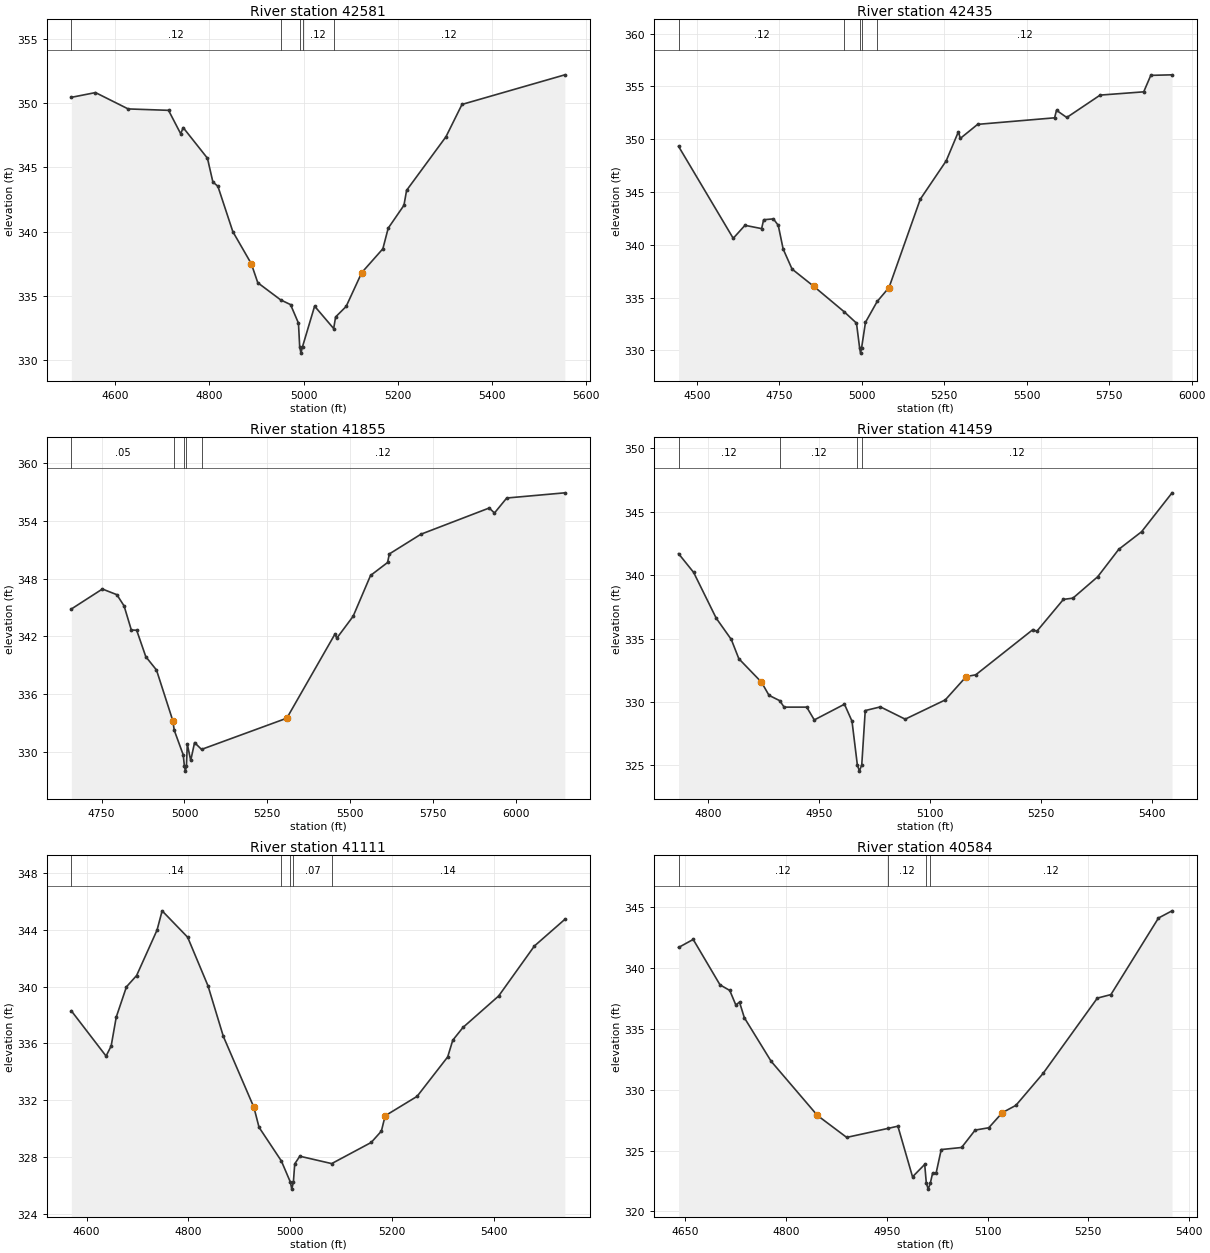
Type RM Length L Ch R = 1 ,42581   ,146,146,146
BEGIN DESCRIPTION:
Mapping XS c81a7653
END DESCRIPTION:
XS GIS Cut Line= 3
      3653213.53     10715018.47      3652803.35     10715161.71
      3652253.37     10715434.53
#Sta/Elev= 30
  4506.8  350.44  4558.1  350.81  4627.5  349.54  4713.3  349.43  4739.1  347.61
  4744.4  348.09  4795.9  345.71  4807.5  343.86  4818.1  343.53  4849.9     340
  4889.1  337.51  4902.9  336.03  4951.4   334.7  4972.5  334.33  4989.3  332.89
  4991.9  331.06  4994.6  330.56  4997.9  331.06  5023.6  334.21  5064.1  332.47
  5068.2  333.37  5090.6  334.19  5123.8  336.82  5168.6  338.67  5179.9  340.27
  5213.4  342.05    5219  343.21  5302.7  347.38  5336.7  349.89  5555.2  352.19
#Mann= 5 ,-1 , 0
  4506.8     .12       0  4951.4     .12       0  4991.9     .07       0
  4997.9     .12       0  5064.1     .12       0
Bank Sta=4889.1,5123.8
XS Rating Curve= 0 ,0
Exp/Cntr=0.3,0.1

Type RM Length L Ch R = 1 ,42435   ,580,580,580
BEGIN DESCRIPTION:
MITCHELL BRANCH 60.0
END DESCRIPTION:
XS GIS Cut Line= 3
      3653109.08     10714758.77      3652484.05     10715203.24
      3651859.06     10715578.23
#Sta/Elev= 30
  4444.8  349.33  4610.5  340.62  4646.1  341.85  4696.6  341.54  4702.7  342.38
  4732.2  342.46    4747  341.85  4761.8  339.61  4788.8  337.71    4854  336.09
    4947  333.66  4984.1  332.59  4993.6  330.25  4996.4  329.75  4999.6  330.25
  5011.4  332.67  5046.8  334.64  5082.7  335.96  5177.4  344.32  5256.1  347.96
    5293  350.71  5298.8  350.08  5351.3  351.41  5584.6  352.03  5590.4  352.74
  5621.5  352.06  5722.6  354.18  5854.7  354.49  5876.1  356.05  5940.6   356.1
#Mann= 5 ,-1 , 0
  4444.8     .12       0    4947     .12       0  4993.6     .07       0
  4999.6     .12       0  5046.8     .12       0
Bank Sta=4854,5082.7
XS Rating Curve= 0 ,0
Exp/Cntr=0.3,0.1

Type RM Length L Ch R = 1 ,41855   ,396,396,396
BEGIN DESCRIPTION:
MITCHELL BRANCH 59.0
END DESCRIPTION:
XS GIS Cut Line= 3
      3652866.01     10714369.89      3652361.95     10714644.61
      3651492.83     10714931.79
#Sta/Elev= 30
  4658.5  344.85  4752.2  346.93  4795.9  346.34  4817.7  345.17  4839.5  342.67
  4855.7  342.64  4883.2  339.89  4915.5   338.5  4964.9  333.21    4969  332.24
  4996.1  329.68  4999.8  328.48  5002.6  327.98  5005.8  328.48  5008.5  330.79
  5018.8  329.09  5030.4  330.95  5051.4  330.24  5308.8  333.49  5454.2  342.25
  5459.5  341.81  5508.9  344.09  5561.5  348.34  5612.9  349.69  5618.2  350.58
  5713.4  352.63  5919.6  355.36  5935.5  354.84  5972.5   356.4  6147.9  356.94
#Mann= 5 ,-1 , 0
  4658.5     .05       0    4969     .12       0  4999.8     .07       0
  5005.8     .12       0  5051.4     .12       0
Bank Sta=4964.9,5308.8
XS Rating Curve= 0 ,0
Exp/Cntr=0.3,0.1

Type RM Length L Ch R = 1 ,41459   ,348,348,348
BEGIN DESCRIPTION:
MITCHELL BRANCH 58.0
END DESCRIPTION:
XS GIS Cut Line= 3
      3652599.57     10714310.18      3652349.61     10714260.19
      3651949.63     10714160.19
#Sta/Elev= 30
  4759.9   341.7  4780.3  340.22  4810.8  336.61  4831.2  334.93  4841.4  333.41
    4872  331.56  4882.2  330.52  4896.7   330.1  4902.6  329.59  4933.2  329.59
  4943.4  328.58  4984.2  329.82  4994.4  328.48  5001.6  325.04  5004.4  324.54
  5007.6  325.04  5012.3  329.32  5032.8  329.61  5066.3  328.64  5120.5  330.16
  5148.8     332  5161.7  332.14    5239  335.71  5244.2  335.57  5280.2  338.09
  5293.1  338.19  5326.6  339.88    5355  342.04  5385.9  343.43  5427.1   346.5
#Mann= 4 ,-1 , 0
  4759.9     .12       0  4896.7     .12       0  5001.6     .07       0
  5007.6     .12       0
Bank Sta=4872,5148.8
XS Rating Curve= 0 ,0
Exp/Cntr=0.3,0.1

Type RM Length L Ch R = 1 ,41111   ,527,527,527
BEGIN DESCRIPTION:
MITCHELL BRANCH 57.0
END DESCRIPTION:
XS GIS Cut Line= 2
      3652857.67     10713968.43      3651889.87     10713916.35
#Sta/Elev= 30
  4570.1  338.29  4638.3   335.1  4648.3  335.81  4658.3  337.85  4678.3  339.98
  4698.3  340.78  4738.4  343.98  4748.4  345.34  4798.5  343.48  4838.5  340.05
  4868.6  336.49  4928.7  331.48  4938.7  330.08  4982.5  327.71  5000.2  326.22
    5003  325.72  5006.2  326.22  5008.8   327.5  5018.8  328.04  5081.4  327.52
    5159  329.01    5179  329.81  5186.4  330.89  5249.1  332.26  5309.2  335.04
  5319.2  336.22  5339.3  337.12  5409.4  339.34  5479.5  342.86  5539.3  344.74
#Mann= 5 ,-1 , 0
  4570.1     .14       0  4982.5     .07       0  5000.2     .07       0
  5006.2     .07       0  5081.4     .14       0
Bank Sta=4928.7,5186.4
XS Rating Curve= 0 ,0
Exp/Cntr=0.3,0.1

Type RM Length L Ch R = 1 ,40584   ,492,492,492
BEGIN DESCRIPTION:
MITCHELL BRANCH 56.0
END DESCRIPTION:
XS GIS Cut Line= 3
      3652699.63      10713660.2      3652349.61     10713510.19
      3651999.57     10713560.19
#Sta/Elev= 30
  4640.2  341.68    4662  342.34  4701.9  338.61  4716.4  338.15  4725.4  336.96
  4730.9  337.19  4738.1  335.91    4778  332.33  4846.9  327.88  4890.4  326.08
  4952.1  326.82  4966.6     327  4988.4  322.84  5006.5  323.86  5008.9  322.33
  5011.7  321.83  5014.9  322.33  5018.3  323.15  5023.5  323.15  5031.1  325.08
  5061.4  325.25  5081.6  326.68  5101.8  326.87    5122  328.11  5142.2  328.71
  5182.6  331.33  5263.4  337.52  5283.6  337.81  5354.4   344.1  5374.6  344.69
#Mann= 4 ,-1 , 0
  4640.2     .12       0  4952.1     .12       0  5008.9     .07       0
  5014.9     .12       0
Bank Sta=4846.9,5122
XS Rating Curve= 0 ,0
Exp/Cntr=0.3,0.1

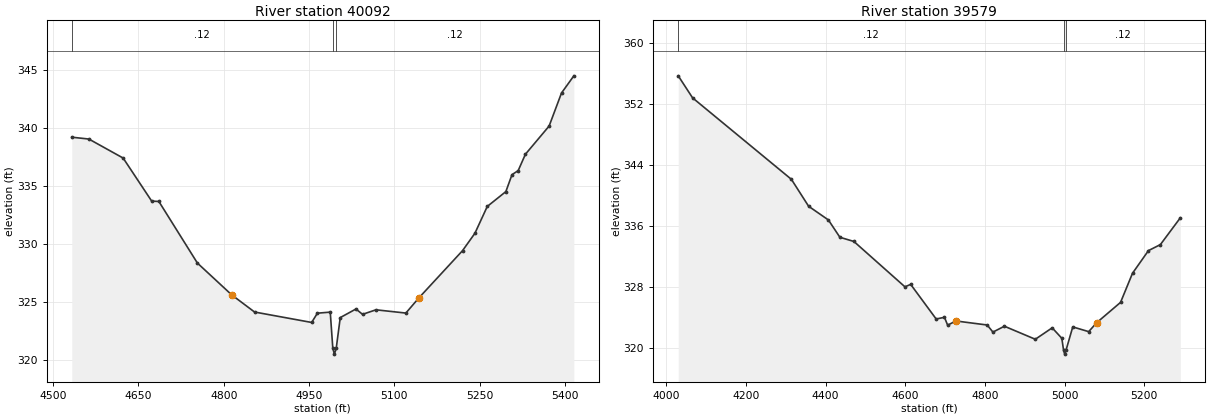
Type RM Length L Ch R = 1 ,40092   ,513,513,513
BEGIN DESCRIPTION:
MITCHELL BRANCH 55.0
END DESCRIPTION:
XS GIS Cut Line= 3
      3652849.56     10713110.18      3652349.61     10713060.19
      3651999.64     10713210.18
#Sta/Elev= 30
  4532.7  339.17  4562.8  339.01  4623.1  337.37  4673.3  333.66  4685.9  333.63
  4753.7  328.32    4814  325.58  4854.2   324.1  4954.7   323.2  4964.8     324
  4987.4  324.09  4991.9  320.97  4994.7  320.47  4997.9  320.97    5005  323.62
  5032.6  324.36  5044.2   323.9  5067.8  324.29  5120.4  324.01  5143.9  325.35
  5220.1  329.39  5241.9  330.89  5263.6   333.2  5296.3  334.48  5307.1  335.94
    5318  336.29  5330.7   337.7  5372.4  340.13  5394.2  342.98  5415.9  344.46
#Mann= 3 ,-1 , 0
  4532.7     .12       0  4991.9     .03       0  4997.9     .12       0
Bank Sta=4814,5143.9
XS Rating Curve= 0 ,0
Exp/Cntr=0.3,0.1

Type RM Length L Ch R = 1 ,39579   ,487,487,487
BEGIN DESCRIPTION:
MITCHELL BRANCH 54.0
END DESCRIPTION:
XS GIS Cut Line= 3
      3653099.59      10712010.2      3652349.61     10712610.19
      3652049.66     10712610.19
#Sta/Elev= 30
  4029.9  355.74  4065.9  352.85    4314  342.16  4357.2  338.63  4406.9  336.83
  4435.7  334.56  4470.9  334.01    4599  328.06  4613.4  328.38  4677.4  323.84
  4698.2  324.06  4706.2  323.03    4727  323.58  4805.5  323.05  4819.9  322.12
  4848.7  322.89  4926.3  321.18  4968.7  322.68  4992.8  321.31  4997.3  319.73
  5000.1  319.23  5003.3  319.73  5020.3   322.8  5060.3  322.18  5080.3  323.35
  5140.3  326.02  5170.3  329.84  5210.3  332.81  5240.3   333.6  5290.3  337.11
#Mann= 3 ,-1 , 0
  4029.9     .12       0  4997.3     .03       0  5003.3     .12       0
Bank Sta=4727,5080.3
XS Rating Curve= 0 ,0
Exp/Cntr=0.3,0.1