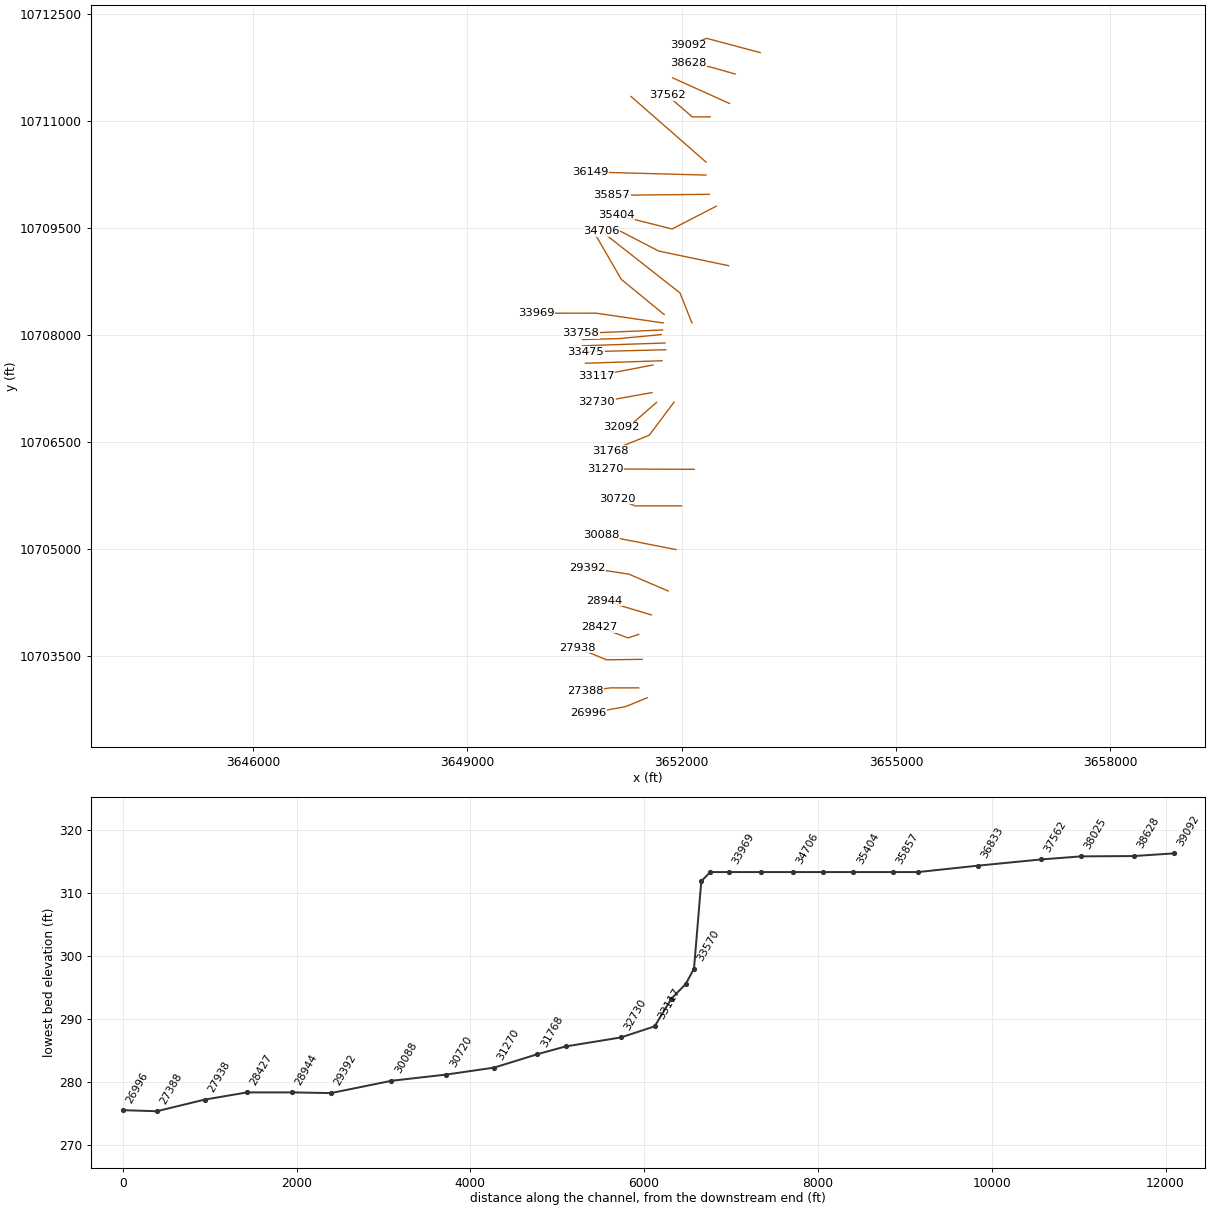
HEC-RAS study MITCHELL BRANCH.prj: MITCHELL BRANCH Base Level Engineering

--- MITCHELL BRANCH.g01 (geometry) --- (continued)

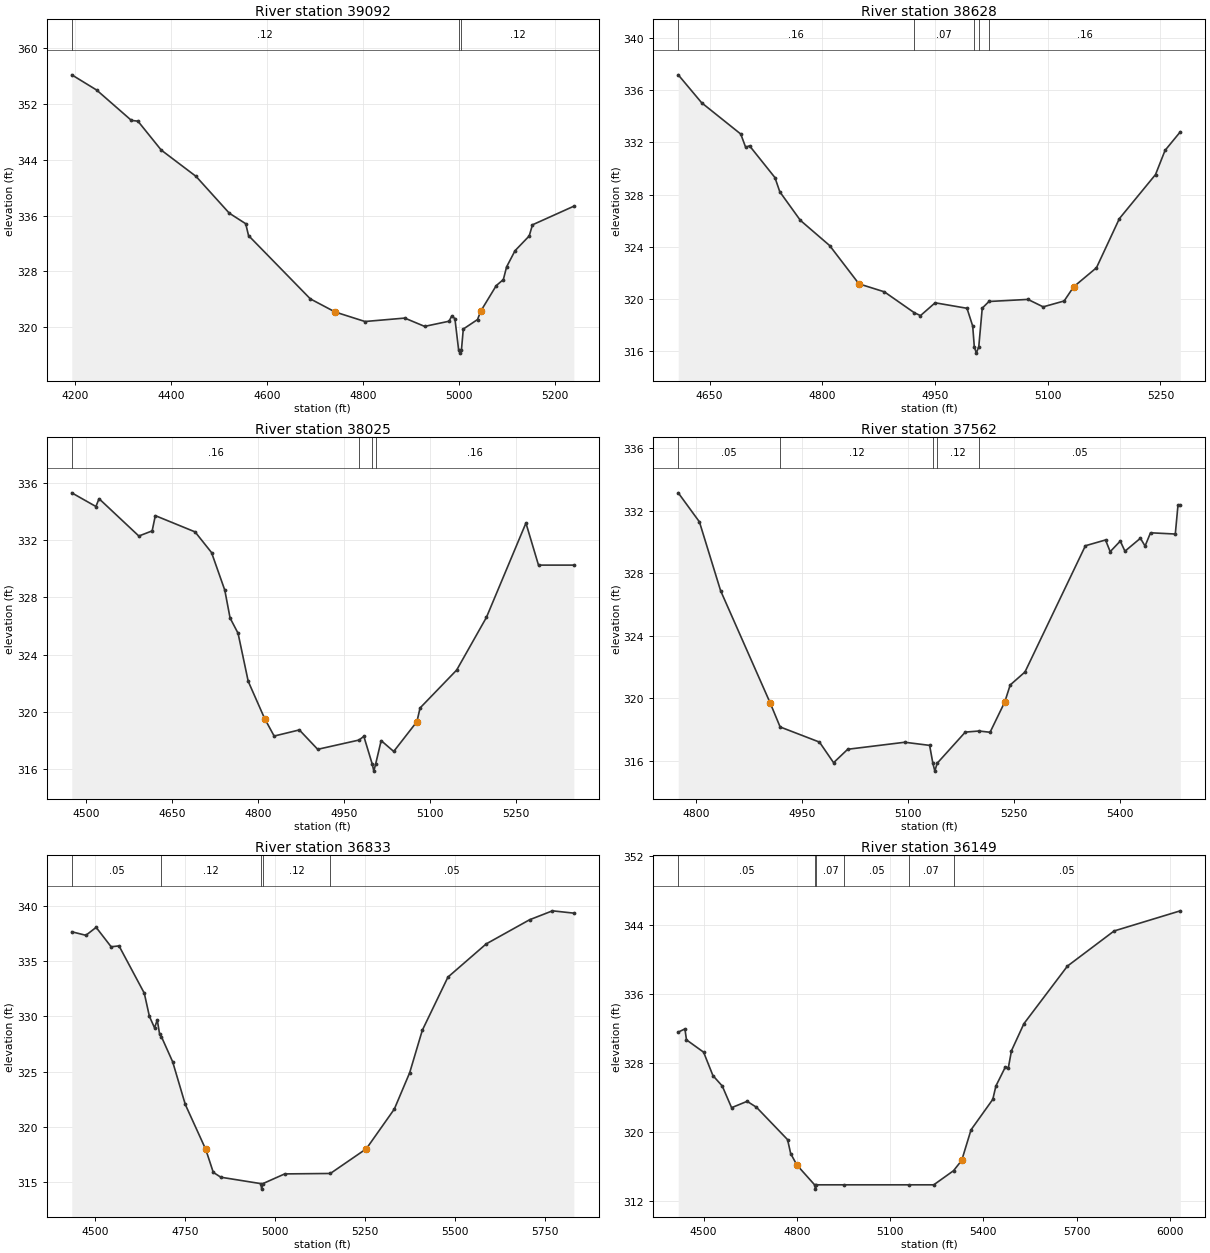
Type RM Length L Ch R = 1 ,39092   ,464,464,464
BEGIN DESCRIPTION:
MITCHELL BRANCH 53.0
END DESCRIPTION:
XS GIS Cut Line= 3
      3653099.62     10711960.18      3652349.61     10712160.19
      3652099.59     10712060.18
#Sta/Elev= 30
  4193.1  356.16  4244.9  353.98  4317.3  349.63  4330.9  349.52  4379.4  345.38
  4451.9  341.61  4521.1  336.34  4555.3  334.83  4561.2  333.13  4689.9  324.06
  4741.6  322.18  4803.7  320.82  4886.5  321.31  4927.9  320.12  4978.7  320.86
  4984.1  321.58  4990.9  321.25  4998.6  316.79  5001.4  316.29  5004.6  316.79
  5008.4  319.74    5038   321.1  5044.7   322.3    5077  325.96  5091.8  326.83
  5098.6  328.65  5116.1  330.96  5145.7  333.08  5152.4  334.67  5238.6  337.34
#Mann= 3 ,-1 , 0
  4193.1     .12       0  4998.6     .03       0  5004.6     .12       0
Bank Sta=4741.6,5044.7
XS Rating Curve= 0 ,0
Exp/Cntr=0.3,0.1

Type RM Length L Ch R = 1 ,38628   ,603,603,603
BEGIN DESCRIPTION:
MITCHELL BRANCH 52.0
END DESCRIPTION:
XS GIS Cut Line= 3
      3652749.62     10711660.18      3652399.61     10711760.19
      3652099.57      10711810.2
#Sta/Elev= 30
  4608.3  337.16  4639.5  335.02  4691.5  332.63    4698  331.62  4703.2  331.73
    4737   329.3  4743.5  328.21  4770.8  326.03  4809.8   324.1  4848.8  321.17
  4882.6  320.56  4922.5  318.96  4930.7  318.74  4950.2  319.72  4992.6   319.3
  5000.2  317.94  5002.3  316.37    5005  315.87  5008.3  316.37  5012.9  319.31
  5021.8  319.82  5073.7  319.98    5094  319.41  5121.9  319.86  5134.5  320.94
  5164.9   322.4  5195.4  326.16  5243.5  329.53  5256.2  331.38  5276.5   332.8
#Mann= 5 ,-1 , 0
  4608.3     .16       0  4922.5     .07       0  5002.3     .07       0
  5008.3     .07       0  5021.8     .16       0
Bank Sta=4848.8,5134.5
XS Rating Curve= 0 ,0
Exp/Cntr=0.3,0.1

Type RM Length L Ch R = 1 ,38025   ,463,463,463
BEGIN DESCRIPTION:
MITCHELL BRANCH 51.0
END DESCRIPTION:
XS GIS Cut Line= 2
      3652671.11     10711247.06       3651873.5     10711606.85
#Sta/Elev= 30
  4475.4  335.34  4517.5  334.38  4522.9  334.93  4592.3  332.31  4615.5  332.67
    4621  333.74  4690.3   332.6    4719  331.15  4742.1  328.51  4751.3  326.56
  4765.2  325.49  4782.9  322.12  4811.5  319.51  4828.1  318.28    4872  318.71
    4904  317.35    4976     318  4984.4  318.26    4999  316.32  5001.8  315.82
    5005  316.32  5014.6  317.96  5036.5   317.2  5076.9  319.29  5082.4  320.25
  5146.2  322.91    5198   326.6  5266.9  333.22  5288.8  330.27  5350.4  330.27
#Mann= 4 ,-1 , 0
  4475.4     .16       0    4976     .12       0    4999     .07       0
    5005     .16       0
Bank Sta=4811.5,5076.9
XS Rating Curve= 0 ,0
Exp/Cntr=0.3,0.1

Type RM Length L Ch R = 1 ,37562   ,729,729,729
BEGIN DESCRIPTION:
MITCHELL BRANCH 50.0
END DESCRIPTION:
XS GIS Cut Line= 3
      3652399.66     10711060.19      3652149.61     10711060.19
      3651799.63     10711360.17
#Sta/Elev= 30
  4774.5  333.16  4804.5   331.3  4834.5  326.89  4904.5  319.72  4918.8  318.16
  4974.5  317.19  4994.5  315.87  5014.5  316.73  5095.3  317.18  5130.5  316.98
  5135.1  315.83  5137.9  315.33  5141.1  315.83    5181  317.83  5200.4   317.9
  5216.1  317.82  5236.9  319.76  5244.6  320.85  5265.5  321.68  5351.1  329.77
  5379.6  330.14  5386.2  329.39  5400.5  330.07  5407.1  329.42    5429  330.25
  5435.6  329.75  5443.3   330.6  5478.4  330.52  5482.2  332.37  5485.5  332.37
#Mann= 5 ,-1 , 0
  4774.5     .05       0  4918.8     .12       0  5135.1     .07       0
  5141.1     .12       0  5200.4     .05       0
Bank Sta=4904.5,5236.9
XS Rating Curve= 0 ,0
Exp/Cntr=0.3,0.1

Type RM Length L Ch R = 1 ,36833   ,684,684,684
BEGIN DESCRIPTION:
MITCHELL BRANCH 49.0
END DESCRIPTION:
XS GIS Cut Line= 2
      3652341.18      10710426.8      3651291.87     10711346.03
#Sta/Elev= 30
  4434.6  337.68  4473.8  337.36  4502.3  338.08    4544  336.32  4565.9   336.4
  4636.1  332.11  4650.3  330.01  4664.6  328.97  4672.2  329.68  4678.8  328.37
  4683.9  328.15  4714.9  325.89    4750  322.02  4806.9  317.94  4827.8  315.86
  4848.8  315.42  4959.6  314.84  4962.3  314.34  4965.6  314.84  5026.2  315.72
  5153.1  315.76    5253     318  5330.8   321.6  5373.5   324.9  5408.6  328.75
  5479.8  333.57  5586.1  336.58  5706.6  338.77  5770.2  339.58  5829.6  339.37
#Mann= 5 ,-1 , 0
  4434.6     .05       0  4683.9     .12       0  4959.6     .07       0
  4965.6     .12       0  5153.1     .05       0
Bank Sta=4806.9,5253
XS Rating Curve= 0 ,0
Exp/Cntr=0.3,0.1

Type RM Length L Ch R = 1 ,36149   ,292,292,292
BEGIN DESCRIPTION:
MITCHELL BRANCH 48.0
END DESCRIPTION:
XS GIS Cut Line= 2
      3652341.18     10710244.48      3650726.66     10710287.88
#Sta/Elev= 30
  4418.7  331.57  4440.2  331.94  4445.2  330.67  4500.3  329.24  4530.3  326.52
  4560.3  325.31  4590.3  322.79  4640.3  323.53  4670.4  322.84  4770.4  319.08
  4780.4  317.46  4800.4  316.13  4857.4  313.83  4860.2  313.33  4863.4  313.83
  4952.7  313.83  5160.7  313.83  5240.6  313.83  5304.3  315.47  5330.6  316.67
  5360.6  320.22  5430.6  323.76  5440.6  325.31  5470.6  327.49  5480.7  327.44
  5490.7  329.41  5530.7  332.55  5670.7  339.24  5820.8  343.32  6033.8  345.66
#Mann= 6 ,-1 , 0
  4418.7     .05       0  4857.4    .033       0  4863.4     .07       0
  4952.7     .05       0  5160.7     .07       0  5304.3     .05       0
Bank Sta=4800.4,5330.6
XS Rating Curve= 0 ,0
Exp/Cntr=0.3,0.1

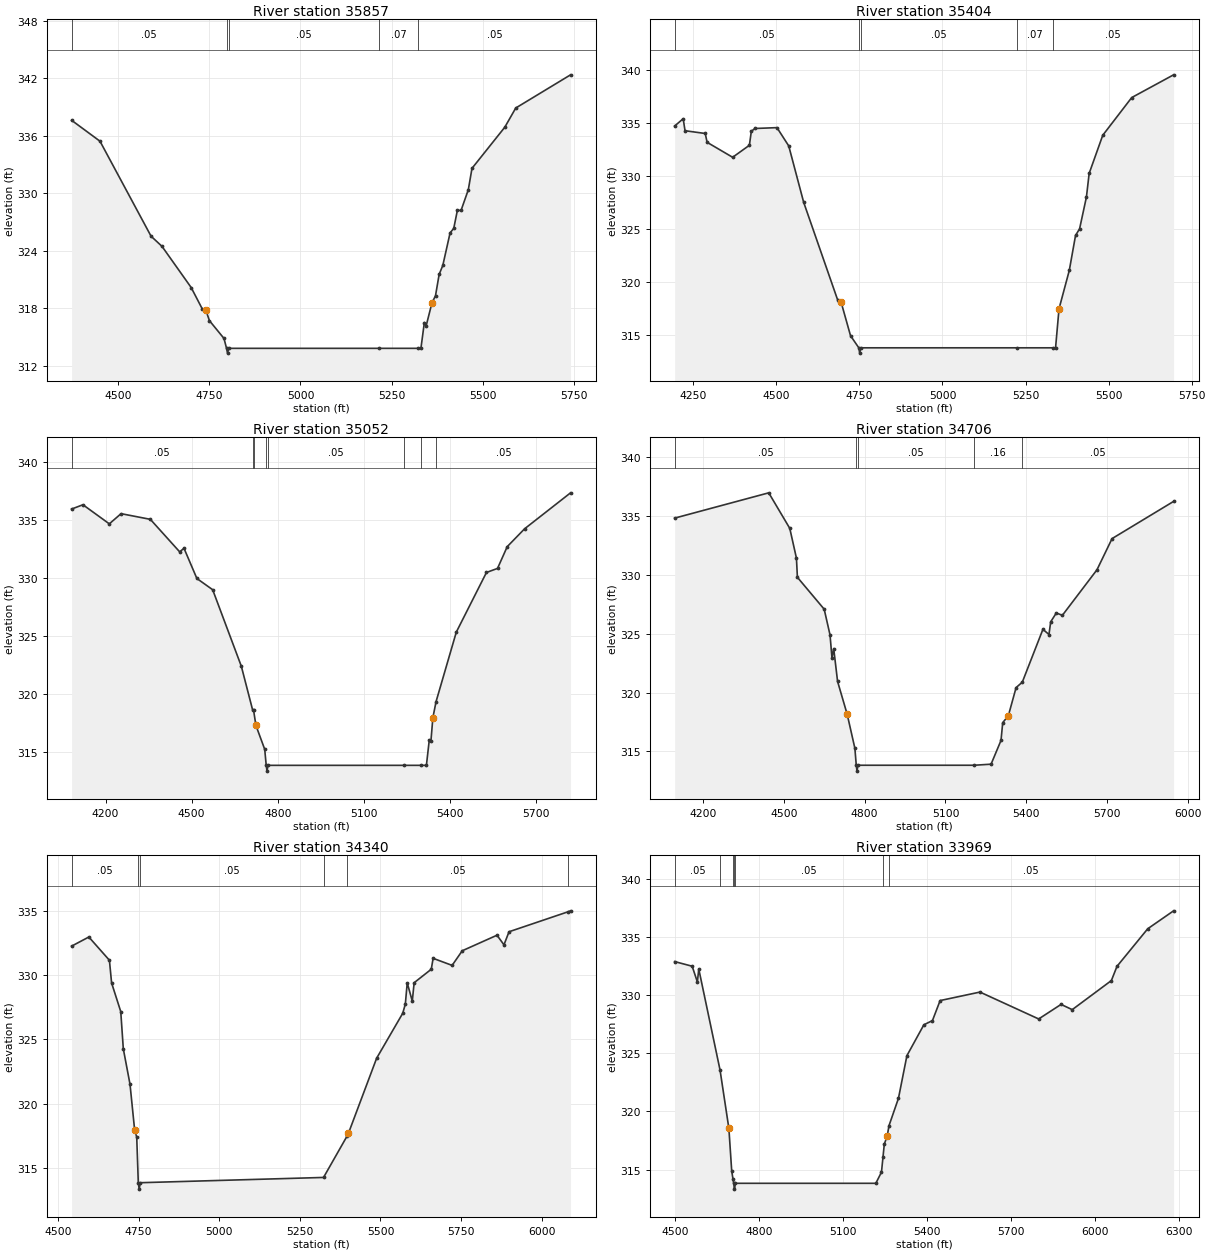
Type RM Length L Ch R = 1 ,35857   ,453,453,453
BEGIN DESCRIPTION:
MITCHELL BRANCH 47.0
END DESCRIPTION:
XS GIS Cut Line= 2
      3652387.37     10709975.05      3651019.35     10709961.16
#Sta/Elev= 30
  4372.5   337.6  4450.3  335.42  4590.3  325.52  4620.3  324.46  4700.3  320.17
  4730.3  317.97  4740.3  317.84  4750.3  316.72  4790.3  314.86  4797.3  313.83
    4800  313.33  4803.3  313.83  5214.3  313.83  5322.7  313.83  5330.3  313.83
  5339.7  316.52  5344.7  316.18  5360.3  318.53  5370.3  319.32  5380.3  321.54
  5390.3  322.47  5410.3  325.87  5420.3  326.33  5430.3  328.22  5440.3   328.2
  5460.3  330.37  5470.3  332.59  5560.3  336.88  5590.3  338.88  5740.6  342.34
#Mann= 5 ,-1 , 0
  4372.5     .05       0  4797.3    .033       0  4803.3     .05       0
  5214.3     .07       0  5322.7     .05       0
Bank Sta=4740.3,5360.3
XS Rating Curve= 0 ,0
Exp/Cntr=0.3,0.1

Type RM Length L Ch R = 1 ,35404   ,352,352,352
BEGIN DESCRIPTION:
MITCHELL BRANCH 46.0
END DESCRIPTION:
XS GIS Cut Line= 3
      3652484.67      10709808.4      3651866.59     10709488.94
      3651085.33     10709686.86
#Sta/Elev= 30
  4193.9   334.7  4219.6  335.39  4225.2  334.26    4286     334  4291.6  333.17
  4368.5  331.76  4418.9  332.89  4424.7   334.2  4435.4  334.47  4501.9  334.55
  4537.3  332.83  4582.3  327.52  4684.7  318.32  4694.9  318.13  4723.3  314.97
  4748.2  313.83  4750.9  313.33  4754.2  313.83  5224.9  313.83  5331.2  313.83
  5340.4  313.83  5350.8   317.5  5381.7  321.11  5400.5   324.4  5412.7  325.03
  5433.3  328.02  5441.5  330.24  5482.4  333.83  5569.6  337.38  5695.6  339.52
#Mann= 5 ,-1 , 0
  4193.9     .05       0  4748.2    .033       0  4754.2     .05       0
  5224.9     .07       0  5331.2     .05       0
Bank Sta=4694.9,5350.8
XS Rating Curve= 0 ,0
Exp/Cntr=0.3,0.1

Type RM Length L Ch R = 1 ,35052   ,346,346,346
BEGIN DESCRIPTION:
MITCHELL BRANCH 45.0
END DESCRIPTION:
XS GIS Cut Line= 3
      3652658.24     10708975.06      3651679.09     10709179.91
      3651023.71     10709519.74
#Sta/Elev= 30
  4081.8  335.97  4121.3  336.34  4213.2  334.69  4254.1  335.57  4356.2  335.08
  4458.4  332.27  4473.4  332.58  4518.3  329.97  4573.3     329  4673.2  322.39
    4713  318.57  4715.9  318.59    4724  317.28  4754.7  315.21  4759.9  313.83
  4762.7  313.33  4765.9  313.83  5239.1  313.83  5298.6  313.83  5318.1  313.83
  5328.2  316.04  5333.8  315.91  5340.6  317.94  5351.8  319.34  5422.3  325.34
  5527.3  330.49  5565.9  330.84  5599.7  332.72  5660.1  334.26  5820.4  337.37
#Mann= 8 ,-1 , 0
  4081.8     .05       0    4713     .07       0  4715.9     .05       0
  4759.9    .033       0  4765.9     .05       0  5239.1     .16       0
  5298.6     .07       0  5351.8     .05       0
Bank Sta=4724,5340.6
XS Rating Curve= 0 ,0
Exp/Cntr=0.3,0.1

Type RM Length L Ch R = 1 ,34706   ,366,366,366
BEGIN DESCRIPTION:
Mapping XS cb0db3f1
END DESCRIPTION:
XS GIS Cut Line= 3
      3652144.35       10708173.       3651977.7     10708593.11
      3650877.01     10709457.69
#Sta/Elev= 30
  4094.9  334.83  4444.1  336.98  4522.2  333.96  4546.9  331.43  4550.5   329.8
  4649.9  327.09  4671.6   324.9  4678.8  322.94  4685.2  323.74  4699.6  320.95
  4735.2  318.16  4763.8  315.27  4768.9  313.83  4771.7  313.33  4774.9  313.83
  5206.9  313.83  5269.2  313.92  5306.1  315.94  5312.4  317.45  5333.2  318.03
  5362.1  320.43  5385.1  320.89  5461.6  325.38  5484.1  324.94  5490.5  326.02
  5511.3  326.77  5533.8  326.57  5662.2  330.44  5718.2  333.09  5946.5  336.25
#Mann= 5 ,-1 , 0
  4094.9     .05       0  4768.9    .033       0  4774.9     .05       0
  5206.9     .16       0  5385.1     .05       0
Bank Sta=4735.2,5333.2
XS Rating Curve= 0 ,0
Exp/Cntr=0.3,0.1

Type RM Length L Ch R = 1 ,34340   ,371,371,371
BEGIN DESCRIPTION:
MITCHELL BRANCH 44.0
END DESCRIPTION:
XS GIS Cut Line= 3
      3651755.48     10708291.02      3651154.78     10708784.08
      3650769.36     10709450.75
#Sta/Elev= 30
  4542.3  332.26  4595.7  332.97  4659.5  331.16  4666.3  329.39  4694.7  327.16
  4702.6  324.26  4723.4   321.5  4737.7  317.94  4744.2  317.39  4749.1  313.83
  4751.8  313.33  4755.1  313.83  5323.5  314.24  5396.9  317.48  5400.6  317.67
  5488.2  323.53  5569.1  327.03  5577.2  327.75    5583   329.4  5598.7  327.98
  5604.5  329.41  5657.6  330.46  5663.3  331.31  5722.2  330.76  5753.7   331.9
  5861.4  333.11    5883  332.36  5898.7  333.38  6081.1  334.93  6089.5  335.01
#Mann= 6 ,-1 , 0
  4542.3     .05       0  4749.1    .033       0  4755.1     .05       0
  5323.5     .16       0  5396.9     .05       0  6081.1     .16       0
Bank Sta=4737.7,5400.6
XS Rating Curve= 0 ,0
Exp/Cntr=0.3,0.1

Type RM Length L Ch R = 1 ,33969   ,211,211,211
BEGIN DESCRIPTION:
MITCHELL BRANCH 43.0
END DESCRIPTION:
XS GIS Cut Line= 3
      3651741.61     10708172.97      3650799.61     10708310.19
      3649967.25     10708308.39
#Sta/Elev= 30
  4497.9  332.88  4560.6  332.48  4579.2  331.13  4584.2  332.24  4660.3  323.56
  4691.9  318.54    4702  314.88  4706.4  314.23  4709.1  313.83  4711.9  313.33
  4715.1  313.83  5217.4  313.83  5237.6  314.79  5243.1   316.1  5247.7   317.2
  5257.8  317.86  5264.6  318.79  5298.3  321.13  5328.6   324.8  5389.2  327.45
  5419.9  327.81  5447.3  329.53  5589.8  330.26  5799.8  327.95  5879.8   329.2
  5919.8  328.75  6059.8  331.25  6079.8  332.47  6189.8   335.7  6282.2  337.24
#Mann= 7 ,-1 , 0
  4497.9     .05       0  4660.3     .16       0  4706.4     .05       0
  4709.1    .033       0  4715.1     .05       0  5243.1     .16       0
  5264.6     .05       0
Bank Sta=4691.9,5257.8
XS Rating Curve= 0 ,0
Exp/Cntr=0.3,0.1

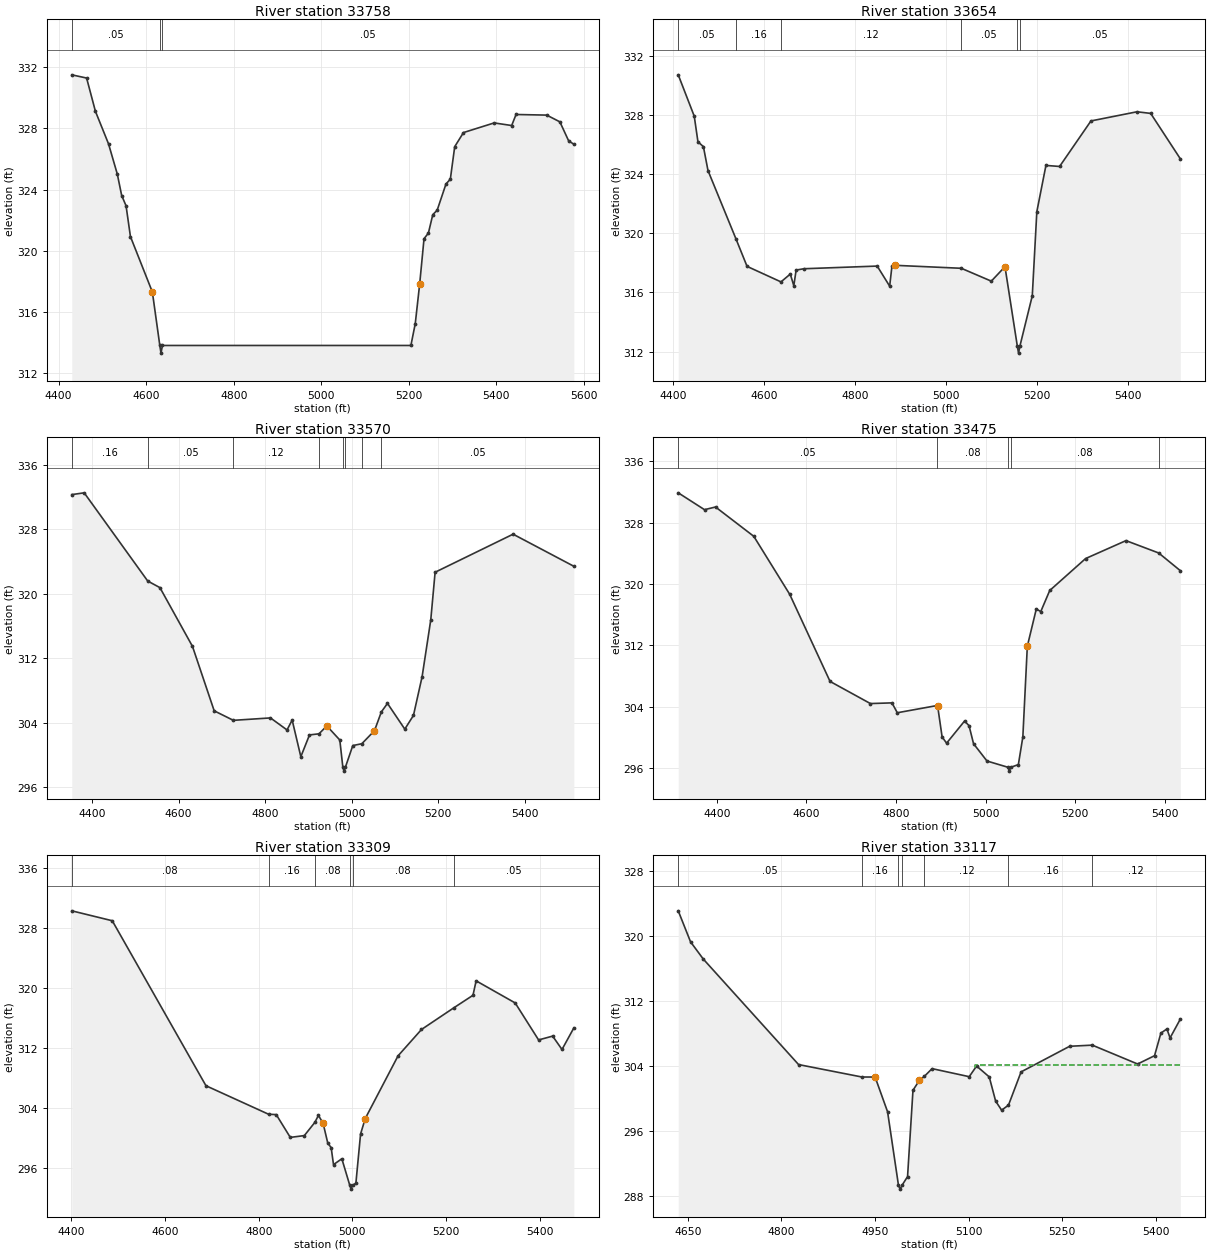
Type RM Length L Ch R = 1 ,33758   ,104,104,104
BEGIN DESCRIPTION:
Mapping XS 96300859
END DESCRIPTION:
XS GIS Cut Line= 2
      3651733.53     10708074.33      3650587.72     10708026.59
#Sta/Elev= 30
  4430.1   331.5    4464  331.29  4484.1  329.12  4514.1  326.99  4534.1  325.02
  4544.1  323.62  4554.1  322.95  4564.1  320.94  4614.2  317.32  4631.2  313.83
  4633.9  313.33  4637.2  313.83  5204.7  313.83  5214.7  315.26  5224.7  317.83
  5234.7   320.8  5244.7  321.17  5254.7  322.37  5264.7  322.66  5284.8  324.37
  5294.8  324.69  5304.8  326.81  5324.8  327.73  5394.9  328.36  5434.9  328.19
  5444.9  328.91    5515  328.87    5545  328.43    5565  327.19  5576.9  326.97
#Mann= 3 ,-1 , 0
  4430.1     .05       0  4631.2    .033       0  4637.2     .05       0
Bank Sta=4614.2,5224.7
XS Rating Curve= 0 ,0
Exp/Cntr=0.3,0.1

Type RM Length L Ch R = 1 ,33654   ,84,84,84
BEGIN DESCRIPTION:
MITCHELL BRANCH 42.0
END DESCRIPTION:
XS GIS Cut Line= 3
      3651714.69     10708009.61      3651128.47     10707953.58
      3650614.54     10707940.17
#Sta/Elev= 30
  4411.1  330.72  4446.3  327.92  4454.4  326.19  4466.4  325.86  4476.5  324.24
  4537.8  319.63  4562.3  317.76  4636.8  316.71  4657.3  317.24    4665  316.45
  4670.1  317.51  4687.4   317.6  4848.2  317.78  4875.6  316.42  4880.7  317.81
  4888.4  317.83    5033  317.63  5098.9  316.76  5128.9  317.74  5155.9  312.39
  5158.7  311.89  5161.9  312.39  5188.9  315.77  5198.9  321.46  5218.9  324.59
  5248.9  324.52  5317.8   327.6    5419  328.22    5449  328.11  5514.1  325.04
#Mann= 6 ,-1 , 0
  4411.1     .05       0  4537.8     .16       0  4636.8     .12       0
    5033     .05       0  5155.9     .07       0  5161.9     .05       0
Bank Sta=4888.4,5128.9
XS Rating Curve= 0 ,0
Exp/Cntr=0.3,0.1

Type RM Length L Ch R = 1 ,33570   ,95,95,95
BEGIN DESCRIPTION:
Mapping XS 7415a289
END DESCRIPTION:
XS GIS Cut Line= 2
      3651768.27     10707892.04      3650609.43     10707852.98
#Sta/Elev= 30
  4353.4  332.31  4382.1  332.53  4528.8  321.59    4557  320.77  4632.2  313.48
  4682.3  305.49  4726.6  304.31  4812.3  304.61  4850.5  303.12  4862.4  304.34
  4882.4   299.8  4902.4   302.5  4924.4  302.64  4942.4  303.62  4972.4  301.87
  4979.4  298.51  4982.2  298.01  4985.4  298.51  5002.4  301.18  5023.3  301.41
  5052.5  303.03  5068.4  305.36  5082.5  306.41  5122.5  303.22  5142.5  304.92
  5162.5  309.73  5182.5  316.78  5192.5  322.68  5372.6   327.4  5512.9  323.42
#Mann= 8 ,-1 , 0
  4353.4     .16       0  4528.8     .05       0  4726.6     .12       0
  4924.4     .16       0  4979.4     .07       0  4985.4     .16       0
  5023.3     .08       0  5068.4     .05       0
Bank Sta=4942.4,5052.5
XS Rating Curve= 0 ,0
Exp/Cntr=0.3,0.1

Type RM Length L Ch R = 1 ,33475   ,166,166,166
BEGIN DESCRIPTION:
Mapping XS a3c91b5d
END DESCRIPTION:
XS GIS Cut Line= 2
      3651778.16     10707797.28      3650658.41     10707769.06
#Sta/Elev= 30
  4314.1   331.9  4372.7   329.7  4397.3  330.05  4482.7  326.22  4562.7  318.66
  4652.8  307.28  4742.8  304.39  4790.9  304.48  4802.8  303.19  4891.3  304.13
  4892.8  304.07  4902.8  300.03  4912.8  299.22  4952.9  302.11  4962.9   301.5
  4972.9  299.15  5002.9  296.89  5049.9  296.07  5052.6  295.57  5055.9  296.07
  5072.9  296.42  5082.9  300.03  5092.9  311.88  5112.9  316.73  5122.9   316.4
  5142.9  319.15  5222.9  323.32    5313  325.66  5385.9  324.05  5434.2  321.74
#Mann= 5 ,-1 , 0
  4314.1     .05       0  4891.3     .08       0  5049.9     .07       0
  5055.9     .08       0  5385.9     .05       0
Bank Sta=4892.8,5092.9
XS Rating Curve= 0 ,0
Exp/Cntr=0.3,0.1

Type RM Length L Ch R = 1 ,33309   ,192,192,192
BEGIN DESCRIPTION:
Mapping XS a632ebc9
END DESCRIPTION:
XS GIS Cut Line= 2
      3651726.09      10707643.2      3650654.36     10707608.48
#Sta/Elev= 30
  4400.7  330.24  4487.2  328.92  4687.3  306.98    4821  303.19  4837.4  303.14
  4867.4  300.11  4897.4  300.35  4919.9  302.11  4927.5  303.04  4937.5  301.98
  4947.5  299.34  4954.7  298.75  4959.7  296.49  4977.5  297.27  4994.5  293.73
  4997.2  293.23  5000.5  293.73  5007.5  294.01  5017.5  300.56  5027.5  302.62
  5097.6  310.96  5147.6  314.46  5216.6  317.34  5257.6  319.01  5264.3  320.93
  5347.7  317.99  5397.7  313.07  5427.7  313.58  5447.7   311.8    5473  314.67
#Mann= 6 ,-1 , 0
  4400.7     .08       0    4821     .16       0  4919.9     .08       0
  4994.5     .07       0  5000.5     .08       0  5216.6     .05       0
Bank Sta=4937.5,5027.5
XS Rating Curve= 0 ,0
Exp/Cntr=0.3,0.1

Type RM Length L Ch R = 1 ,33117   ,387,387,387
BEGIN DESCRIPTION:
MITCHELL BRANCH 41.0
END DESCRIPTION:
XS GIS Cut Line= 2
      3651598.98     10707583.88      3650809.05     10707431.97
#Sta/Elev= 30
  4634.7  323.08  4654.4  319.27  4674.8  317.15  4827.5  304.17    4929  302.64
  4950.1  302.64  4970.1  298.36  4987.5  289.35  4990.2  288.85  4993.5  289.35
  5002.1  290.39  5010.8  301.01    5021  302.22    5029  302.72  5041.4  303.67
  5100.9  302.68  5112.7  303.99    5133  302.65  5143.2  299.68  5152.8  298.56
  5163.8  299.18    5184  303.27  5261.8  306.42  5298.1  306.56  5370.7  304.24
  5397.8  305.26    5408  308.04  5417.6  308.55  5422.7  307.45  5439.1  309.76
#Mann= 7 ,-1 , 0
  4634.7     .05       0    4929     .16       0  4987.5     .07       0
  4993.5     .16       0    5029     .12       0  5163.8     .16       0
  5298.1     .12       0
#XS Ineff= 2 , 0
                         5110.16           304.1
Permanent Ineff=
       F       F
Bank Sta=4950.1,5021
XS Rating Curve= 0 ,0
Exp/Cntr=0.3,0.1

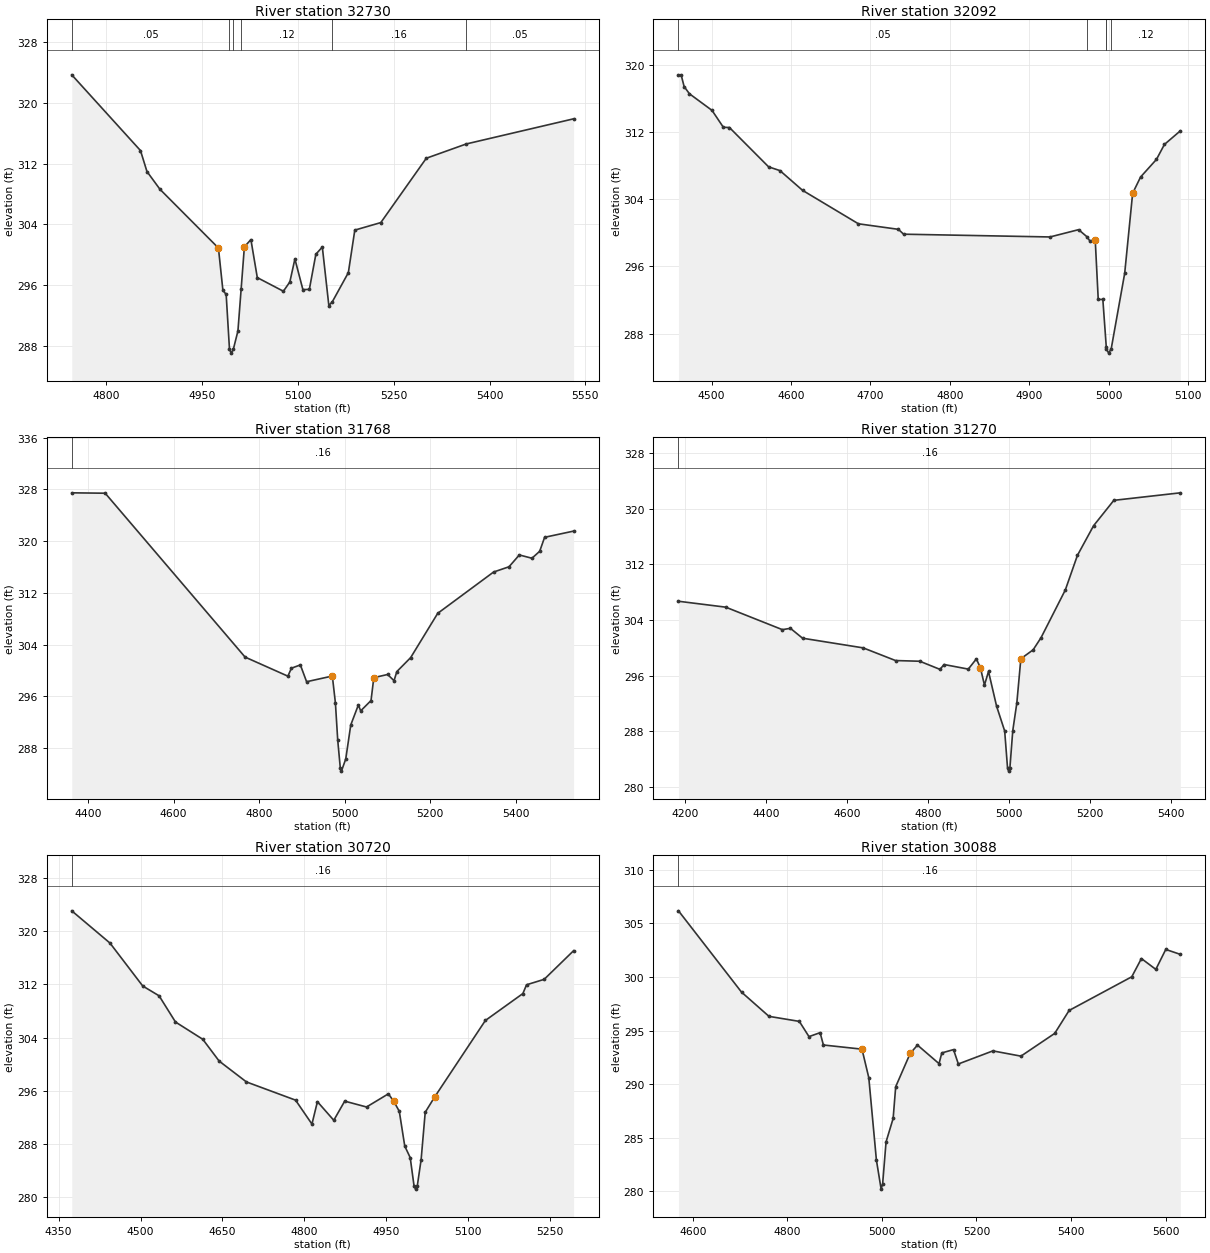
Type RM Length L Ch R = 1 ,32730   ,638,638,638
BEGIN DESCRIPTION:
MITCHELL BRANCH 40.0
END DESCRIPTION:
XS GIS Cut Line= 2
      3651585.38     10707197.28      3650812.81     10707058.71
#Sta/Elev= 30
  4746.6  323.65  4854.1   313.7  4864.2  310.95  4884.5  308.62    4976   300.9
    4983  295.34  4988.1   294.8  4993.3  287.59    4996  287.09  4999.3  287.59
  5006.5     290  5011.5  295.48  5016.6  301.06  5026.8     302  5036.8  297.01
  5077.6  295.22  5087.7  296.44  5095.6  299.46  5108.1  295.44  5118.2  295.46
  5128.4  300.08  5138.5  301.03  5148.7  293.34  5154.1  293.83  5179.2  297.66
  5189.3  303.25    5230  304.24  5301.1  312.69  5363.7  314.57  5531.5  317.87
#Mann= 6 ,-1 , 0
  4746.6     .05       0  4993.3     .03       0  4999.3     .05       0
  5011.5     .12       0  5154.1     .16       0  5363.7     .05       0
Bank Sta=4976,5016.6
XS Rating Curve= 0 ,0
Exp/Cntr=0.3,0.1

Type RM Length L Ch R = 1 ,32092   ,324,324,324
BEGIN DESCRIPTION:
MITCHELL BRANCH 39.0
END DESCRIPTION:
XS GIS Cut Line= 3
      3651649.62      10707060.2      3651249.61     10706710.19
      3651149.63     10706710.19
#Sta/Elev= 30
  4458.4  318.84  4461.7  318.84  4465.5  317.44  4472.2  316.58  4500.6   314.6
  4514.9  312.58  4522.5  312.56  4571.8  307.87  4586.1  307.42  4614.5  305.07
  4684.8  301.08  4735.1  300.42  4741.7  299.84  4925.9  299.51  4961.9  300.38
  4972.2  299.55  4976.2  299.02  4982.8  299.19  4986.6  292.06  4992.4  292.06
  4996.7  286.42  4996.9  286.16  4999.7  285.66  5002.9  286.16  5019.9  295.18
  5029.9  304.72  5039.9  306.66  5059.9  308.76  5069.9  310.54  5089.9  312.16
#Mann= 5 ,-1 , 0
  4458.4     .05       0  4972.2     .16       0  4996.7     .12       0
  4996.9     .07       0  5002.9     .12       0
Bank Sta=4982.8,5029.9
XS Rating Curve= 0 ,0
Exp/Cntr=0.3,0.1

Type RM Length L Ch R = 1 ,31768   ,498,498,498
BEGIN DESCRIPTION:
MITCHELL BRANCH 38.0
END DESCRIPTION:
XS GIS Cut Line= 3
      3651894.37     10707063.95      3651547.17     10706599.57
      3650995.98     10706378.22
#Sta/Elev= 30
  4361.7  327.48  4439.9  327.42  4767.1  302.07  4867.2  299.12  4875.5  300.35
  4896.4  300.86    4911  298.26  4971.2  299.14  4978.4  294.97  4983.8  289.23
  4989.8  284.93  4992.5  284.43  5002.6  286.32  5014.3  291.57  5032.1  294.67
  5037.5  293.75  5061.7  295.35  5068.2  298.89  5100.5  299.38  5115.5  298.42
  5122.1  299.83  5154.4  301.99  5217.7  308.84  5348.4  315.23  5384.4  316.04
  5408.6  317.87  5438.1  317.36  5456.2  318.44  5467.7   320.6  5535.5  321.56
#Mann= 1 ,-1 , 0
  4361.7     .16       0
Bank Sta=4971.2,5068.2
XS Rating Curve= 0 ,0
Exp/Cntr=0.3,0.1

Type RM Length L Ch R = 1 ,31270   ,550,550,550
BEGIN DESCRIPTION:
MITCHELL BRANCH 37.0
END DESCRIPTION:
XS GIS Cut Line= 2
      3652176.55     10706122.14      3650935.15     10706126.48
#Sta/Elev= 30
  4182.7  306.71  4299.6  305.86  4439.6  302.63  4459.6  302.82  4489.6   301.4
  4639.6  300.01  4719.6  298.19  4779.6  298.09  4829.6  296.92  4839.6  297.62
  4899.6  296.96  4919.6  298.43  4929.6  297.14  4939.6  294.66  4949.6  296.62
  4969.6  291.63  4989.6  288.07  4996.6   282.8  4999.4   282.3  5002.6   282.8
  5009.6  288.11  5019.6  292.06  5029.6  298.45    5060  299.73  5079.6  301.48
  5139.6  308.33  5169.6  313.31  5209.6  317.57  5259.6  321.21  5424.1  322.29
#Mann= 1 ,-1 , 0
  4182.7     .16       0
Bank Sta=4929.6,5029.6
XS Rating Curve= 0 ,0
Exp/Cntr=0.3,0.1

Type RM Length L Ch R = 1 ,30720   ,632,632,632
BEGIN DESCRIPTION:
MITCHELL BRANCH 36.0
END DESCRIPTION:
XS GIS Cut Line= 3
      3651999.63     10705610.19      3651349.61     10705610.19
      3651099.59      10705710.2
#Sta/Elev= 30
    4374  323.08    4444  318.23    4504  311.77    4534  310.29    4564  306.35
    4614  303.75    4644  300.47    4694  297.33    4784  294.59    4814  290.99
    4824  294.36    4854  291.56    4874  294.44    4914  293.56    4954  295.54
    4964   294.4    4974  292.91    4984  287.68    4994  285.94    5001   281.7
  5003.8   281.2    5007   281.7    5014  285.64  5021.5  292.77  5038.8  295.07
  5131.7  306.58  5200.4  310.63  5207.1  311.95  5239.4  312.77  5293.3  317.08
#Mann= 1 ,-1 , 0
    4374     .16       0
Bank Sta=4964,5038.8
XS Rating Curve= 0 ,0
Exp/Cntr=0.3,0.1

Type RM Length L Ch R = 1 ,30088   ,696,696,696
BEGIN DESCRIPTION:
MITCHELL BRANCH 35.0
END DESCRIPTION:
XS GIS Cut Line= 2
      3651920.43     10704998.01      3650878.82     10705201.99
#Sta/Elev= 30
  4569.7  306.16    4703  298.58  4761.1  296.32  4825.3  295.85  4845.7  294.43
  4869.2   294.8  4876.2  293.65  4957.8  293.26  4972.2   290.6  4988.3  282.92
  4998.3  280.21  5001.5  280.71  5008.7  284.61  5023.7   286.8  5029.1  289.76
  5059.7  292.86  5075.2  293.64  5120.8  291.91  5126.6  292.91  5151.4  293.22
  5161.6  291.88  5234.7   293.1    5294  292.61  5365.4  294.73  5395.9  296.87
  5528.4  300.01  5548.8  301.71  5579.3   300.7  5600.3  302.56  5631.1   302.1
#Mann= 1 ,-1 , 0
  4569.7     .16       0
Bank Sta=4957.8,5059.7
XS Rating Curve= 0 ,0
Exp/Cntr=0.3,0.1

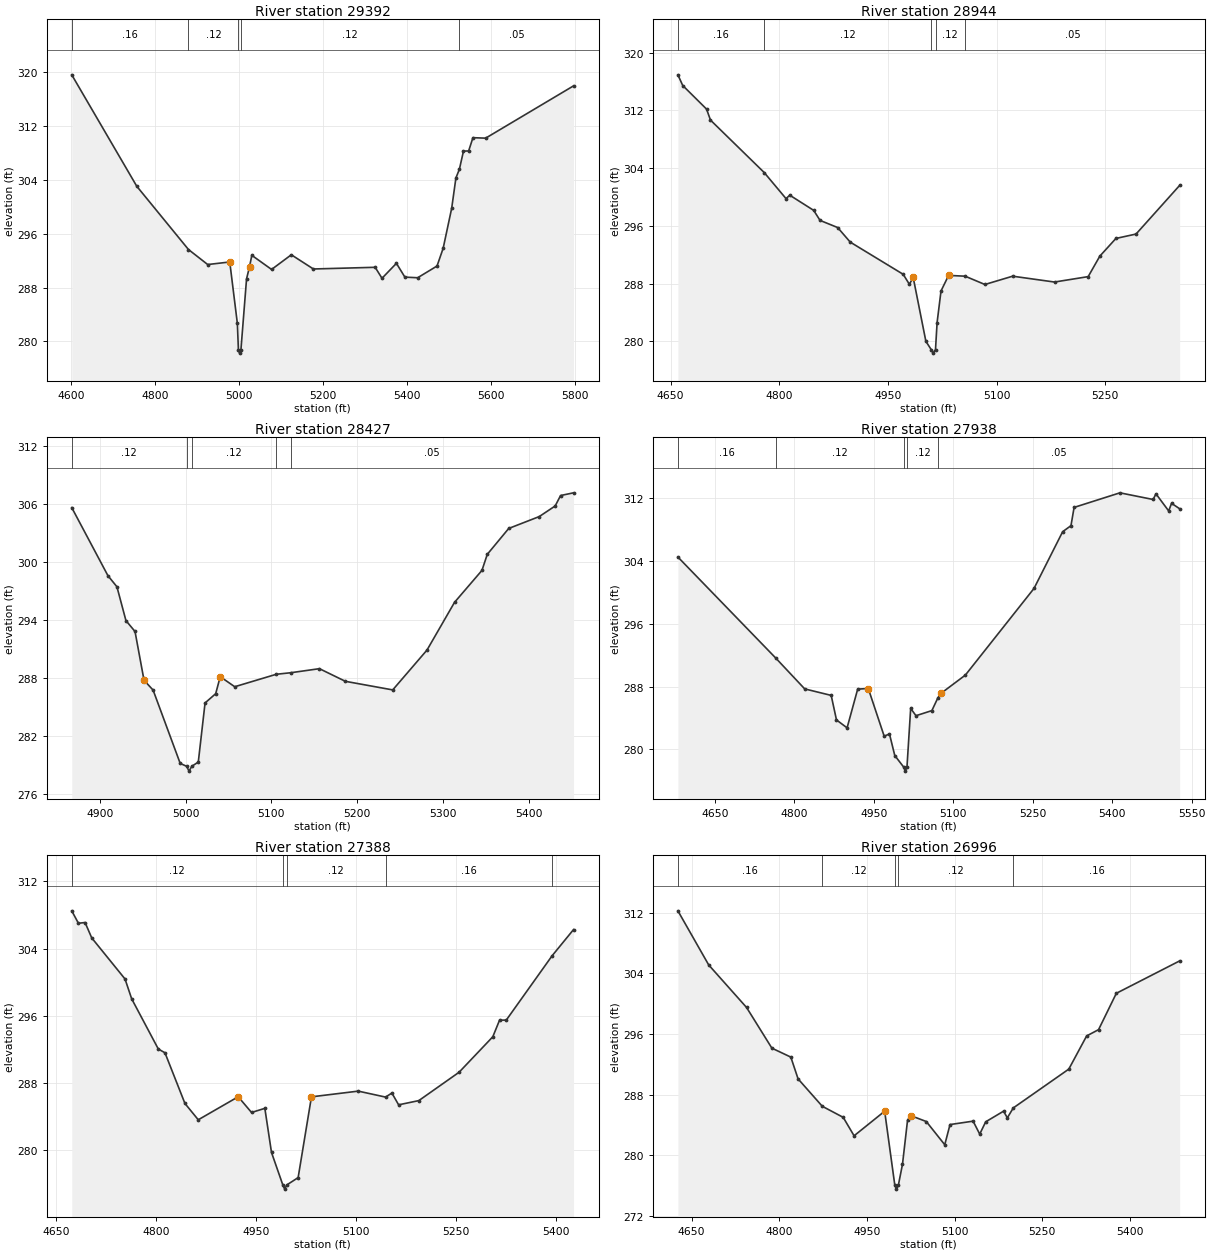
Type RM Length L Ch R = 1 ,29392   ,448,448,448
BEGIN DESCRIPTION:
MITCHELL BRANCH 34.0
END DESCRIPTION:
XS GIS Cut Line= 3
      3651811.81     10704417.07      3651263.29     10704653.35
       3650672.9     10704744.93
#Sta/Elev= 30
  4601.4  319.57  4756.2  303.03  4879.3  293.64  4925.1  291.41  4977.6  291.79
  4995.7  282.67  4998.2  278.76  5000.9  278.26  5004.2  278.76  5017.6  289.29
  5024.7  291.08  5030.1  292.78  5077.2  290.68  5124.2  292.86  5176.7  290.75
  5323.8     291  5340.1  289.37  5374.4  291.59  5394.6  289.54    5425  289.45
  5471.1  291.19  5485.7  293.82    5506  299.76  5516.1  304.27  5524.3  305.54
  5534.1  308.25  5546.4  308.27  5556.6  310.24  5586.9  310.17  5796.1  317.93
#Mann= 5 ,-1 , 0
  4601.4     .16       0  4879.3     .12       0  4998.2     .07       0
  5004.2     .12       0  5524.3     .05       0
Bank Sta=4977.6,5024.7
XS Rating Curve= 0 ,0
Exp/Cntr=0.3,0.1

Type RM Length L Ch R = 1 ,28944   ,517,517,517
BEGIN DESCRIPTION:
MITCHELL BRANCH 33.0
END DESCRIPTION:
XS GIS Cut Line= 2
      3651577.55     10704082.21      3650914.09     10704281.68
#Sta/Elev= 30
    4660  316.93  4666.7  315.45  4699.6  312.18    4705  310.66  4779.2  303.39
  4809.3  299.78  4814.5  300.25  4847.5  298.15  4856.3  296.76  4880.6  295.77
    4898  293.75  4971.1  289.29  4979.6  287.91  4984.9  288.85  5002.4  280.01
  5009.7  278.87  5012.4  278.37  5015.7  278.87  5017.9  282.61  5023.3  286.98
  5033.8  289.14  5056.6  289.03  5083.9  287.88  5122.2  289.03    5180  288.22
  5226.5  288.97  5242.6  291.81  5264.8  294.26  5292.6  294.87  5352.8  301.61
#Mann= 5 ,-1 , 0
    4660     .16       0  4779.2     .12       0  5009.7     .07       0
  5015.7     .12       0  5056.6     .05       0
Bank Sta=4984.9,5033.8
XS Rating Curve= 0 ,0
Exp/Cntr=0.3,0.1

Type RM Length L Ch R = 1 ,28427   ,489,489,489
BEGIN DESCRIPTION:
MITCHELL BRANCH 32.0
END DESCRIPTION:
XS GIS Cut Line= 3
       3651399.6     10703810.18      3651249.61     10703760.19
      3650849.61     10703910.19
#Sta/Elev= 30
  4867.2  305.66  4909.4  298.61  4919.9  297.46  4930.4  293.96    4941  292.83
  4951.5  287.78  4962.1  286.76  4993.7  279.17  5001.2  278.87    5004  278.37
  5007.2  278.87  5014.8  279.31  5022.7  285.43  5035.1  286.39  5040.4  288.15
  5057.3  287.11  5105.8   288.4  5122.7  288.56  5156.1  288.98  5186.4  287.67
  5241.6  286.78  5281.6  290.91  5313.7  295.85  5345.7  299.16  5351.9  300.82
  5376.9   303.5  5412.5  304.73  5431.1  305.83  5437.4  306.91  5452.5  307.19
#Mann= 5 ,-1 , 0
  4867.2     .12       0  5001.2     .07       0  5007.2     .12       0
  5105.8     .07       0  5122.7     .05       0
Bank Sta=4951.5,5040.4
XS Rating Curve= 0 ,0
Exp/Cntr=0.3,0.1

Type RM Length L Ch R = 1 ,27938   ,550,550,550
BEGIN DESCRIPTION:
MITCHELL BRANCH 31.0
END DESCRIPTION:
XS GIS Cut Line= 3
      3651448.86     10703460.17      3650949.71     10703453.66
      3650535.23     10703622.93
#Sta/Elev= 30
  4580.5  304.53  4764.8  291.67  4819.8  287.71  4869.8  286.88  4879.8  283.75
  4899.8  282.74  4919.8  287.68  4939.8  287.76  4969.8  281.68  4979.8  281.96
  4989.8  279.21  5006.8  277.72  5009.5  277.22  5012.8  277.72  5019.8  285.22
  5029.8  284.29  5059.8  284.94  5071.1  286.56  5077.2  287.15    5123  289.47
  5252.6  300.53  5306.6  307.76  5322.3  308.53  5328.2  310.86  5414.7  312.72
  5477.3  311.87  5482.7  312.59  5506.7  310.41  5512.1  311.38  5527.4  310.69
#Mann= 5 ,-1 , 0
  4580.5     .16       0  4764.8     .12       0  5006.8     .07       0
  5012.8     .12       0  5071.1     .05       0
Bank Sta=4939.8,5077.2
XS Rating Curve= 0 ,0
Exp/Cntr=0.3,0.1

Type RM Length L Ch R = 1 ,27388   ,392,392,392
BEGIN DESCRIPTION:
MITCHELL BRANCH 30.0
END DESCRIPTION:
XS GIS Cut Line= 3
      3651399.63     10703060.19      3650999.61     10703060.19
      3650649.58     10703010.18
#Sta/Elev= 30
  4673.3  308.49  4683.3  307.01  4693.3   307.1  4703.3  305.27  4753.3  300.38
  4763.3  298.02  4803.3  292.05  4813.3   291.6  4843.3  285.57  4863.3  283.63
  4923.3  286.37  4943.3   284.5  4963.3  284.99  4973.3  279.74  4990.3  275.88
  4993.1  275.38  4996.3  275.88  5013.3  276.75  5033.3  286.36  5103.6  287.04
  5144.6  286.33  5154.1  286.81  5164.2  285.41  5194.5  285.91  5255.1  289.29
  5305.7  293.51  5315.8  295.48  5325.9  295.49  5394.7  303.14  5426.9  306.26
#Mann= 5 ,-1 , 0
  4673.3     .12       0  4990.3     .07       0  4996.3     .12       0
  5144.6     .16       0  5394.7     .12       0
Bank Sta=4923.3,5033.3
XS Rating Curve= 0 ,0
Exp/Cntr=0.3,0.1

Type RM Length L Ch R = 1 ,26996   ,379,379,379
BEGIN DESCRIPTION:
MITCHELL BRANCH 29.0
END DESCRIPTION:
XS GIS Cut Line= 3
       3651518.3     10702921.98       3651216.1     10702797.55
      3650693.07     10702703.08
#Sta/Elev= 30
  4626.6  312.23  4679.3   305.1  4744.1  299.49  4787.4  294.13  4819.8  292.95
  4832.2  290.08  4873.6  286.47  4909.4  285.01    4928  282.58  4980.3  285.82
  4997.7  276.05  5000.4  275.55  5003.7  276.05  5010.8  278.83  5019.4   284.6
  5024.5  285.25  5051.5  284.46  5083.1   281.4  5092.1  284.06  5131.6  284.51
  5142.9   282.8  5153.1  284.42  5183.6  285.82  5190.2  284.95  5200.3  286.25
  5295.3  291.37  5325.8  295.74  5346.2  296.57  5376.6  301.36  5484.9  305.63
#Mann= 5 ,-1 , 0
  4626.6     .16       0  4873.6     .12       0  4997.7     .07       0
  5003.7     .12       0  5200.3     .16       0
Bank Sta=4980.3,5024.5
XS Rating Curve= 0 ,0
Exp/Cntr=0.3,0.1