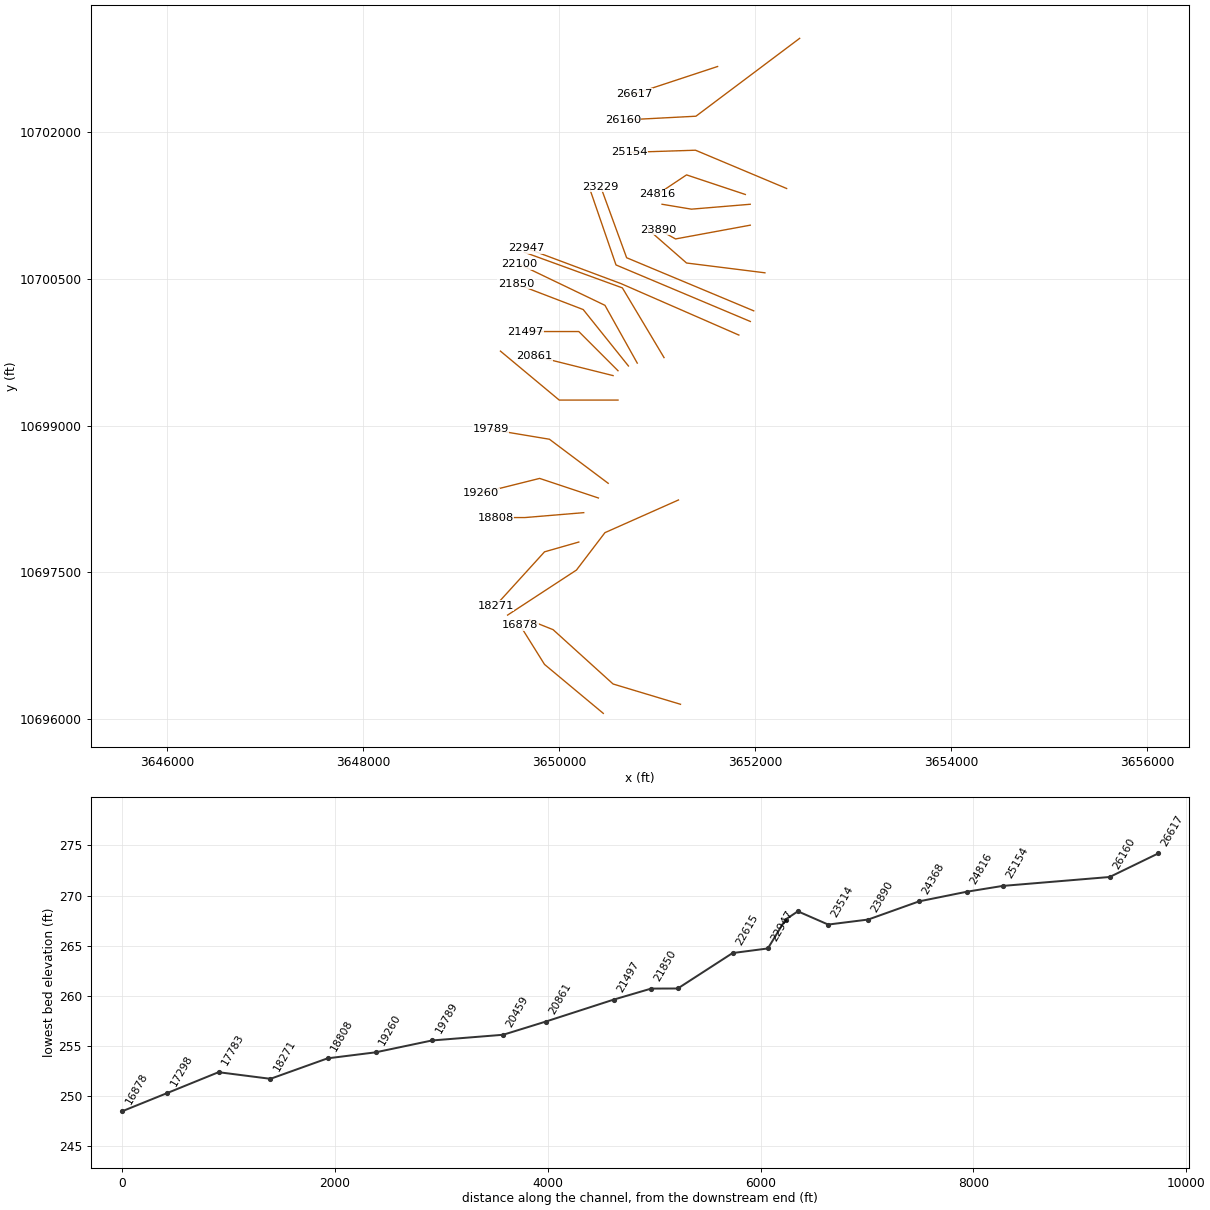
HEC-RAS study MITCHELL BRANCH.prj: MITCHELL BRANCH Base Level Engineering

--- MITCHELL BRANCH.g01 (geometry) --- (continued)

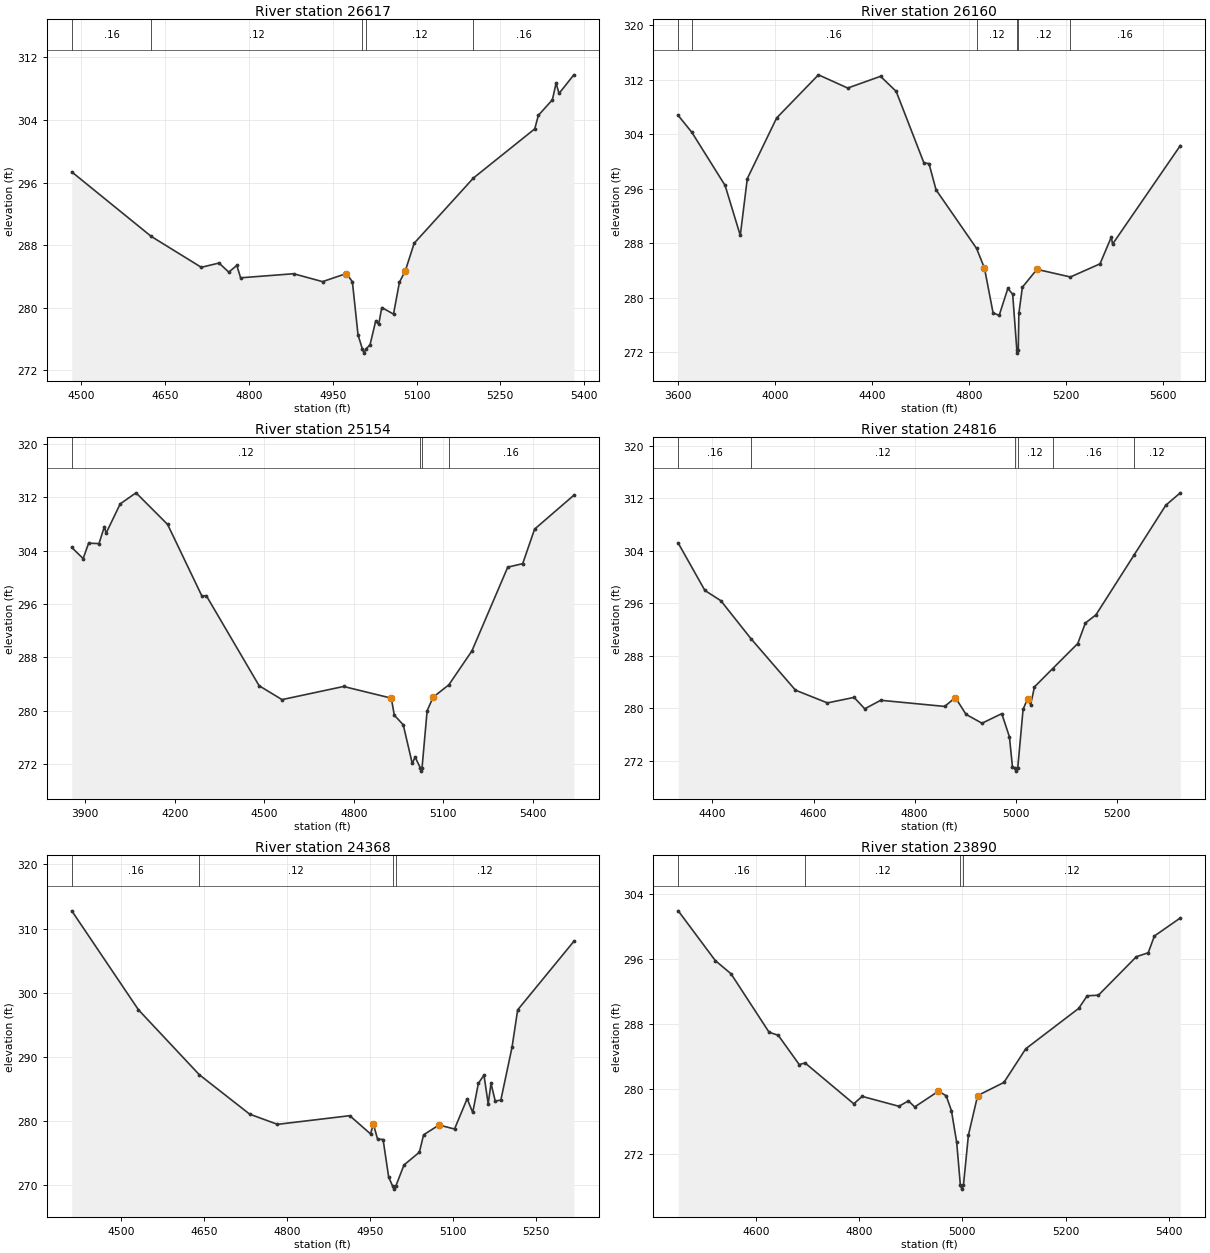
Type RM Length L Ch R = 1 ,26617   ,457,457,457
BEGIN DESCRIPTION:
Mapping XS 0a4f549e
END DESCRIPTION:
XS GIS Cut Line= 2
      3651616.58     10702667.26      3650763.14     10702385.67
#Sta/Elev= 30
  4482.9  297.37  4625.2  289.12  4714.8  285.17  4746.5  285.72    4764  284.55
  4778.3  285.42  4785.1  283.83  4879.9  284.35  4931.8  283.34  4974.6  284.38
  4985.2  283.32  4995.3  276.53  5003.2   274.7    5006   274.2  5009.2   274.7
  5016.8  275.27    5027  278.33  5032.3  277.89  5037.8  280.03  5058.8  279.19
  5069.4  283.26  5079.9  284.72  5095.8  288.25  5201.9  296.59  5311.6  302.87
  5318.1   304.6  5343.2  306.59  5349.8  308.72  5355.1   307.4  5381.6  309.78
#Mann= 5 ,-1 , 0
  4482.9     .16       0  4625.2     .12       0  5003.2     .07       0
  5009.2     .12       0  5201.9     .16       0
Bank Sta=4974.6,5079.9
XS Rating Curve= 0 ,0
Exp/Cntr=0.3,0.1

Type RM Length L Ch R = 1 ,26160   ,1006,1006,1006
BEGIN DESCRIPTION:
MITCHELL BRANCH 28.0
END DESCRIPTION:
XS GIS Cut Line= 3
      3652454.41     10702954.95      3651395.26     10702159.46
      3650648.69      10702120.4
#Sta/Elev= 30
  3599.9  306.74  3655.9  304.28  3793.3  296.47    3856  289.13  3884.9  297.47
  4006.1  306.38  4178.6  312.71  4299.4  310.77  4434.8  312.49  4499.4  310.28
    4614  299.77  4634.8  299.68  4663.9  295.83  4831.3  287.22  4863.9  284.32
  4899.3  277.76  4924.5  277.39  4960.2  281.34  4980.2  280.51  4997.3  272.35
    5000  271.85  5003.3  272.35  5005.8  277.69  5020.3  281.53  5080.4  284.15
  5218.6  283.03  5340.7  284.96  5387.4   288.9  5392.4  287.85  5672.1  302.32
#Mann= 6 ,-1 , 0
  3599.9     .12       0  3655.9     .16       0  4831.3     .12       0
  4997.3     .07       0  5003.3     .12       0  5218.6     .16       0
Bank Sta=4863.9,5080.4
XS Rating Curve= 0 ,0
Exp/Cntr=0.3,0.1

Type RM Length L Ch R = 1 ,25154   ,338,338,338
BEGIN DESCRIPTION:
MITCHELL BRANCH 27.0
END DESCRIPTION:
XS GIS Cut Line= 3
       3652321.6      10701421.1      3651390.92     10701812.24
       3650718.2     10701790.54
#Sta/Elev= 30
  3854.9  304.49  3893.1  302.82  3911.3  305.13  3946.1  305.07  3964.4  307.63
  3969.8  306.62  4017.3  311.03  4070.3  312.68  4176.1  307.94    4291  297.21
  4305.7  297.27  4482.8  283.76  4559.5  281.68  4765.8  283.65  4925.8   281.9
  4935.8  279.35  4965.8   277.9  4995.8  272.14  5005.8  273.06  5022.8  271.46
  5025.6  270.96  5028.8  271.46  5045.8  280.01  5065.8  282.04  5118.6   283.9
  5195.9  288.98    5316  301.54    5366  302.06    5406  307.24  5537.5  312.32
#Mann= 4 ,-1 , 0
  3854.9     .12       0  5022.8     .07       0  5028.8     .12       0
  5118.6     .16       0
Bank Sta=4925.8,5065.8
XS Rating Curve= 0 ,0
Exp/Cntr=0.3,0.1

Type RM Length L Ch R = 1 ,24816   ,448,448,448
BEGIN DESCRIPTION:
MITCHELL BRANCH 26.0
END DESCRIPTION:
XS GIS Cut Line= 3
      3651899.58      10701360.2      3651299.61     10701560.19
      3650999.59     10701360.17
#Sta/Elev= 30
  4332.4  305.17  4385.1  297.95  4416.7  296.38  4476.1   290.6  4564.3  282.73
  4627.5  280.79  4680.2  281.63  4701.3  279.89  4732.9  281.19  4859.4  280.25
  4880.5  281.61  4901.6  279.04  4933.2  277.69  4972.3  279.15  4987.4  275.62
  4993.4  271.06  4997.9  270.88  5000.6  270.38  5003.9  270.88  5014.4  279.79
  5023.4  281.43  5029.4  280.51  5036.9  283.23  5072.9  286.02  5122.6  289.85
  5137.6  292.97  5158.6  294.23  5234.5  303.42  5296.8  310.96  5325.4  312.84
#Mann= 6 ,-1 , 0
  4332.4     .16       0  4476.1     .12       0  4997.9     .07       0
  5003.9     .12       0  5072.9     .16       0  5234.5     .12       0
Bank Sta=4880.5,5023.4
XS Rating Curve= 0 ,0
Exp/Cntr=0.3,0.1

Type RM Length L Ch R = 1 ,24368   ,478,478,478
BEGIN DESCRIPTION:
MITCHELL BRANCH 25.0
END DESCRIPTION:
XS GIS Cut Line= 3
      3651949.59     10701260.19      3651349.61     10701210.19
      3651049.61     10701260.19
#Sta/Elev= 30
  4411.6  312.77    4532  297.35  4641.8  287.24  4732.7   281.1  4782.9  279.51
  4913.3  280.86  4950.9  278.02    4956  279.54  4963.5  277.22  4973.5  277.15
  4983.6  271.29  4990.6  269.92  4993.3  269.42  4996.6  269.92  5011.2  273.18
    5039  275.17  5046.6  277.88  5074.5  279.41  5102.4  278.78  5125.2   283.5
  5135.3  281.36  5145.5   285.9  5155.6  287.18  5163.2   282.7  5168.3  285.89
  5175.9  283.15    5186  283.28  5206.3  291.55  5216.4  297.34  5317.8  308.02
#Mann= 4 ,-1 , 0
  4411.6     .16       0  4641.8     .12       0  4990.6     .07       0
  4996.6     .12       0
Bank Sta=4956,5074.5
XS Rating Curve= 0 ,0
Exp/Cntr=0.3,0.1

Type RM Length L Ch R = 1 ,23890   ,376,376,376
BEGIN DESCRIPTION:
MITCHELL BRANCH 24.0
END DESCRIPTION:
XS GIS Cut Line= 3
      3651950.23     10701046.61      3651187.18     10700905.98
      3651015.34     10701002.32
#Sta/Elev= 30
  4449.3  301.91  4521.1  295.78  4551.6  294.15  4625.3  286.95  4643.1  286.57
  4683.8  282.96  4695.1  283.16  4789.4  278.13  4805.8  279.04    4877  277.82
  4895.4  278.49  4907.5  277.74  4953.5  279.68  4968.5  279.12  4978.7  277.28
  4988.9  273.36    4996  268.11  4998.8  267.61    5002  268.11  5011.6  274.27
  5029.5  279.14  5080.4  280.76  5122.7  284.91  5225.2  289.88  5241.8  291.44
  5263.5  291.51  5337.1  296.26    5360  296.74    5372  298.81  5422.2  301.03
#Mann= 4 ,-1 , 0
  4449.3     .16       0  4695.1     .12       0    4996     .07       0
    5002     .12       0
Bank Sta=4953.5,5029.5
XS Rating Curve= 0 ,0
Exp/Cntr=0.3,0.1

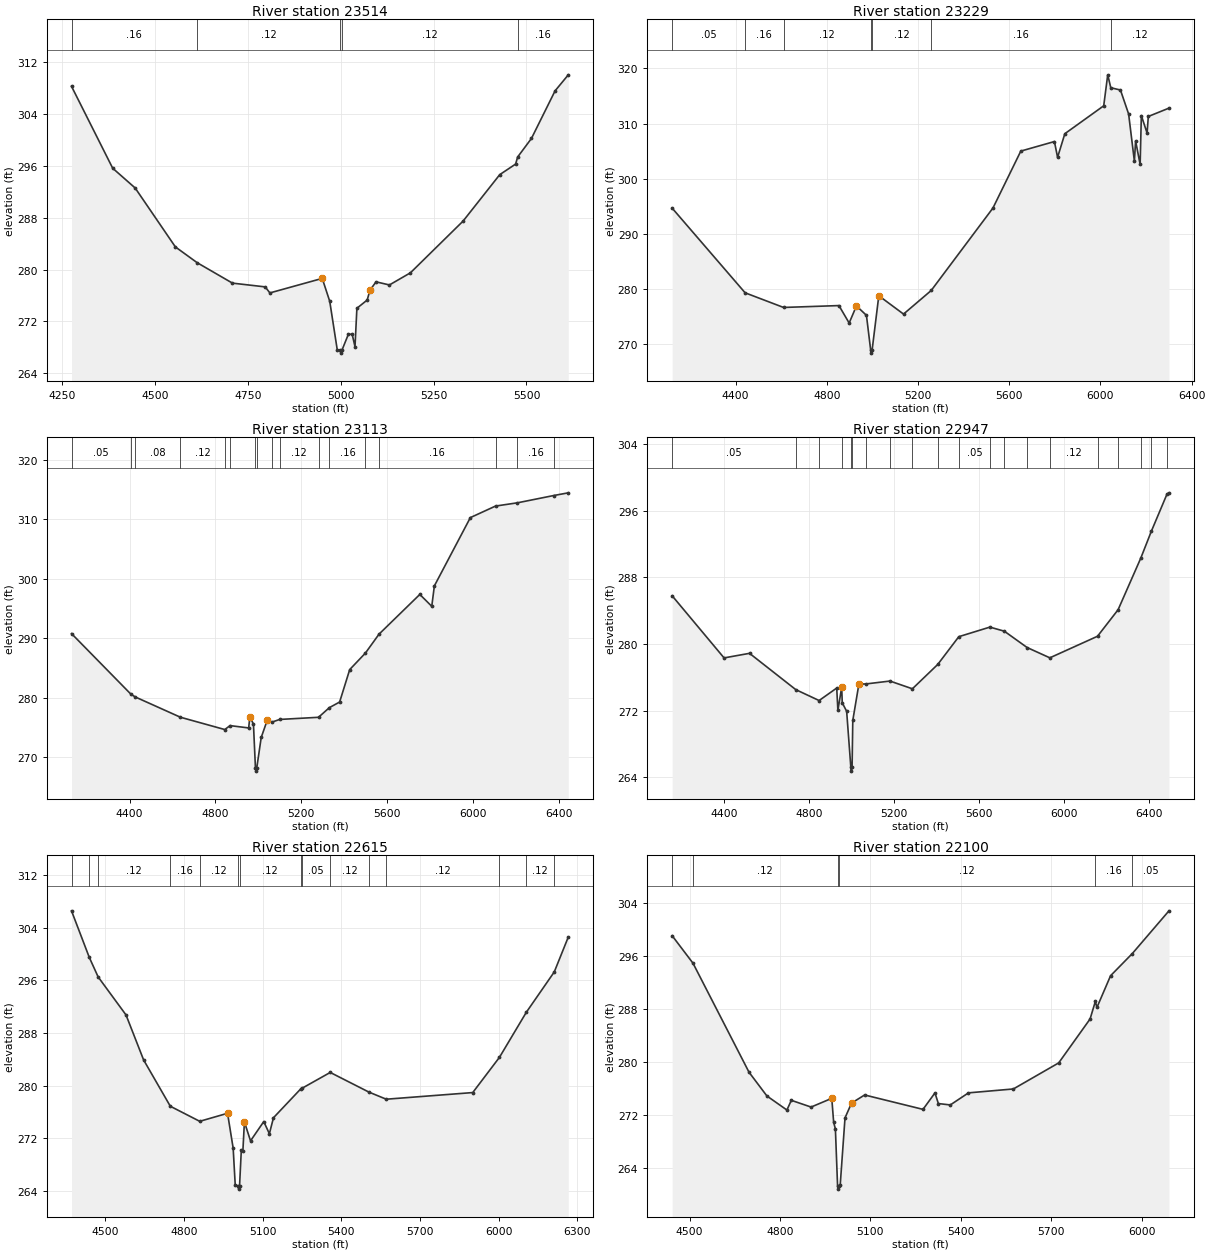
Type RM Length L Ch R = 1 ,23514   ,285,285,285
BEGIN DESCRIPTION:
MITCHELL BRANCH 23.0
END DESCRIPTION:
XS GIS Cut Line= 3
      3652099.64     10700560.18      3651299.61     10700660.19
      3650899.58     10701010.21
#Sta/Elev= 30
  4274.8  308.28  4385.7  295.64  4446.2  292.59  4554.5   283.5    4613  281.07
  4708.2  277.91  4796.4  277.33    4809   276.4    4950  278.64  4970.2   275.1
  4990.4  267.63  4997.4  267.61  5000.2  267.11  5003.4  267.61  5020.6  270.05
  5030.7     270  5038.2   268.1  5043.3  274.03    5071   275.3  5078.5  276.81
  5094.8  278.11  5130.9  277.63  5187.4   279.5  5329.2  287.48    5428  294.65
  5470.7  296.28  5476.2  297.37  5513.4  300.24    5577  307.58  5612.6  310.05
#Mann= 5 ,-1 , 0
  4274.8     .16       0    4613     .12       0  4997.4     .07       0
  5003.4     .12       0  5476.2     .16       0
Bank Sta=4950,5078.5
XS Rating Curve= 0 ,0
Exp/Cntr=0.3,0.1

Type RM Length L Ch R = 1 ,23229   ,116,116,116
BEGIN DESCRIPTION:
Mapping XS 29fd450d
END DESCRIPTION:
XS GIS Cut Line= 3
      3651985.53     10700171.62       3650687.8     10700714.15
      3650423.06     10701438.94
#Sta/Elev= 30
  4122.3  294.68  4442.2  279.35  4610.7   276.7  4853.5  277.04  4898.3  273.88
  4930.3  276.98  4974.1  275.27  4992.8  268.93  4995.6  268.43  4998.8  268.93
  5028.3  278.82  5136.7   275.5    5258  279.77  5528.9  294.71  5650.9  305.01
  5798.3  306.74  5812.1  303.88    5844  308.16  6014.4  313.21    6032  318.82
  6045.4  316.48  6087.8  316.07  6123.6  311.73  6148.9  303.18  6154.2  306.86
  6174.1  302.59  6179.4  311.44  6204.6  308.27  6209.9  311.28  6300.5  312.79
#Mann= 7 ,-1 , 0
  4122.3     .05       0  4442.2     .16       0  4610.7     .12       0
  4992.8     .07       0  4998.8     .12       0    5258     .16       0
  6045.4     .12       0
Bank Sta=4930.3,5028.3
XS Rating Curve= 0 ,0
Exp/Cntr=0.3,0.1

Type RM Length L Ch R = 1 ,23113   ,166,166,166
BEGIN DESCRIPTION:
Mapping XS bd61c042
END DESCRIPTION:
XS GIS Cut Line= 3
       3651950.8     10700063.12      3650579.29     10700640.37
       3650310.2     10701421.58
#Sta/Elev= 30
  4129.5  290.76  4406.8  280.54  4427.3  280.08  4636.9  276.68  4843.4  274.61
  4868.2  275.27  4954.8  274.88  4960.3  276.74  4977.1  275.53  4986.4  268.11
  4989.2  267.61  4992.4  268.11  5013.2  273.27  5042.3  276.28  5061.7  275.84
  5099.5  276.31  5280.1  276.67  5330.9   278.3  5378.5  279.24  5425.5   284.7
  5498.4  287.47  5562.2  290.67  5752.1  297.35  5807.7  295.35  5819.9  298.79
  5987.5  310.28  6104.7  312.22    6207  312.77  6376.4     314  6443.8  314.45
#Mann= 17 ,-1 , 0
  4129.5     .05       0  4406.8     .16       0  4427.3     .08       0
  4636.9     .12       0  4843.4     .05       0  4868.2     .12       0
  4986.4     .07       0  4992.4     .12       0  5061.7     .05       0
  5099.5     .12       0  5280.1     .05       0  5330.9     .16       0
  5498.4     .05       0  5562.2     .16       0  6104.7     .12       0
    6207     .16       0  6376.4     .12       0
Bank Sta=4960.3,5042.3
XS Rating Curve= 0 ,0
Exp/Cntr=0.3,0.1

Type RM Length L Ch R = 1 ,22947   ,332,332,332
BEGIN DESCRIPTION:
MITCHELL BRANCH 22.0
END DESCRIPTION:
XS GIS Cut Line= 3
      3651833.65     10699924.21      3650631.37     10700449.39
       3649667.8     10700809.65
#Sta/Elev= 30
  4154.9  285.79  4399.4  278.33  4519.4  278.88  4737.3  274.52  4847.2  273.21
  4930.2  274.71  4935.7  272.04  4953.6  274.79  4956.3  272.93    4977  271.92
  4996.6  265.23  4999.3  264.73  5002.6  265.23  5005.9  270.82  5034.7  275.19
  5066.9   275.2  5181.1  275.55  5286.7  274.62    5406  277.54  5505.4  280.88
  5651.8  282.03  5719.9  281.54  5827.1  279.58  5934.3  278.34  6158.9  280.93
    6256  284.12  6363.2  290.34  6412.5  293.54  6486.2     298  6495.6  298.16
#Mann= 20 ,-1 , 0
  4154.9     .05       0  4737.3     .08       0  4847.2     .12       0
  4956.3     .08       0  4996.6     .07       0  5002.6     .08       0
  5066.9     .16       0  5181.1     .08       0  5286.7     .12       0
    5406     .08       0  5505.4     .05       0  5651.8     .08       0
  5719.9     .05       0  5827.1     .12       0  5934.3     .12       0
  6158.9     .08       0    6256     .16       0  6363.2     .12       0
  6412.5     .08       0  6486.2     .05       0
Bank Sta=4953.6,5034.7
XS Rating Curve= 0 ,0
Exp/Cntr=0.3,0.1

Type RM Length L Ch R = 1 ,22615   ,515,515,515
BEGIN DESCRIPTION:
MITCHELL BRANCH 21.0
END DESCRIPTION:
XS GIS Cut Line= 3
      3651069.76     10699694.16      3650644.39     10700405.99
      3649643.17     10700770.07
#Sta/Elev= 30
  4371.5  306.58  4439.2  299.51  4473.1  296.53  4579.4  290.75  4646.5  283.91
  4748.3  276.87  4860.5  274.58  4966.6   275.8    4988  270.49  4995.9  264.87
  5006.4  264.77  5009.1  264.27  5012.4  264.77  5019.1  270.22    5025  270.03
  5030.9  274.49  5054.2  271.61  5104.7  274.54  5126.1  272.69  5141.7  275.12
  5246.7  279.55  5251.4  279.62  5358.2  282.01  5505.8  279.02  5571.8  277.94
  5901.7  278.95  6003.4   284.3  6105.9  291.15  6212.7   297.3  6266.1   302.6
#Mann= 15 ,-1 , 0
  4371.5     .12       0  4439.2     .16       0  4473.1     .12       0
  4748.3     .16       0  4860.5     .12       0  5006.4     .07       0
  5012.4     .12       0  5246.7     .08       0  5251.4     .05       0
  5358.2     .12       0  5505.8     .05       0  5571.8     .12       0
  6003.4     .16       0  6105.9     .12       0  6212.7     .05       0
Bank Sta=4966.6,5030.9
XS Rating Curve= 0 ,0
Exp/Cntr=0.3,0.1

Type RM Length L Ch R = 1 ,22100   ,250,250,250
BEGIN DESCRIPTION:
MITCHELL BRANCH 20.0
END DESCRIPTION:
XS GIS Cut Line= 3
      3650796.29     10699637.79      3650466.44     10700228.04
      3649589.74     10700649.03
#Sta/Elev= 30
  4442.2  299.12  4511.4  294.95  4697.2  278.45  4756.6  274.85    4823  272.72
  4837.6  274.19  4903.2  273.17  4971.9  274.49  4978.1  270.87  4983.9  269.85
  4991.1  261.24  4993.9  260.74  4997.1  261.24  4999.8  261.31  5015.8  271.53
  5037.5  273.77  5080.9     275  5274.6  272.82  5314.3  275.31  5325.6   273.7
  5365.2  273.49  5425.5  275.32  5574.5  275.91    5725  279.86  5829.1  286.51
  5846.6  289.17  5851.8  288.25  5897.1  293.06  5969.3  296.42  6090.9  302.89
#Mann= 6 ,-1 , 0
  4442.2     .16       0  4511.4     .12       0  4991.1     .07       0
  4997.1     .12       0  5846.6     .16       0  5969.3     .05       0
Bank Sta=4971.9,5037.5
XS Rating Curve= 0 ,0
Exp/Cntr=0.3,0.1

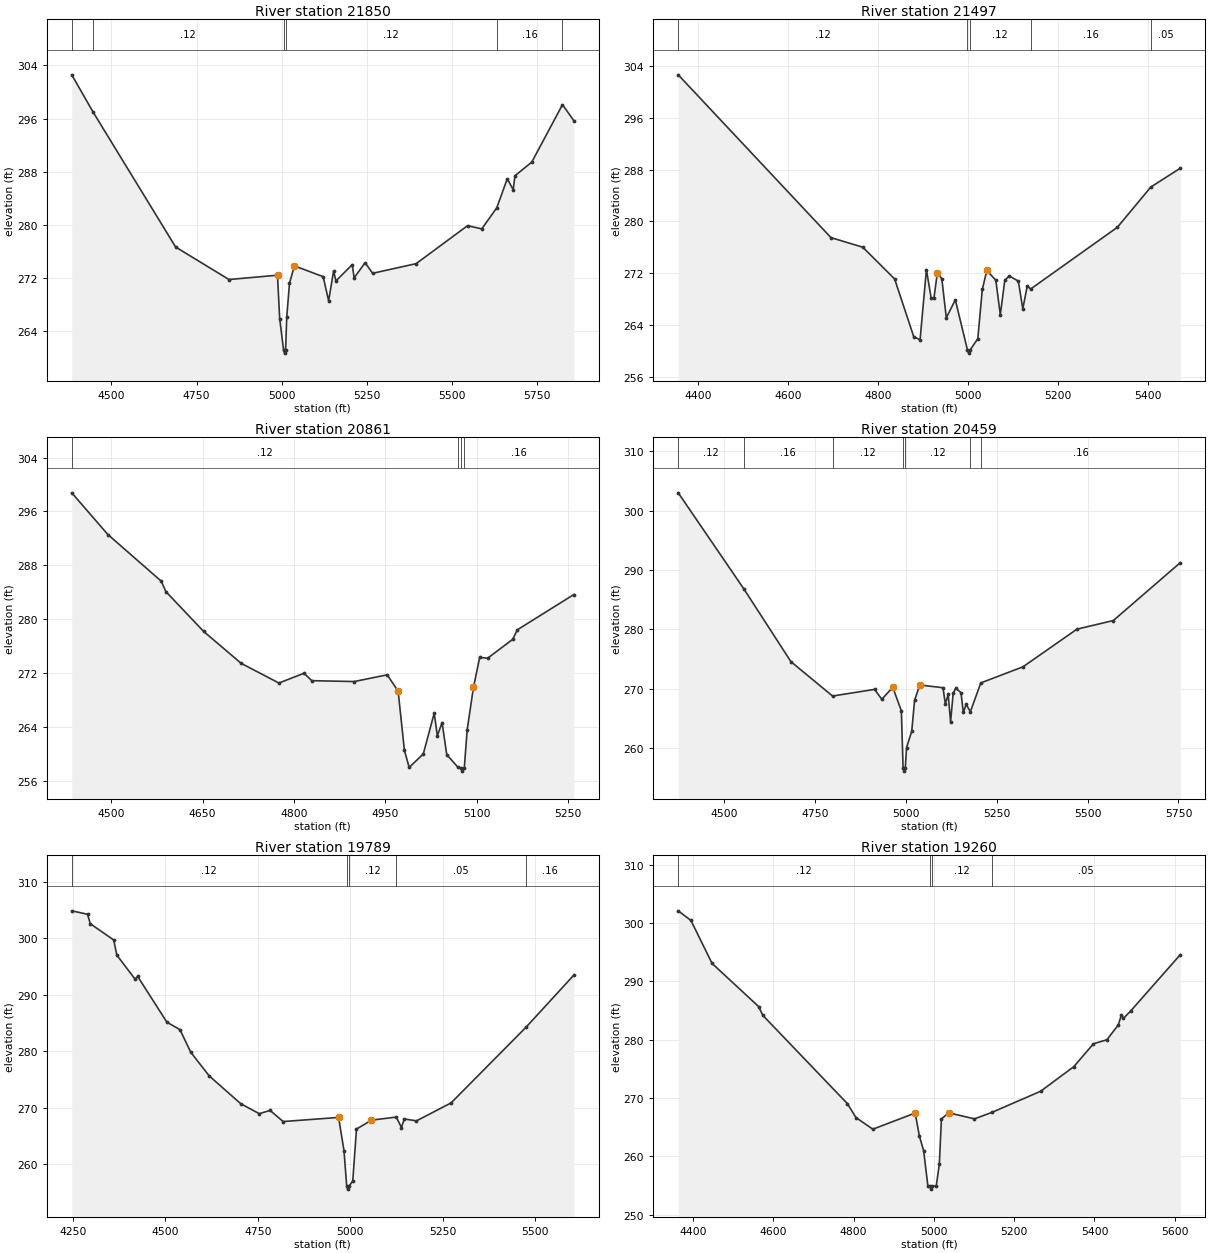
Type RM Length L Ch R = 1 ,21850   ,353,353,353
BEGIN DESCRIPTION:
Mapping XS f9d7d750
END DESCRIPTION:
XS GIS Cut Line= 3
      3650706.37     10699608.32      3650244.57      10700184.7
      3649557.04      10700448.6
#Sta/Elev= 30
  4383.3  302.59  4445.6  297.02  4688.4  276.69  4845.2   271.8  4987.7  272.45
  4994.1  265.91  5005.5  261.23  5008.3  260.73  5011.5  261.23  5014.9   266.2
  5022.9  271.23  5037.3  273.86  5121.8  272.23  5137.9   268.6  5152.5   273.1
  5159.3  271.58  5207.2  274.04  5212.9  272.06    5245  274.33  5267.3  272.74
    5395  274.19    5546   279.9  5587.8  279.42  5631.9  282.59  5662.7  286.95
  5680.1  285.32  5685.4  287.41  5734.8  289.47  5824.9   298.1  5858.3  295.69
#Mann= 6 ,-1 , 0
  4383.3     .16       0  4445.6     .12       0  5005.5     .07       0
  5011.5     .12       0  5631.9     .16       0  5824.9     .05       0
Bank Sta=4987.7,5037.3
XS Rating Curve= 0 ,0
Exp/Cntr=0.3,0.1

Type RM Length L Ch R = 1 ,21497   ,636,636,636
BEGIN DESCRIPTION:
MITCHELL BRANCH 19.0
END DESCRIPTION:
XS GIS Cut Line= 3
       3650599.6     10699560.19      3650199.61     10699960.19
      3649649.59     10699960.19
#Sta/Elev= 30
  4356.7  302.64  4696.1  277.48  4766.8     276  4837.5   271.1    4880  262.18
  4894.1  261.68  4908.2  272.54  4918.8  268.12  4924.9  268.12  4932.4  271.99
  4942.4  271.14  4952.4  265.09  4972.4  267.87  4999.4  260.13  5002.1  259.63
  5005.4  260.13  5022.4  261.86  5032.4  269.47  5042.4   272.4  5062.4  270.91
  5072.4  265.56  5082.4  270.88  5092.4  271.56  5112.4  270.76  5122.4  266.48
  5132.4  270.05  5139.6  269.53  5332.4  279.07  5406.9   285.3  5472.4  288.21
#Mann= 5 ,-1 , 0
  4356.7     .12       0  4999.4     .07       0  5005.4     .12       0
  5139.6     .16       0  5406.9     .05       0
Bank Sta=4932.4,5042.4
XS Rating Curve= 0 ,0
Exp/Cntr=0.3,0.1

Type RM Length L Ch R = 1 ,20861   ,402,402,402
BEGIN DESCRIPTION:
MITCHELL BRANCH 18.0
END DESCRIPTION:
XS GIS Cut Line= 3
      3650549.63     10699510.18      3649949.61     10699660.19
      3649749.65     10699710.18
#Sta/Elev= 30
  4435.2  298.77  4494.5  292.58  4582.1  285.66  4589.8   284.1  4651.7   278.2
  4713.5  273.45  4775.4  270.53  4816.6  271.98  4829.5  270.88  4899.1  270.75
  4953.2  271.75  4971.2  269.33  4981.5  260.56  4989.3     258  5012.5  259.99
  5030.5  266.06  5035.6   262.7  5043.4  264.65  5051.1  259.89  5069.4  258.03
  5073.9  257.95  5076.6  257.45  5079.9  257.95  5084.6  263.57  5094.9  269.87
  5105.2  274.34  5118.1  274.21  5159.3  277.01  5167.1  278.44  5259.8  283.67
#Mann= 4 ,-1 , 0
  4435.2     .12       0  5069.4     .16       0  5073.9     .07       0
  5079.9     .16       0
Bank Sta=4971.2,5094.9
XS Rating Curve= 0 ,0
Exp/Cntr=0.3,0.1

Type RM Length L Ch R = 1 ,20459   ,670,670,670
BEGIN DESCRIPTION:
MITCHELL BRANCH 17.0
END DESCRIPTION:
XS GIS Cut Line= 3
      3650599.62     10699260.19      3649999.61     10699260.19
      3649399.64     10699760.17
#Sta/Elev= 30
  4374.1  303.01  4554.4  286.84  4684.1  274.57  4798.6  268.78  4914.1   269.9
  4934.1  268.23  4964.1  270.25  4987.8  266.31  4992.6  256.63  4995.3  256.13
  4998.6  256.63  5002.1  260.08  5016.4  262.86  5024.2  268.07  5038.5  270.64
  5102.3  270.18  5108.8  267.46  5116.6  269.05  5123.2  264.42  5130.3  269.24
  5137.5  270.09  5151.8  269.36  5158.3  266.01  5166.1  267.39  5177.6  266.14
  5206.3  270.99  5322.3   273.7  5470.7  280.04  5570.9   281.5  5755.1  291.25
#Mann= 7 ,-1 , 0
  4374.1     .12       0  4554.4     .16       0  4798.6     .12       0
  4992.6     .07       0  4998.6     .12       0  5177.6     .05       0
  5206.3     .16       0
Bank Sta=4964.1,5038.5
XS Rating Curve= 0 ,0
Exp/Cntr=0.3,0.1

Type RM Length L Ch R = 1 ,19789   ,529,529,529
BEGIN DESCRIPTION:
MITCHELL BRANCH 16.0
END DESCRIPTION:
XS GIS Cut Line= 3
      3650499.58     10698410.21      3649899.61     10698860.19
      3649299.65     10698960.18
#Sta/Elev= 30
  4246.6  304.89  4289.3  304.28  4296.6  302.61  4360.1  299.72  4368.4  297.05
  4418.4  292.74  4424.7  293.28  4503.9  285.15  4539.3  283.83  4568.4  279.83
  4618.4  275.63  4703.9  270.69  4753.9  268.93    4783  269.52  4818.4  267.54
  4968.4  268.27    4983   262.4  4990.4  256.06  4993.2  255.56  4996.4  256.06
  5006.7  256.99  5016.8  266.21  5057.4  267.79  5124.5  268.33  5138.5  266.48
  5146.1     268  5179.1  267.66  5272.8  270.85  5475.2  284.24  5604.8   293.5
#Mann= 5 ,-1 , 0
  4246.6     .12       0  4990.4     .07       0  4996.4     .12       0
  5124.5     .05       0  5475.2     .16       0
Bank Sta=4968.4,5057.4
XS Rating Curve= 0 ,0
Exp/Cntr=0.3,0.1

Type RM Length L Ch R = 1 ,19260   ,452,452,452
BEGIN DESCRIPTION:
MITCHELL BRANCH 15.0
END DESCRIPTION:
XS GIS Cut Line= 3
      3650399.61     10698260.19      3649799.61     10698460.19
      3649199.63     10698310.19
#Sta/Elev= 30
  4362.9  302.11  4394.5  300.46  4447.2  293.09  4563.2  285.69  4573.7  284.18
  4784.5  269.03  4805.6  266.66  4847.8  264.66  4953.2  267.43  4963.7  263.48
  4974.3  260.98  4984.8  254.97  4989.7  254.88  4992.5  254.38  4995.7  254.88
  5005.7  254.91  5013.4  258.66  5018.6  266.41  5036.6  267.47    5101  266.43
  5144.4  267.54  5265.9  271.17  5348.4  275.38  5397.4  279.31  5430.9     280
  5459.2  282.53  5466.9  284.23  5472.1  283.68  5490.1  284.93  5613.8  294.59
#Mann= 4 ,-1 , 0
  4362.9     .12       0  4989.7     .07       0  4995.7     .12       0
  5144.4     .05       0
Bank Sta=4953.2,5036.6
XS Rating Curve= 0 ,0
Exp/Cntr=0.3,0.1

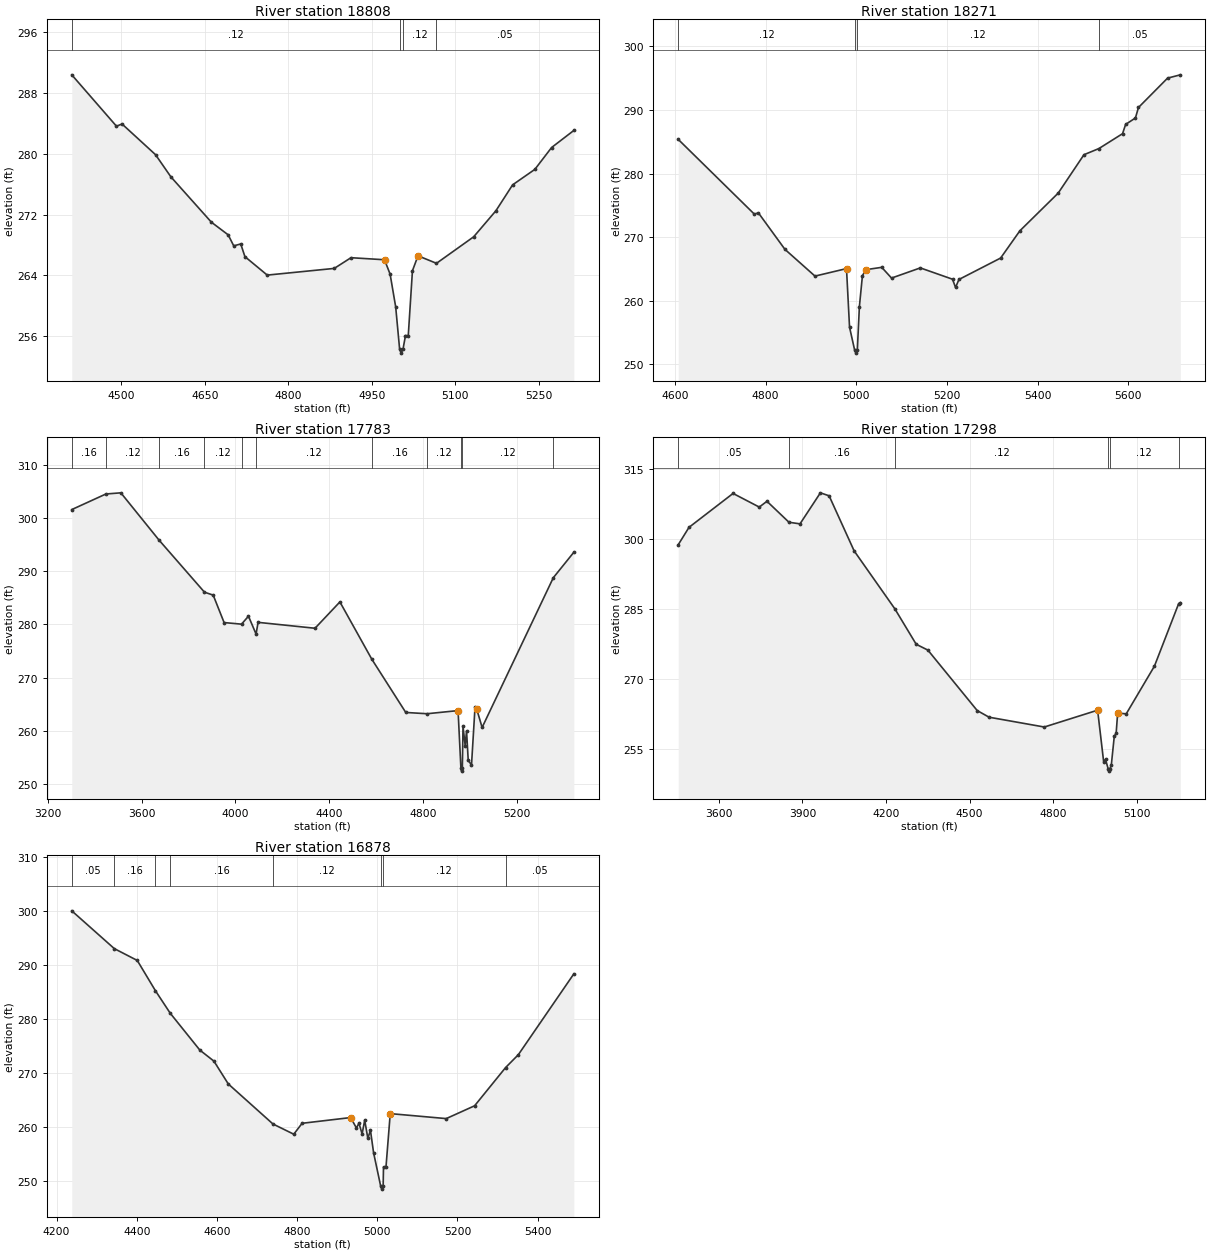
Type RM Length L Ch R = 1 ,18808   ,537,537,537
BEGIN DESCRIPTION:
MITCHELL BRANCH 14.0
END DESCRIPTION:
XS GIS Cut Line= 3
      3650249.61     10698110.19      3649649.61     10698060.19
      3649349.59     10698060.19
#Sta/Elev= 30
  4410.7  290.41    4491  283.65    4501  283.94  4561.2   279.9  4588.8  276.98
  4661.6  271.01  4691.7  269.35  4701.7   267.9  4714.3  268.15  4721.8  266.48
  4761.9  264.05  4882.3  264.93  4912.4  266.34  4972.6  266.07  4982.7  264.17
  4992.7  259.86  4999.8  254.28  5002.5  253.78  5005.8  254.28  5010.3  256.09
  5015.3  256.09  5022.8  264.62  5032.8  266.59    5066   265.6  5132.8  269.09
  5172.8  272.52  5202.8  275.93  5242.8  277.97  5272.8  280.84  5312.8  283.09
#Mann= 4 ,-1 , 0
  4410.7     .12       0  4999.8     .07       0  5005.8     .12       0
    5066     .05       0
Bank Sta=4972.6,5032.8
XS Rating Curve= 0 ,0
Exp/Cntr=0.3,0.1

Type RM Length L Ch R = 1 ,18271   ,488,488,488
BEGIN DESCRIPTION:
MITCHELL BRANCH 13.0
END DESCRIPTION:
XS GIS Cut Line= 3
      3650199.58     10697810.18      3649849.61     10697710.19
      3649349.59     10697160.17
#Sta/Elev= 30
  4607.2  285.37  4774.9  273.62    4784  273.81  4842.5  268.07  4908.8  263.86
  4978.3  265.04    4985  255.82  4996.2  252.24    4999  251.74  5002.2  252.24
  5006.7  259.05  5013.4  263.91  5020.8  264.87    5056  265.24  5077.6  263.55
  5141.1  265.15  5212.1  263.37  5218.8  262.07  5226.3  263.33  5318.2   266.7
  5360.7  270.99  5445.2  276.92    5502  282.96    5535  283.93  5587.1  286.27
  5593.9  287.73  5615.5  288.74  5622.2  290.39  5686.4  295.01  5714.5  295.53
#Mann= 4 ,-1 , 0
  4607.2     .12       0  4996.2     .07       0  5002.2     .12       0
    5535     .05       0
Bank Sta=4978.3,5020.8
XS Rating Curve= 0 ,0
Exp/Cntr=0.3,0.1

Type RM Length L Ch R = 1 ,17783   ,485,485,485
BEGIN DESCRIPTION:
MITCHELL BRANCH 12.0
END DESCRIPTION:
XS GIS Cut Line= 4
      3651217.11     10698239.79      3650466.44     10697905.99
      3650175.64     10697524.05      3649472.56       10697064.
#Sta/Elev= 30
  3302.3  301.57  3447.9   304.5  3511.7  304.72  3674.8  295.82  3868.4  286.04
  3905.6  285.49  3952.1  280.33  4026.5  280.03  4056.1  281.53  4088.5  278.17
  4097.1  280.37    4340  279.26  4446.1  284.21  4582.1  273.45  4727.1  263.43
  4818.1  263.19  4950.2  263.78  4962.4   252.9  4965.1   252.4  4968.4   252.9
  4971.3  260.79  4980.5  257.21  4986.4  259.97  4993.5  254.45  5007.5  253.52
  5022.6  264.48  5029.4  264.12  5052.8  260.61  5356.5  288.76  5444.1  293.55
#Mann= 11 ,-1 , 0
  3302.3     .16       0  3447.9     .12       0  3674.8     .16       0
  3868.4     .12       0  4026.5     .16       0  4088.5     .12       0
  4582.1     .16       0  4818.1     .12       0  4962.4     .07       0
  4968.4     .12       0  5356.5     .05       0
Bank Sta=4950.2,5029.4
XS Rating Curve= 0 ,0
Exp/Cntr=0.3,0.1

Type RM Length L Ch R = 1 ,17298   ,420,420,420
BEGIN DESCRIPTION:
MITCHELL BRANCH 11.0
END DESCRIPTION:
XS GIS Cut Line= 4
      3651237.96     10696153.01      3650549.61     10696360.19
      3649937.21     10696915.15      3649699.62     10697010.19
#Sta/Elev= 30
  3454.7  298.76  3493.3  302.48  3651.4  309.74  3745.4  306.82    3773  308.06
    3852  303.57  3891.6  303.23  3964.7  309.87    3996  309.23  4085.8  297.44
  4231.5  285.07  4308.4  277.46  4350.3  276.21  4527.3  263.27  4569.9  261.85
  4767.9  259.75  4959.2  263.35  4980.8  252.37  4987.6  252.83    4997  250.81
  4999.7  250.31    5003  250.81  5008.2  251.52    5019  257.76  5025.7   258.4
  5031.1  262.71    5062  262.58    5163  272.77  5249.9  286.14  5255.9  286.37
#Mann= 6 ,-1 , 0
  3454.7     .05       0    3852     .16       0  4231.5     .12       0
    4997     .07       0    5003     .12       0  5249.9     .05       0
Bank Sta=4959.2,5031.1
XS Rating Curve= 0 ,0
Exp/Cntr=0.3,0.1

Type RM Length L Ch R = 1 ,16878   ,673,673,673
BEGIN DESCRIPTION:
MITCHELL BRANCH 10.0
END DESCRIPTION:
XS GIS Cut Line= 3
      3650449.62     10696060.18      3649849.61     10696560.19
      3649599.63     10696960.15
#Sta/Elev= 30
  4237.8     300  4343.9  293.01  4401.2  290.82  4446.6  285.21  4483.5  281.05
  4557.4  274.23  4592.5  272.19  4628.3  267.97  4739.8  260.56  4791.7  258.67
  4812.5  260.69  4933.6  261.75  4947.9  259.84  4954.4  260.69  4962.2  258.72
  4968.7  261.27  4976.5   257.9    4983   259.4  4990.9  255.22  5008.7  249.01
  5011.4  248.51  5014.7  249.01  5015.6  252.62  5021.8  252.62  5032.4  262.48
  5172.1  261.56  5242.9  263.93  5320.2     271    5352  273.38  5490.5  288.34
#Mann= 8 ,-1 , 0
  4237.8     .05       0  4343.9     .16       0  4446.6     .12       0
  4483.5     .16       0  4739.8     .12       0  5008.7     .07       0
  5014.7     .12       0  5320.2     .05       0
Bank Sta=4933.6,5032.4
XS Rating Curve= 0 ,0
Exp/Cntr=0.3,0.1