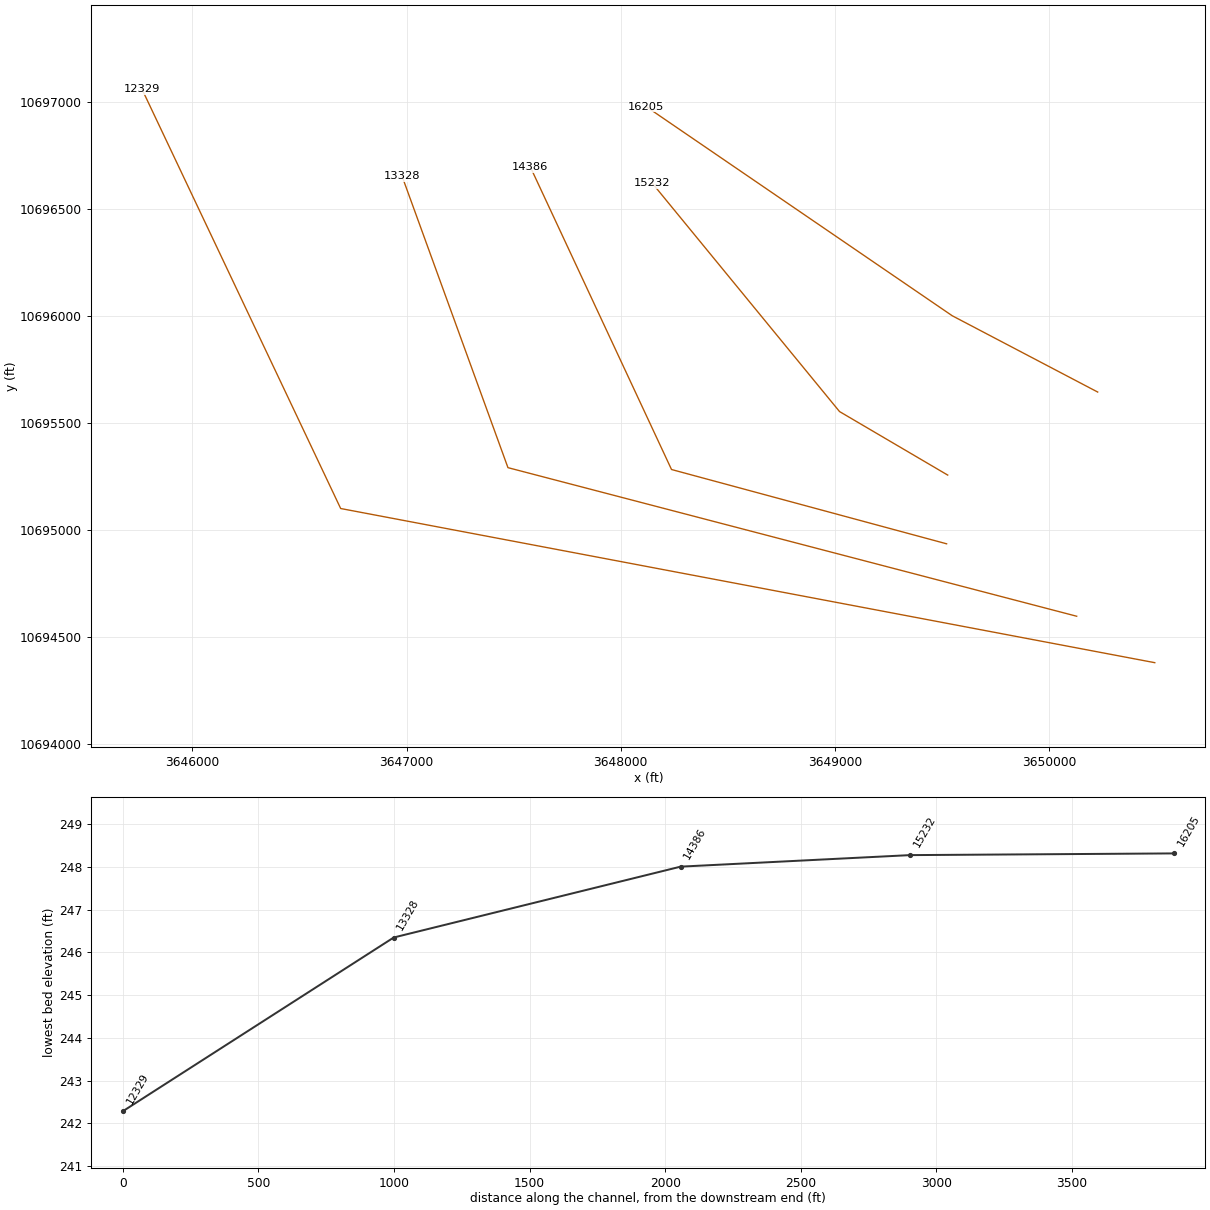
HEC-RAS study MITCHELL BRANCH.prj: MITCHELL BRANCH Base Level Engineering

--- MITCHELL BRANCH.g01 (geometry) --- (continued)

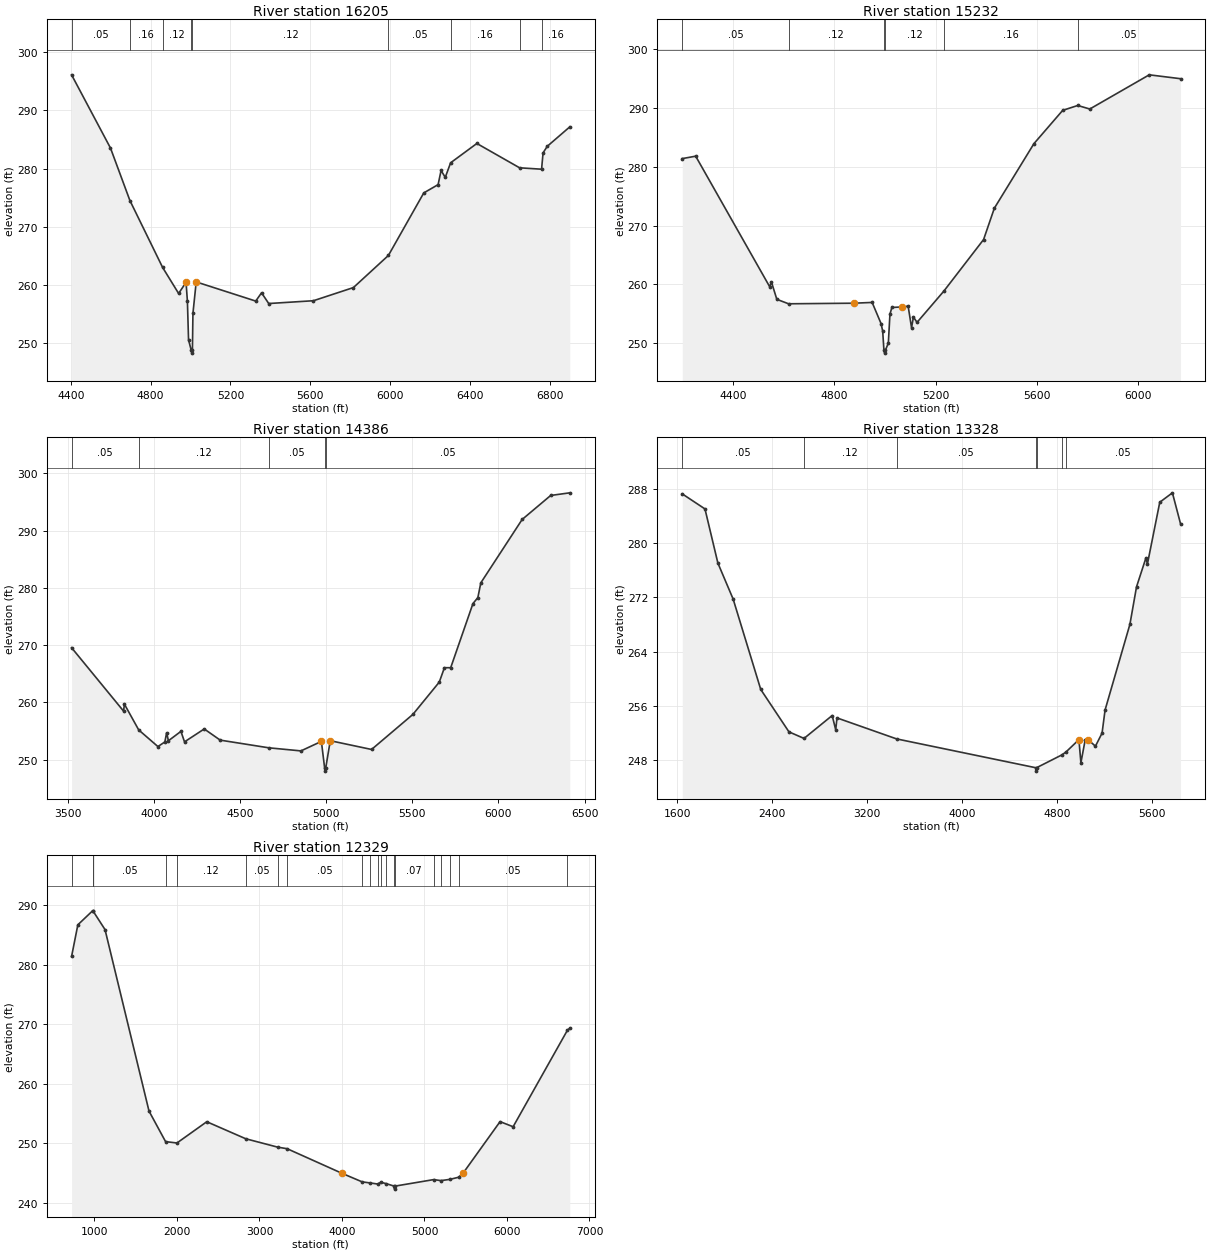
Type RM Length L Ch R = 1 ,16205   ,973,973,973
BEGIN DESCRIPTION:
MITCHELL BRANCH 9.0
END DESCRIPTION:
XS GIS Cut Line= 3
      3650227.72     10695644.71      3649548.04     10696001.51
      3648120.07     10696978.08
#Sta/Elev= 30
  4403.5  296.12  4598.6  283.54  4695.9  274.53  4859.7  263.05  4940.1  258.57
  4977.4  260.48  4984.2  257.23  4989.9   250.6  5003.3  248.82    5006  248.32
  5009.3  248.82  5011.9  255.15  5028.3  260.55  5326.7  257.26  5355.9  258.68
  5391.8  256.84    5616  257.32  5816.4  259.58  5991.9   265.1  6169.2  275.84
    6241  277.26  6255.9  279.69  6276.9  278.51  6303.7  281.01  6435.3  284.33
  6649.5  280.15  6759.7  279.91  6767.2  282.71  6788.1  283.84  6901.1  287.18
#Mann= 9 ,-1 , 0
  4403.5     .05       0  4695.9     .16       0  4859.7     .12       0
  5003.3     .07       0  5009.3     .12       0  5991.9     .05       0
  6303.7     .16       0  6649.5     .05       0  6759.7     .16       0
Bank Sta=4977.4,5028.3
XS Rating Curve= 0 ,0
Exp/Cntr=0.3,0.1

Type RM Length L Ch R = 1 ,15232   ,846,846,846
BEGIN DESCRIPTION:
MITCHELL BRANCH 8.0
END DESCRIPTION:
XS GIS Cut Line= 3
       3649527.2     10695256.72        3649022.      10695553.6
      3648147.01     10696621.29
#Sta/Elev= 30
  4200.2   281.4    4253  281.81  4545.4  259.56  4551.8  260.42  4573.3  257.44
  4619.6  256.68  4877.7  256.78  4949.5  256.91  4984.7  253.31  4991.1  252.04
    4996  248.78  4998.8  248.28    5002  248.78  5013.4  249.99  5019.8  254.92
  5027.4  256.05  5069.3  256.15  5091.6  256.28    5105  252.61  5112.4  254.41
  5126.8  253.52  5232.4  258.83  5389.4  267.62  5431.8  272.95  5588.2  283.95
  5701.6  289.61    5761  290.44  5808.6  289.84  6043.3  295.66  6166.6     295
#Mann= 6 ,-1 , 0
  4200.2     .05       0  4619.6     .12       0    4996     .07       0
    5002     .12       0  5232.4     .16       0    5761     .05       0
Bank Sta=4877.7,5069.3
XS Rating Curve= 0 ,0
Exp/Cntr=0.3,0.1

Type RM Length L Ch R = 1 ,14386   ,1058,1058,1058
BEGIN DESCRIPTION:
MITCHELL BRANCH 7.0
END DESCRIPTION:
XS GIS Cut Line= 3
      3649522.03     10694935.53      3648237.27     10695282.76
      3647578.15      10696696.4
#Sta/Elev= 30
  3523.2  269.55  3824.7  258.49  3829.9  259.69  3912.7   255.2  4024.1   252.3
  4064.4   253.1  4074.7  254.71  4085.1  253.31  4157.6  254.95  4178.5  253.12
  4292.9  255.37  4385.5  253.42  4667.3  252.08    4854  251.54  4972.6   253.2
  4991.6  248.51  4994.4  248.01  4997.6  248.51  5024.1  253.32  5263.8  251.79
  5503.5  257.91  5656.7  263.55  5686.4  266.06  5722.9  266.06    5852  277.25
  5880.4  278.29  5897.7  280.87  6137.4  291.93    6303  296.12  6413.8  296.58
#Mann= 5 ,-1 , 0
  3523.2     .05       0  3912.7     .12       0  4667.3     .05       0
  4991.6     .03       0  4997.6     .05       0
Bank Sta=4972.6,5024.1
XS Rating Curve= 0 ,0
Exp/Cntr=0.3,0.1

Type RM Length L Ch R = 1 ,13328   ,999,999,999
BEGIN DESCRIPTION:
Mapping XS dca508b2
END DESCRIPTION:
XS GIS Cut Line= 3
      3650129.61       10694597.      3647473.38     10695291.44
      3646978.59      10696654.3
#Sta/Elev= 30
    1643  287.29  1833.9  285.07  1942.7  277.07  2071.3  271.75  2303.6  258.41
  2541.1  252.15  2668.1  251.18  2905.1  254.56    2935  252.45  2945.5  254.21
  3447.3  251.11  4619.9  246.85  4622.7  246.35  4625.9  246.85  4838.6  248.74
  4874.2  249.18  4982.9     251  4999.6  247.58  5036.1     251  5060.8  250.99
    5122  250.03  5177.9  251.97  5203.2  255.38  5412.2  268.02  5468.1  273.57
  5546.8  277.81  5559.9  276.94  5663.8  286.06  5770.2  287.45  5838.4   282.9
#Mann= 7 ,-1 , 0
    1643     .05       0  2668.1     .12       0  3447.3     .05       0
  4619.9     .03       0  4625.9     .05       0  4838.6     .07       0
  4874.2     .05       0
Bank Sta=4982.9,5060.8
XS Rating Curve= 0 ,0
Exp/Cntr=0.3,0.1

Type RM Length L Ch R = 1 ,12329   ,0,0,0
BEGIN DESCRIPTION:
Mapping XS b70f2430
END DESCRIPTION:
XS GIS Cut Line= 3
      3650494.27     10694379.97      3646692.13     10695100.47
      3645763.94     10697060.95
#Sta/Elev= 30
   722.6  281.36   798.6  286.68     977  289.03   985.1  288.95    1128  285.88
  1661.2  255.39  1861.9  250.26  1999.9  250.03  2361.4   253.6  2833.9  250.74
  3221.5  249.33  3335.5  249.07  4004.6  244.91  4244.9   243.5  4345.2  243.31
  4431.6  243.14  4471.6  243.43  4536.7   243.2  4634.6  242.78  4637.4  242.28
  4640.6  242.78  5111.7  243.88  5200.4  243.71  5308.5  243.92    5415  244.28
  5466.2  244.92  5916.5  253.62  6074.7  252.76  6732.9  268.97  6761.5  269.31
#Mann= 20 ,-1 , 0
   722.6     .05       0     977     .16       0   985.1     .05       0
  1861.9     .07       0  1999.9     .12       0  2833.9     .05       0
  3221.5     .12       0  3335.5     .05       0  4244.9     .07       0
  4345.2     .05       0  4431.6     .07       0  4471.6     .12       0
  4536.7     .07       0  4634.6     .07       0  4640.6     .07       0
  5111.7     .05       0  5200.4     .07       0  5308.5     .12       0
    5415     .05       0  6732.9     .08       0
Bank Sta=4004.6,5466.2
XS Rating Curve= 0 ,0
Exp/Cntr=0.3,0.1

Chan Stop Cuts=-1
Use User Specified Reach Order=0
Composite Channel Slope=5