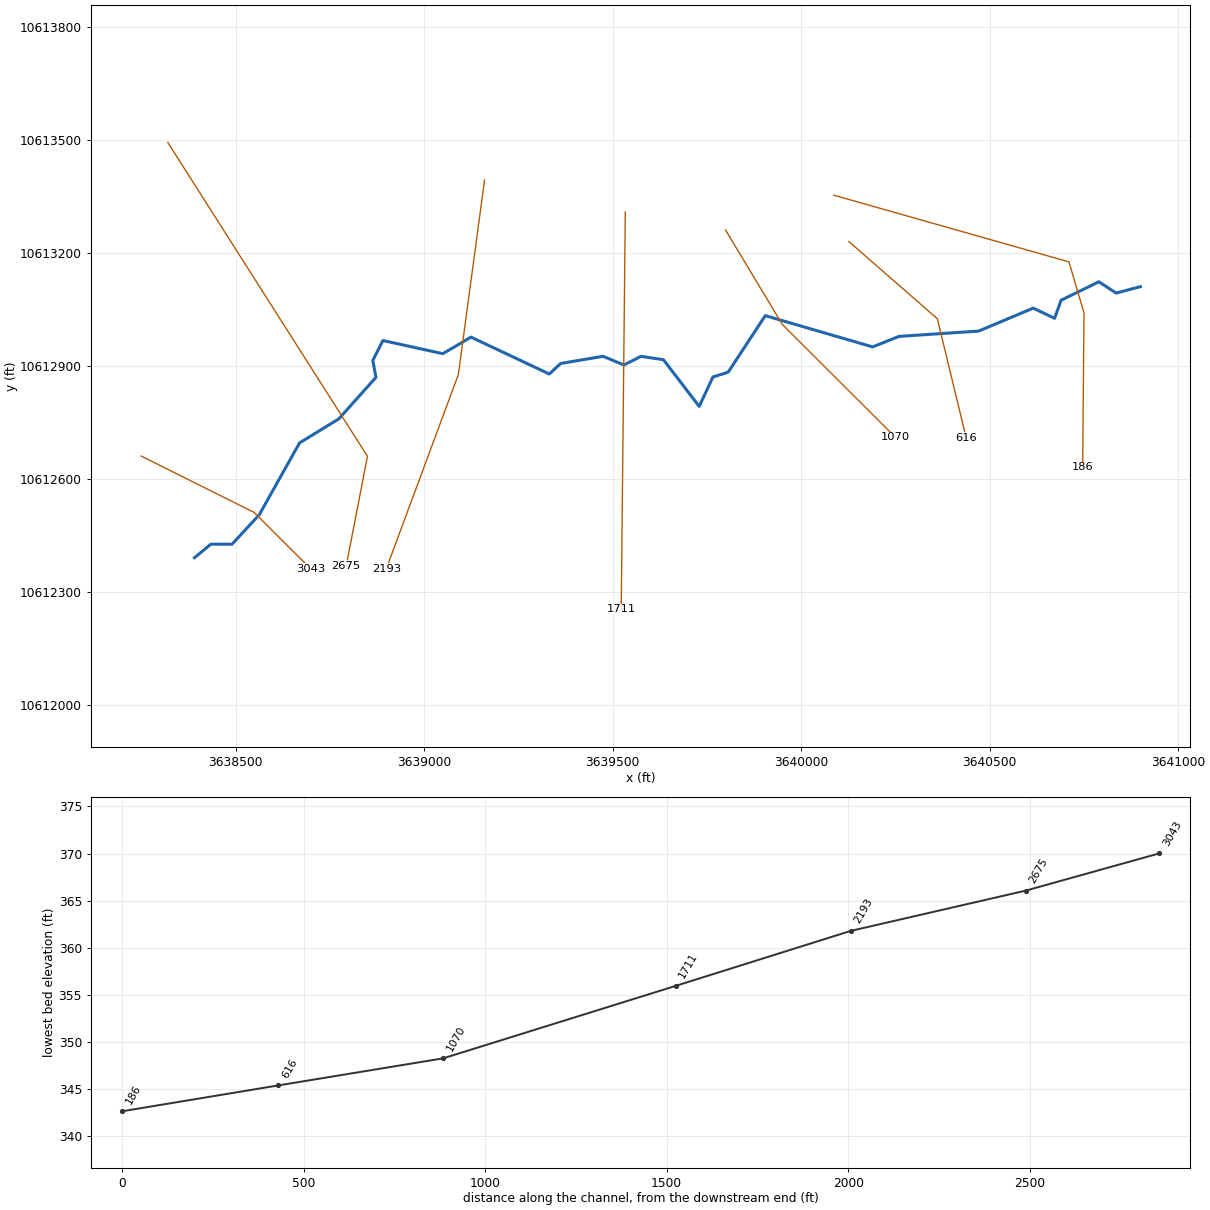
--- TANYARD BRANCH.prj (project) ---

Proj Title=TANYARD BRANCH Base Level Engineering
Current Plan=p01
Default Exp/Contr=0.3,0.1
English Units
Geom File=g01
Flow File=f01
Plan File=p01
Y Axis Title=Elevation
X Axis Title(PF)=Main Channel Distance
X Axis Title(XS)=Station
BEGIN DESCRIPTION:
TANYARD BRANCH
END DESCRIPTION:
DSS Export Rating Curves= 0
DSS Export Rating Curve Sorted= 0
DSS Export Volume Flow Curves= 0
DXF OffsetX= 0
DXF OffsetY= 0
DXF ScaleX= 1
DXF ScaleY= 10

--- TANYARD BRANCH.p01 (plan) ---

Plan Title=Multiple Run
Short Identifier=Multiple
Geom File=g01
Flow File=f01
Subcritical Flow
K Sum by GR= 0
Std Step Tol= 0.01
Critical Tol= 0.01
Num of Std Step Trials= 20
Max Error Tol= 0.3
Flow Tol Ratio= 0.001
Split Flow NTrial= 30
Split Flow Tol= 0.02
Split Flow Ratio= 0.02
Log Output Level= 0
Friction Slope Method= 1
Unsteady Friction Slope Method= 2
Unsteady Bridges Friction Slope Method= 1
Parabolic Critical Depth
Global Vel Dist=  1 , 1 , 1
Global Log Level= 0
CheckData=True
Encroach Param= -1, 0, 0, 0
BEGIN DESCRIPTION:
Multiple Run
END DESCRIPTION:

--- TANYARD BRANCH.f01 (steady flow) ---

Flow Title=Multiple
Number of Profiles=7
Profile Names=10-year,25-year,50-year,1pct_min,100-year,1pct_plu,500-year
River Rch & RM= TANYARD BRANCH,Reach-1,3043
    1063    1484    1839    1668    2256    3051    3378
Boundary for River Rch & Prof#=TANYARD BRANCH,Reach-1,1
Up Type=0
Dn Type=3
Dn Slope=0.005
Boundary for River Rch & Prof#=TANYARD BRANCH,Reach-1,2
Up Type=0
Dn Type=3
Dn Slope=0.005
Boundary for River Rch & Prof#=TANYARD BRANCH,Reach-1,3
Up Type=0
Dn Type=3
Dn Slope=0.005
Boundary for River Rch & Prof#=TANYARD BRANCH,Reach-1,4
Up Type=0
Dn Type=3
Dn Slope=0.005
Boundary for River Rch & Prof#=TANYARD BRANCH,Reach-1,5
Up Type=0
Dn Type=3
Dn Slope=0.005
Boundary for River Rch & Prof#=TANYARD BRANCH,Reach-1,6
Up Type=0
Dn Type=3
Dn Slope=0.005
Boundary for River Rch & Prof#=TANYARD BRANCH,Reach-1,7
Up Type=0
Dn Type=3
Dn Slope=0.005

--- TANYARD BRANCH.g01 (geometry) ---

Geom Title=Existing Conditions
Program Version=4.10

River Reach=TANYARD BRANCH  ,Reach-1
Reach XY= 30
        3638391.       10612390.       3638434.5       10612426.
      3638490.75       10612426.      3638562.75       10612504.
      3638669.75       10612695.        3638774.       10612759.
      3638872.25       10612869.        3638864.       10612914.
      3638890.75       10612967.      3639049.75       10612932.
       3639124.5       10612976.        3639332.       10612878.
      3639362.25       10612906.      3639474.75       10612925.
        3639530.       10612902.      3639575.25       10612925.
      3639634.75       10612916.       3639729.5       10612792.
        3639766.       10612870.       3639806.5       10612883.
      3639904.75       10613033.       3640189.5       10612950.
      3640259.75       10612978.       3640470.5       10612992.
       3640615.5       10613053.        3640672.       10613026.
      3640689.25       10613074.       3640789.5       10613123.
      3640835.25       10613093.       3640899.5       10613110.

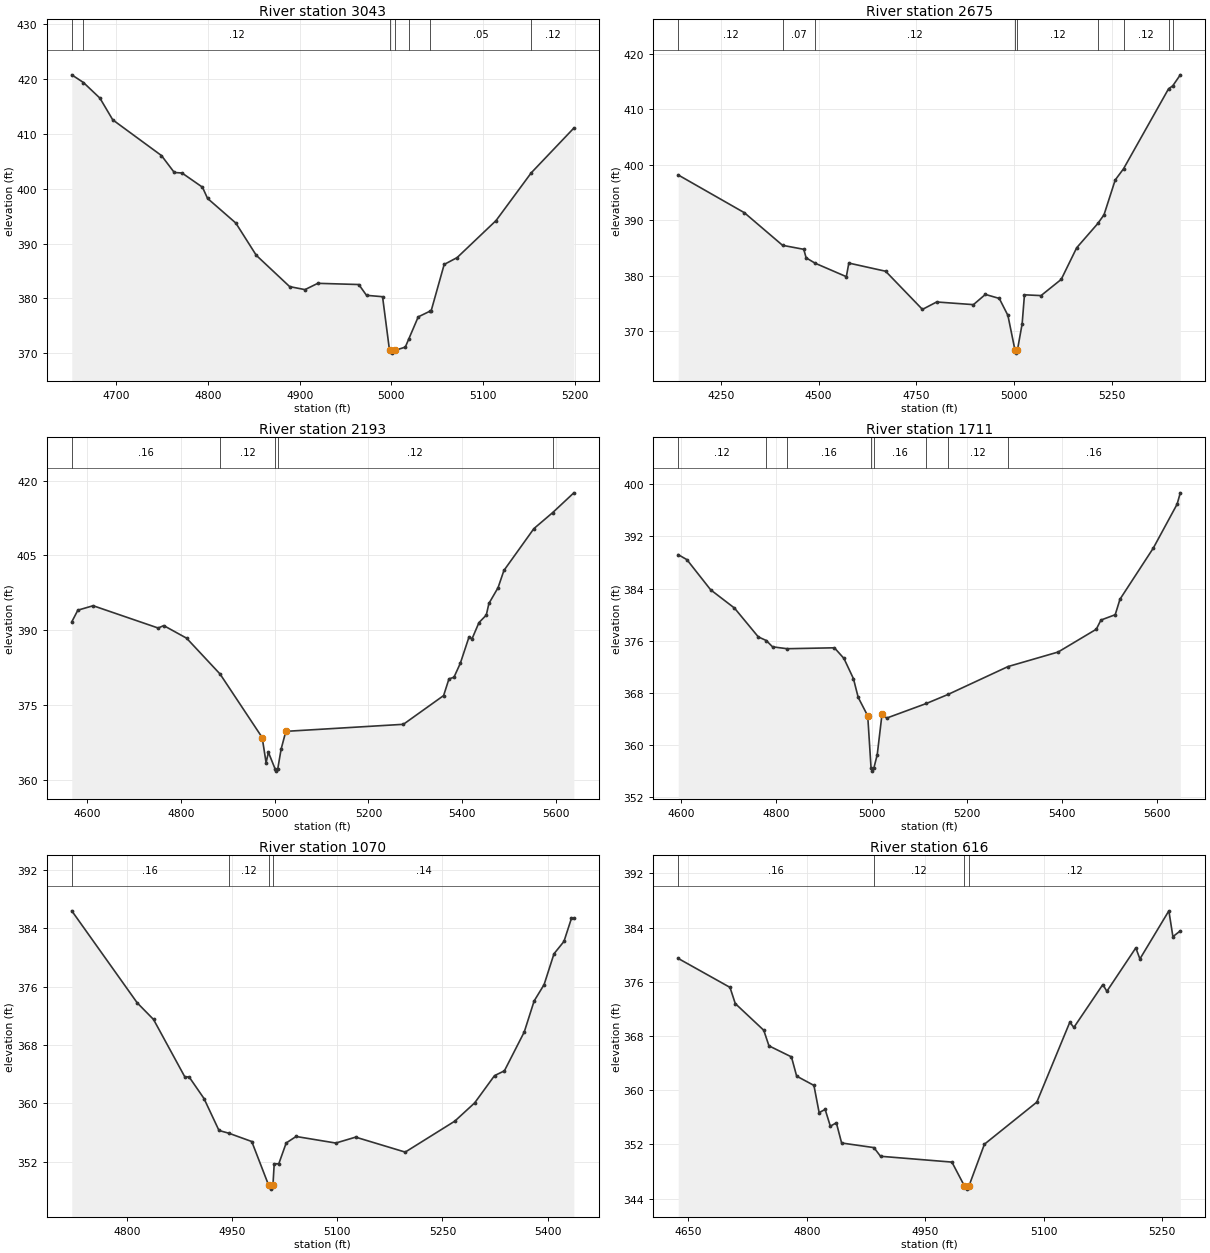
Type RM Length L Ch R = 1 ,3043    ,368,368,368
BEGIN DESCRIPTION:
TANYARD BRANCH 6.0
END DESCRIPTION:
XS GIS Cut Line= 3
      3638249.62     10612660.18      3638549.61     10612510.19
      3638699.59     10612360.21
#Sta/Elev= 30
  4651.5  420.76  4664.2  419.36  4682.2  416.51  4696.2  412.55  4749.3  406.04
  4763.3  402.95  4771.7  402.86    4794  400.27  4799.6  398.22  4830.4  393.73
  4852.7  387.85  4889.1  382.14  4905.8  381.59  4919.8  382.74  4964.5  382.52
  4972.9  380.55  4990.4   380.3    4998  370.51  5000.8  370.01    5004  370.51
  5015.2  371.11    5019  372.59  5029.3  376.62  5041.6  377.62  5043.5  377.78
  5057.6  386.18  5071.7  387.43  5114.2  394.19  5152.5  402.88    5199  411.05
#Mann= 7 ,-1 , 0
  4651.5     .16       0  4664.2     .12       0    4998     .07       0
    5004     .12       0    5019     .16       0  5041.6     .05       0
  5152.5     .12       0
Bank Sta=4998,5004
XS Rating Curve= 0 ,0
Exp/Cntr=0.3,0.1

Type RM Length L Ch R = 1 ,2675    ,482,482,482
BEGIN DESCRIPTION:
TANYARD BRANCH 5.0
END DESCRIPTION:
XS GIS Cut Line= 3
      3638320.47     10613492.87      3638849.84     10612659.49
      3638793.57     10612368.78
#Sta/Elev= 30
  4141.4  398.17  4310.4  391.37  4408.1  385.49  4462.3  384.77  4468.3  383.24
  4491.2  382.27  4571.1  379.84  4577.5  382.29  4671.5  380.82  4765.6  373.94
    4802  375.28    4896   374.8  4926.5  376.64    4962  375.92  4984.1  372.86
  5002.3  366.56    5005  366.06  5008.3  366.56  5020.5  371.34  5026.4  376.57
  5068.8  376.43  5120.4  379.35  5159.9  385.05    5214  389.43  5229.8     391
  5258.4  397.27  5279.6  399.28  5394.8  413.71  5405.4  414.23  5424.8  416.22
#Mann= 9 ,-1 , 0
  4141.4     .12       0  4408.1     .07       0  4491.2     .12       0
  5002.3     .07       0  5008.3     .12       0    5214     .16       0
  5279.6     .12       0  5394.8     .16       0  5405.4     .12       0
Bank Sta=5002.3,5008.3
XS Rating Curve= 0 ,0
Exp/Cntr=0.3,0.1

Type RM Length L Ch R = 1 ,2193    ,482,482,482
BEGIN DESCRIPTION:
TANYARD BRANCH 4.0
END DESCRIPTION:
XS GIS Cut Line= 3
      3639160.32     10613393.06      3639090.87     10612876.55
      3638899.61      10612360.2
#Sta/Elev= 30
  4566.8   391.7  4579.8  394.04  4612.4  394.93  4751.3  390.46  4763.1  390.95
  4811.9  388.43  4883.4  381.24  4973.3  368.52  4981.6  363.48  4986.6  365.56
  5000.6  362.29  5003.3  361.79  5006.6  362.29  5013.7   366.2  5023.8  369.76
  5274.7  371.17  5360.6  376.93    5372  380.27  5382.7   380.6  5396.3  383.41
  5414.7  388.64  5421.3  388.31    5436  391.54  5451.7  393.06  5457.3  395.39
  5476.8  398.54  5489.3  401.99  5553.3  410.38  5593.2  413.57  5638.6  417.55
#Mann= 5 ,-1 , 0
  4566.8     .16       0  4883.4     .12       0  5000.6     .07       0
  5006.6     .12       0  5593.2     .16       0
Bank Sta=4973.3,5023.8
XS Rating Curve= 0 ,0
Exp/Cntr=0.3,0.1

Type RM Length L Ch R = 1 ,1711    ,641,641,641
BEGIN DESCRIPTION:
TANYARD BRANCH 3.0
END DESCRIPTION:
XS GIS Cut Line= 2
      3639533.58     10613308.42      3639522.75     10612253.37
#Sta/Elev= 30
  4593.7   389.2  4611.9  388.44  4661.9   383.8  4711.9     381  4761.9  376.58
  4778.6  376.02  4791.9  375.05  4822.5  374.76  4921.9   374.9  4941.9  373.27
  4961.9  370.16  4971.9  367.28  4991.9  364.45  4998.9  356.46  5001.7  355.96
  5004.9  356.46  5011.9  358.49  5021.9  364.68  5031.9  364.11  5115.2  366.35
  5160.5  367.73  5286.8  372.02    5392  374.25  5472.2  377.75    5482  379.16
    5512  379.98    5522  382.36    5592  390.21    5642  396.95  5648.8   398.7
#Mann= 8 ,-1 , 0
  4593.7     .12       0  4778.6     .16       0  4822.5     .16       0
  4998.9     .07       0  5004.9     .16       0  5115.2     .16       0
  5160.5     .12       0  5286.8     .16       0
Bank Sta=4991.9,5021.9
XS Rating Curve= 0 ,0
Exp/Cntr=0.3,0.1

Type RM Length L Ch R = 1 ,1070    ,454,454,454
BEGIN DESCRIPTION:
TANYARD BRANCH 2.0
END DESCRIPTION:
XS GIS Cut Line= 3
      3639799.61     10613260.19      3639949.61     10613010.19
       3640249.6      10612710.2
#Sta/Elev= 30
  4721.6  386.38  4814.9  373.78  4838.2   371.5  4882.9  363.62  4888.8  363.65
  4910.1  360.68  4931.5   356.3  4945.4  355.93  4978.2  354.79  5002.4  348.77
  5005.1  348.27  5008.4  348.77  5010.2  351.73  5016.7  351.73  5027.3  354.59
  5041.4  355.48    5098  354.58  5126.3  355.39    5197  353.34  5267.7  357.58
    5296  360.08  5324.3  363.81  5338.4  364.47  5366.7  369.79  5380.8  374.04
    5395  376.28  5409.1   380.5  5423.3  382.19  5433.9  385.33  5437.4  385.33
#Mann= 4 ,-1 , 0
  4721.6     .16       0  4945.4     .12       0  5002.4     .07       0
  5008.4     .14       0
Bank Sta=5002.4,5008.4
XS Rating Curve= 0 ,0
Exp/Cntr=0.3,0.1

Type RM Length L Ch R = 1 ,616     ,430,430,430
BEGIN DESCRIPTION:
Mapping XS 4368a0ce
END DESCRIPTION:
XS GIS Cut Line= 3
      3640126.69      10613229.7      3640361.09     10613024.82
      3640437.48     10612708.84
#Sta/Elev= 30
    4637  379.45  4702.6  375.18  4709.3  372.79  4745.4  368.85    4752  366.55
  4780.5  364.92  4787.1  362.08    4809  360.71  4815.6  356.69  4823.2  357.17
  4829.8  354.69  4837.4  355.19  4844.1  352.21    4885  351.53  4893.4  350.25
  4983.9  349.39  4999.6   345.9  5002.4   345.4  5005.6   345.9  5025.1  352.03
  5091.5  358.24  5133.3  370.03  5138.5  369.27  5175.2   375.6  5180.3   374.6
    5217  381.01  5222.2  379.38  5258.9  386.48    5264  382.67  5273.4  383.52
#Mann= 4 ,-1 , 0
    4637     .16       0    4885     .12       0  4999.6     .07       0
  5005.6     .12       0
Bank Sta=4999.6,5005.6
XS Rating Curve= 0 ,0
Exp/Cntr=0.3,0.1

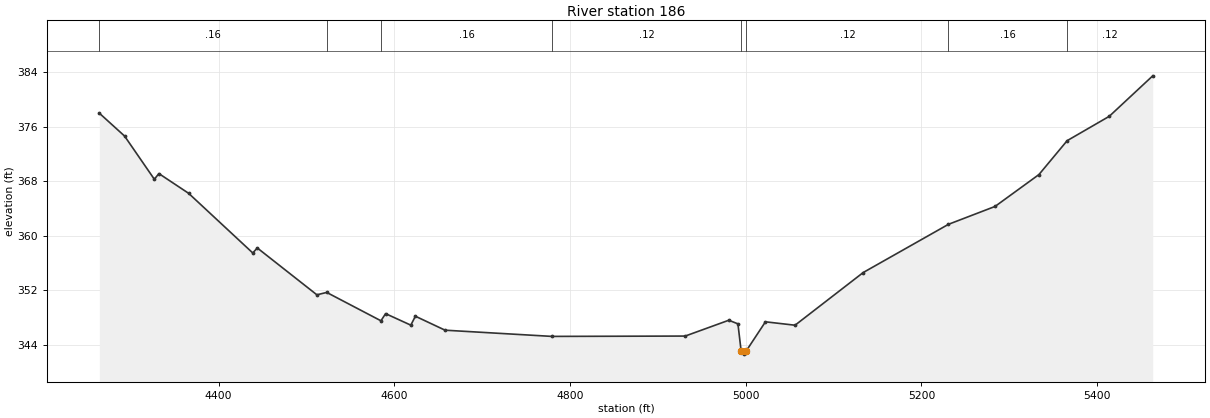
Type RM Length L Ch R = 1 ,186     ,0,0,0
BEGIN DESCRIPTION:
TANYARD BRANCH 1.0
END DESCRIPTION:
XS GIS Cut Line= 4
      3640086.77     10613352.95      3640710.05     10613175.86
      3640749.98     10613040.45       3640746.5     10612630.68
#Sta/Elev= 30
  4264.3     378    4293  374.65  4326.9  368.31  4332.1  369.14  4365.9  366.25
  4438.9   357.5  4444.1  358.23  4511.9  351.36  4523.1  351.71  4584.8  347.55
  4590.1   348.6  4618.8  346.91    4624  348.22  4657.8  346.17  4779.4  345.26
  4931.1  345.31  4980.7  347.63  4991.1   347.1  4994.7  343.16  4997.5  342.66
  5000.7  343.16  5022.4   347.4  5056.1   346.9  5133.7  354.63  5230.7   361.7
  5283.7  364.32  5333.7     369  5365.8  373.97  5413.7  377.54  5463.2  383.48
#Mann= 8 ,-1 , 0
  4264.3     .16       0  4523.1     .12       0  4584.8     .16       0
  4779.4     .12       0  4994.7     .07       0  5000.7     .12       0
  5230.7     .16       0  5365.8     .12       0
Bank Sta=4994.7,5000.7
XS Rating Curve= 0 ,0
Exp/Cntr=0.3,0.1

Chan Stop Cuts=-1
Use User Specified Reach Order=0
Composite Channel Slope=5