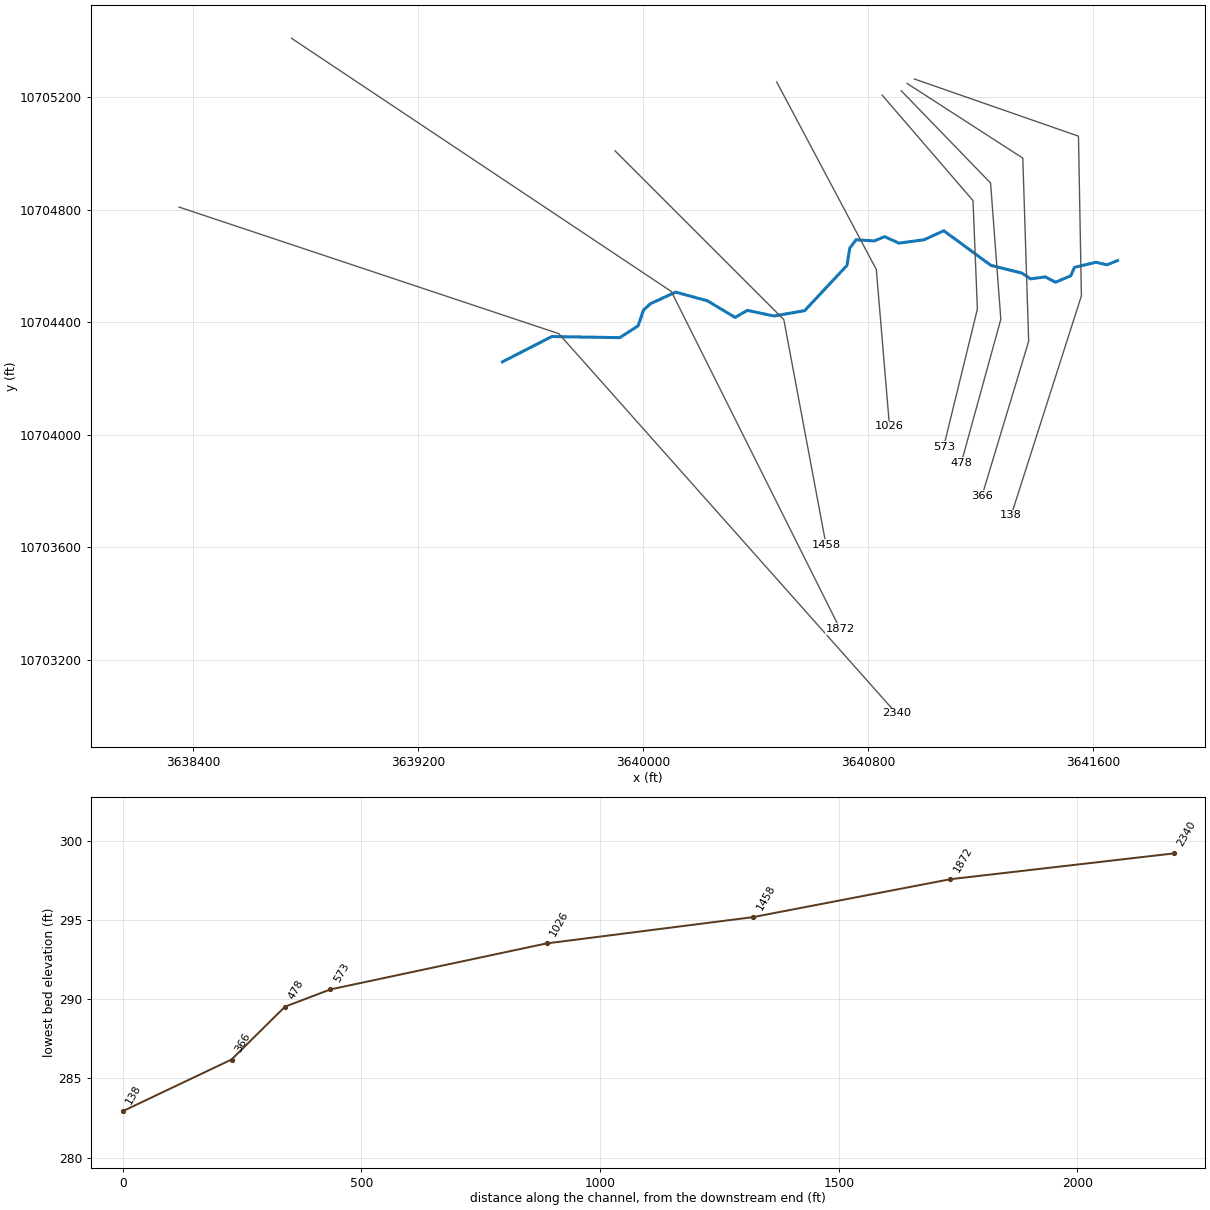
--- UNT 01588 IN LACR.prj (project) ---

Proj Title=UNT 01588 IN LACR Base Level Engineering
Current Plan=p01
Default Exp/Contr=0.3,0.1
English Units
Geom File=g01
Flow File=f01
Plan File=p01
Y Axis Title=Elevation
X Axis Title(PF)=Main Channel Distance
X Axis Title(XS)=Station
BEGIN DESCRIPTION:
UNT 01588 IN LACR
END DESCRIPTION:
DSS Export Rating Curves= 0
DSS Export Rating Curve Sorted= 0
DSS Export Volume Flow Curves= 0
DXF OffsetX= 0
DXF OffsetY= 0
DXF ScaleX= 1
DXF ScaleY= 10

--- UNT 01588 IN LACR.p01 (plan) ---

Plan Title=Multiple Run
Short Identifier=Multiple
Geom File=g01
Flow File=f01
Subcritical Flow
K Sum by GR= 0
Std Step Tol= 0.01
Critical Tol= 0.01
Num of Std Step Trials= 20
Max Error Tol= 0.3
Flow Tol Ratio= 0.001
Split Flow NTrial= 30
Split Flow Tol= 0.02
Split Flow Ratio= 0.02
Log Output Level= 0
Friction Slope Method= 1
Unsteady Friction Slope Method= 2
Unsteady Bridges Friction Slope Method= 1
Parabolic Critical Depth
Global Vel Dist=  1 , 1 , 1
Global Log Level= 0
CheckData=True
Encroach Param= -1, 0, 0, 0
BEGIN DESCRIPTION:
Multiple Run
END DESCRIPTION:

--- UNT 01588 IN LACR.f01 (steady flow) ---

Flow Title=Multiple
Program Version=4.10
Number of Profiles= 7
Profile Names=10-year,25-year,50-year,1pct_min,100-year,1pct_plu,500-year
River Rch & RM=UNT 01588 IN LAC,Reach-1         ,2340
     195     238     269     223     301     407     377
Boundary for River Rch & Prof#=UNT 01588 IN LAC,Reach-1         , 1
Up Type= 0
Dn Type= 3
Dn Slope=0.005
Boundary for River Rch & Prof#=UNT 01588 IN LAC,Reach-1         , 2
Up Type= 0
Dn Type= 3
Dn Slope=0.005
Boundary for River Rch & Prof#=UNT 01588 IN LAC,Reach-1         , 3
Up Type= 0
Dn Type= 3
Dn Slope=0.005
Boundary for River Rch & Prof#=UNT 01588 IN LAC,Reach-1         , 4
Up Type= 0
Dn Type= 3
Dn Slope=0.005
Boundary for River Rch & Prof#=UNT 01588 IN LAC,Reach-1         , 5
Up Type= 0
Dn Type= 3
Dn Slope=0.005
Boundary for River Rch & Prof#=UNT 01588 IN LAC,Reach-1         , 6
Up Type= 0
Dn Type= 3
Dn Slope=0.005
Boundary for River Rch & Prof#=UNT 01588 IN LAC,Reach-1         , 7
Up Type= 0
Dn Type= 3
Dn Slope=0.005
DSS Import GetInterval= 0
DSS Import GetPeak= 0
DSS Import FillOption= 0

--- UNT 01588 IN LACR.g01 (geometry) ---

Geom Title=Existing Conditions
Program Version=4.10

River Reach=UNT 01588 IN LAC,Reach-1
Reach XY= 30
      3639499.61     10704260.19      3639674.75       10704350.
       3639916.5       10704346.       3639981.5       10704388.
      3640000.75       10704444.        3640026.       10704467.
        3640115.       10704508.        3640228.       10704477.
      3640326.25       10704418.        3640370.       10704443.
      3640464.25       10704423.      3640573.75       10704442.
      3640724.25       10704603.        3640734.       10704664.
      3640756.25       10704694.        3640821.       10704690.
      3640858.25       10704705.        3640909.       10704682.
        3640998.       10704694.       3641068.5       10704726.
        3641236.       10704603.        3641345.       10704576.
      3641376.75       10704555.       3641429.5       10704562.
       3641465.5       10704543.      3641519.75       10704566.
        3641533.       10704596.       3641609.5       10704614.
       3641648.5       10704605.        3641686.       10704620.

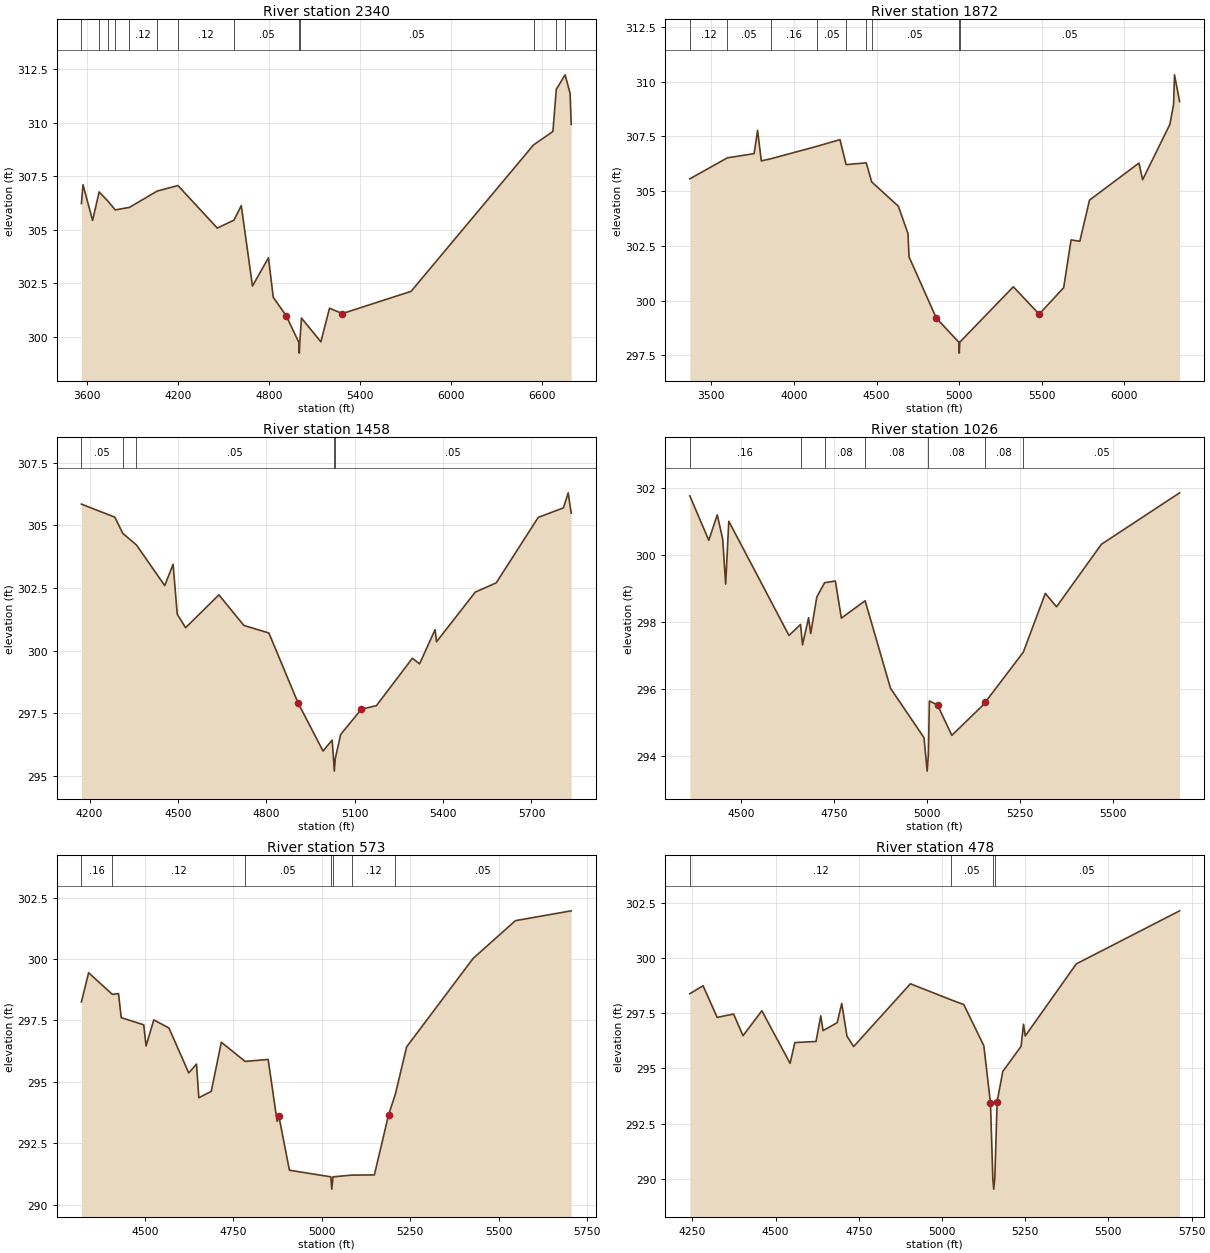
Type RM Length L Ch R = 1 ,2340    ,468,468,468
BEGIN DESCRIPTION:
UNT 01588 IN LACR 4.0
END DESCRIPTION:
XS GIS Cut Line= 3
      3638349.57      10704810.2      3639699.61     10704360.19
       3640899.6     10703010.19
#Sta/Elev= 30
  3563.3  306.23  3573.9  307.11  3637.1  305.44  3680.2  306.77  3738.5  306.34
  3786.4  305.93  3880.1  306.05  4062.6  306.81    4200  307.07  4459.3  305.08
    4569  305.45  4617.4  306.13  4691.2  302.37  4796.6  303.69  4828.3  301.84
  4912.6  300.99  4997.2  299.73  4999.9  299.23  5003.2  299.73  5014.4  300.87
  5142.3  299.76  5199.2  301.33  5283.6  301.08  5736.9  302.12  6544.1  308.97
  6672.2   309.6  6694.3  311.57  6752.5  312.25  6785.5  311.38  6792.6  309.93
#Mann= 13 ,-1 , 0
  3563.3     .05       0  3680.2     .16       0  3738.5     .12       0
  3786.4     .05       0  3880.1     .12       0  4062.6     .16       0
    4200     .12       0    4569     .05       0  4997.2     .03       0
  5003.2     .05       0  6544.1     .08       0  6694.3      .1       0
  6752.5     .08       0
Bank Sta=4912.6,5283.6
XS Rating Curve= 0 ,0
Exp/Cntr=0.3,0.1

Type RM Length L Ch R = 1 ,1872    ,414,414,414
BEGIN DESCRIPTION:
UNT 01588 IN LACR 3.0
END DESCRIPTION:
XS GIS Cut Line= 3
       3638749.6      10705410.2      3640099.61     10704510.19
      3640699.63     10703310.15
#Sta/Elev= 30
  3369.4  305.56  3596.8  306.52  3758.5  306.71  3779.5  307.77  3802.1  306.38
  3861.6  306.48  4136.2  307.04  4278.3  307.35  4315.3  306.21  4437.4  306.29
  4470.2  305.42  4631.4  304.31  4689.9  303.06    4696     302  4861.2   299.2
  4997.3   298.1    5000   297.6  5003.3   298.1  5327.3  300.63  5483.8  299.38
    5632  300.59  5676.7  302.77  5729.8  302.71  5788.5  304.59  6087.6  306.28
  6109.9  305.52  6274.9  308.05  6297.2  308.96  6302.8  310.31  6333.6  309.09
#Mann= 9 ,-1 , 0
  3369.4     .12       0  3596.8     .05       0  3861.6     .16       0
  4136.2     .05       0  4315.3     .16       0  4437.4     .08       0
  4470.2     .05       0  4997.3     .03       0  5003.3     .05       0
Bank Sta=4861.2,5483.8
XS Rating Curve= 0 ,0
Exp/Cntr=0.3,0.1

Type RM Length L Ch R = 1 ,1458    ,432,432,432
BEGIN DESCRIPTION:
UNT 01588 IN LACR 2.0
END DESCRIPTION:
XS GIS Cut Line= 3
      3639899.59     10705010.21      3640499.61     10704410.19
      3640649.61     10703610.19
#Sta/Elev= 30
  4172.4  305.85  4285.6  305.33  4313.2  304.68  4359.3  304.22  4455.3   302.6
  4483.6  303.45  4497.7  301.46    4526  300.92  4639.1  302.23    4724  301.01
  4808.8  300.71  4907.8  297.92  4992.7     296  5023.5  296.44  5028.1   295.7
  5030.9   295.2  5034.1   295.7  5052.3  296.66  5122.7  297.67  5173.6  297.81
  5295.7   299.7  5320.3  299.48  5372.8  300.84  5377.9  300.36  5509.3  302.34
  5580.5  302.71    5723  305.32  5808.6   305.7  5824.7   306.3  5834.9  305.49
#Mann= 5 ,-1 , 0
  4172.4     .05       0  4313.2     .08       0  4359.3     .05       0
  5028.1     .03       0  5034.1     .05       0
Bank Sta=4907.8,5122.7
XS Rating Curve= 0 ,0
Exp/Cntr=0.3,0.1

Type RM Length L Ch R = 1 ,1026    ,453,453,453
BEGIN DESCRIPTION:
Mapping XS 69857d91
END DESCRIPTION:
XS GIS Cut Line= 3
       3640474.3     10705255.16      3640828.48     10704588.47
      3640875.36     10704031.17
#Sta/Elev= 30
  4363.4  301.78  4414.3  300.45    4437  301.21  4451.6  300.49  4459.6  299.14
    4468  301.02  4629.5   297.6  4660.5  297.93  4665.8  297.32  4682.1  298.13
  4687.8  297.66  4704.1  298.75  4725.1  299.18    4754  299.23    4770  298.12
  4833.8  298.64  4901.9  296.02  4991.8  294.54  5000.2  293.54  5003.5  294.04
  5006.2  295.64  5028.1  295.52  5066.4  294.61    5156  295.58  5156.7  295.61
  5258.2   297.1  5317.3  298.86  5347.4  298.46  5467.8  300.33  5677.6  301.87
#Mann= 7 ,-1 , 0
  4363.4     .16       0  4660.5     .06       0  4725.1     .08       0
  4833.8     .08       0  5003.5     .08       0    5156     .08       0
  5258.2     .05       0
Bank Sta=5028.1,5156.7
XS Rating Curve= 0 ,0
Exp/Cntr=0.3,0.1

Type RM Length L Ch R = 1 ,573     ,95,95,95
BEGIN DESCRIPTION:
Mapping XS 0b450790
END DESCRIPTION:
XS GIS Cut Line= 4
      3640849.28      10705208.3      3641172.23     10704833.26
      3641187.86     10704447.85      3641068.06     10703958.24
#Sta/Elev= 30
  4320.3  298.25  4340.7  299.44  4407.7  298.56  4425.2  298.59  4432.9  297.61
  4496.5  297.32  4503.1  296.46    4525  297.52  4567.8  297.19  4623.8  295.36
  4645.7  295.72  4652.3  294.35  4687.4  294.61  4715.9  296.61  4783.2  295.83
  4848.3  295.91  4873.6  293.39  4878.6   293.6  4908.4   291.4  5025.5  291.13
  5028.2  290.63  5031.5  291.13  5084.1   291.2  5148.6  291.21  5188.6  293.65
    5208   294.5  5239.7  296.42  5427.6  300.02  5547.3  301.56    5705  301.96
#Mann= 7 ,-1 , 0
  4320.3     .16       0  4407.7     .12       0  4783.2     .05       0
  5025.5    .033       0  5031.5     .05       0  5084.1     .12       0
    5208     .05       0
Bank Sta=4878.6,5188.6
XS Rating Curve= 0 ,0
Exp/Cntr=0.3,0.1

Type RM Length L Ch R = 1 ,478     ,112,112,112
BEGIN DESCRIPTION:
Mapping XS a89afaa1
END DESCRIPTION:
XS GIS Cut Line= 4
      3640917.05     10705223.86      3641234.73     10704895.76
      3641271.19     10704411.39      3641130.56     10703900.95
#Sta/Elev= 30
    4242  298.38  4281.8  298.74  4324.2  297.31  4373.6  297.46  4401.9  296.48
  4458.5  297.61  4543.4  295.23  4557.5  296.17  4621.3  296.22  4635.5  297.38
  4642.4  296.71  4684.9  297.07  4698.6  297.94  4714.3  296.46  4734.4  295.99
  4904.9  298.83  5027.8   298.1  5065.3  297.89  5125.5  296.03  5145.5  293.45
  5152.6  290.04  5155.3  289.54  5158.6  290.04  5165.6   293.5  5182.5  294.86
  5237.5     296  5244.8     297    5250  296.47  5403.5  299.73  5713.9  302.13
#Mann= 4 ,-1 , 0
    4242     .12       0  5027.8     .05       0  5152.6     .07       0
  5158.6     .05       0
Bank Sta=5145.5,5165.6
XS Rating Curve= 0 ,0
Exp/Cntr=0.3,0.1

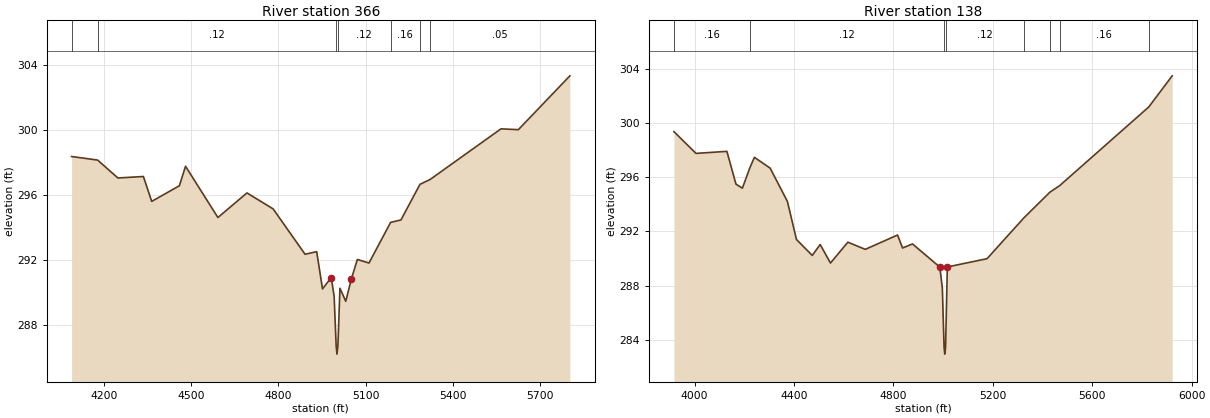
Type RM Length L Ch R = 1 ,366     ,228,228,228
BEGIN DESCRIPTION:
Mapping XS 464de35c
END DESCRIPTION:
XS GIS Cut Line= 4
      3640937.85     10705249.93      3641349.31      10704984.3
      3641370.15     10704333.26      3641204.04     10703783.02
#Sta/Elev= 30
  4087.8  298.35  4177.5  298.13  4247.3  297.03  4335.1  297.12  4363.7  295.59
  4458.9  296.55  4480.2  297.75  4591.7   294.6  4691.7  296.11  4781.8  295.13
  4891.8  292.34  4931.8   292.5  4951.9  290.21  4981.9  290.91  4991.9  289.76
  4998.9   286.7  5001.6   286.2  5004.9   286.7  5011.9  290.25  5031.9  289.45
  5051.3  290.82  5071.9  292.02  5111.9   291.8  5186.4   294.3    5222  294.45
  5287.5  296.64  5322.7  296.94  5566.4  300.05  5626.3     300  5803.7  303.31
#Mann= 7 ,-1 , 0
  4087.8     .16       0  4177.5     .12       0  4998.9     .07       0
  5004.9     .12       0  5186.4     .16       0  5287.5     .12       0
  5322.7     .05       0
Bank Sta=4981.9,5051.3
XS Rating Curve= 0 ,0
Exp/Cntr=0.3,0.1

Type RM Length L Ch R = 1 ,138     ,0,0,0
BEGIN DESCRIPTION:
UNT 01588 IN LACR 1.0
END DESCRIPTION:
XS GIS Cut Line= 4
      3640963.85     10705265.57      3641547.23     10705062.43
      3641557.65     10704494.72      3641307.92     10703714.34
#Sta/Elev= 30
  3916.8  299.37  4005.7  297.76  4130.1  297.91  4166.5  295.49  4192.3  295.19
  4222.4  296.69  4240.6  297.47  4304.1  296.67  4373.5  294.21    4410   291.4
  4473.5  290.22  4505.3  291.03  4546.8  289.66  4616.8   291.2  4686.8  290.67
  4816.8  291.73  4836.8  290.77  4876.8  291.07  4986.8  289.36  4996.9  287.81
  5003.9  283.43  5006.6  282.93  5009.9  283.43  5016.9  289.37  5176.6  289.98
  5325.2     293  5429.4  294.89  5469.1  295.38  5827.5  301.19  5921.7  303.49
#Mann= 8 ,-1 , 0
  3916.8     .16       0  4222.4     .12       0  5003.9     .07       0
  5009.9     .12       0  5325.2     .16       0  5429.4     .12       0
  5469.1     .16       0  5827.5     .05       0
Bank Sta=4986.8,5016.9
XS Rating Curve= 0 ,0
Exp/Cntr=0.3,0.1

Chan Stop Cuts=-1
Use User Specified Reach Order=0
Composite Channel Slope=5