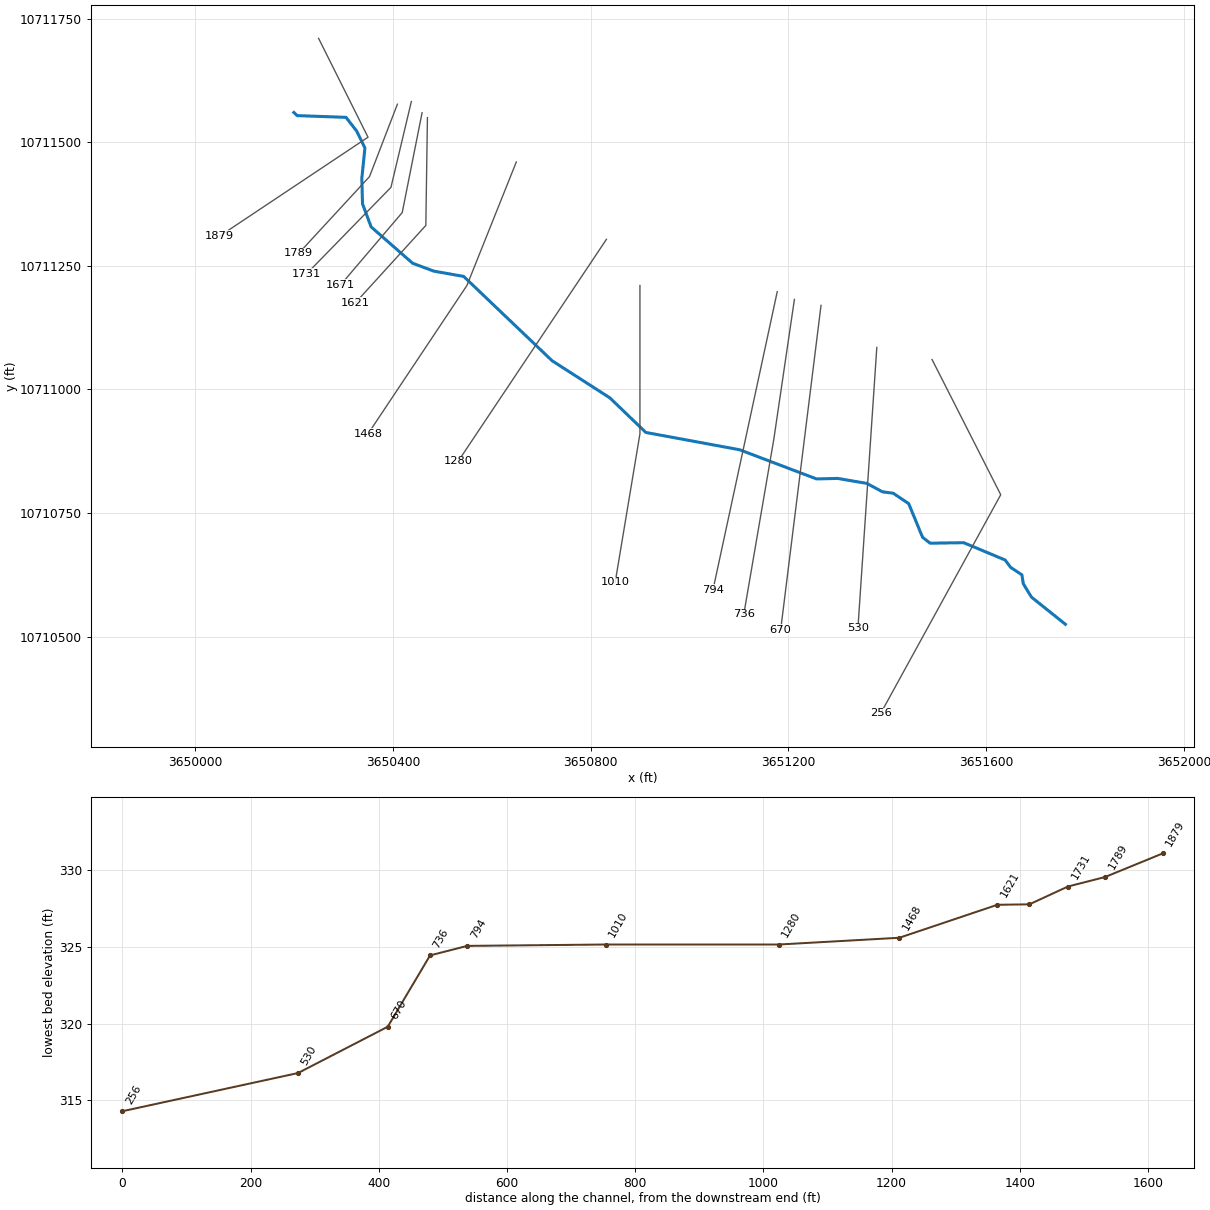
--- UNT 01613 IN LACR.prj (project) ---

Proj Title=UNT 01613 IN LACR Base Level Engineering
Current Plan=p01
Default Exp/Contr=0.3,0.1
English Units
Geom File=g01
Flow File=f01
Plan File=p01
Y Axis Title=Elevation
X Axis Title(PF)=Main Channel Distance
X Axis Title(XS)=Station
BEGIN DESCRIPTION:
UNT 01613 IN LACR
END DESCRIPTION:
DSS Export Rating Curves= 0
DSS Export Rating Curve Sorted= 0
DSS Export Volume Flow Curves= 0
DXF OffsetX= 0
DXF OffsetY= 0
DXF ScaleX= 1
DXF ScaleY= 10

--- UNT 01613 IN LACR.p01 (plan) ---

Plan Title=Multiple Run
Short Identifier=Multiple
Geom File=g01
Flow File=f01
Subcritical Flow
K Sum by GR= 0
Std Step Tol= 0.01
Critical Tol= 0.01
Num of Std Step Trials= 20
Max Error Tol= 0.3
Flow Tol Ratio= 0.001
Split Flow NTrial= 30
Split Flow Tol= 0.02
Split Flow Ratio= 0.02
Log Output Level= 0
Friction Slope Method= 1
Unsteady Friction Slope Method= 2
Unsteady Bridges Friction Slope Method= 1
Parabolic Critical Depth
Global Vel Dist=  1 , 1 , 1
Global Log Level= 0
CheckData=True
Encroach Param= -1, 0, 0, 0
BEGIN DESCRIPTION:
Multiple Run
END DESCRIPTION:

--- UNT 01613 IN LACR.f01 (steady flow) ---

Flow Title=Multiple
Program Version=4.10
Number of Profiles= 7
Profile Names=10-year,25-year,50-year,1pct_min,100-year,1pct_plu,500-year
River Rch & RM=UNT 01613 IN LAC,Reach-1         ,1879
     134     165     188     159     214     290     278
Boundary for River Rch & Prof#=UNT 01613 IN LAC,Reach-1         , 1
Up Type= 0
Dn Type= 3
Dn Slope=0.005
Boundary for River Rch & Prof#=UNT 01613 IN LAC,Reach-1         , 2
Up Type= 0
Dn Type= 3
Dn Slope=0.005
Boundary for River Rch & Prof#=UNT 01613 IN LAC,Reach-1         , 3
Up Type= 0
Dn Type= 3
Dn Slope=0.005
Boundary for River Rch & Prof#=UNT 01613 IN LAC,Reach-1         , 4
Up Type= 0
Dn Type= 3
Dn Slope=0.005
Boundary for River Rch & Prof#=UNT 01613 IN LAC,Reach-1         , 5
Up Type= 0
Dn Type= 3
Dn Slope=0.005
Boundary for River Rch & Prof#=UNT 01613 IN LAC,Reach-1         , 6
Up Type= 0
Dn Type= 3
Dn Slope=0.005
Boundary for River Rch & Prof#=UNT 01613 IN LAC,Reach-1         , 7
Up Type= 0
Dn Type= 3
Dn Slope=0.005
DSS Import GetInterval= 0
DSS Import GetPeak= 0
DSS Import FillOption= 0

--- UNT 01613 IN LACR.g01 (geometry) ---

Geom Title=Existing Conditions
Program Version=4.10

River Reach=UNT 01613 IN LAC,Reach-1
Reach XY= 30
      3650199.61     10711560.19      3650206.18     10711553.85
      3650305.14     10711550.34      3650326.67     10711522.56
      3650343.34     10711488.53      3650337.09     10711426.73
      3650338.48     10711375.34      3650355.84     10711328.81
      3650439.87      10711255.2      3650482.92     10711239.23
      3650543.08     10711228.62        3650722.       10711058.
      3650838.75       10710983.       3650911.5       10710913.
      3651101.25       10710878.      3651256.75       10710819.
       3651299.5       10710820.       3651358.5       10710810.
        3651390.       10710793.        3651412.       10710790.
      3651443.25       10710769.      3651471.25       10710701.
       3651486.5       10710689.       3651554.5       10710690.
      3651638.25       10710655.       3651649.5       10710640.
      3651672.25       10710625.        3651675.       10710607.
       3651691.5       10710580.      3651760.25       10710525.

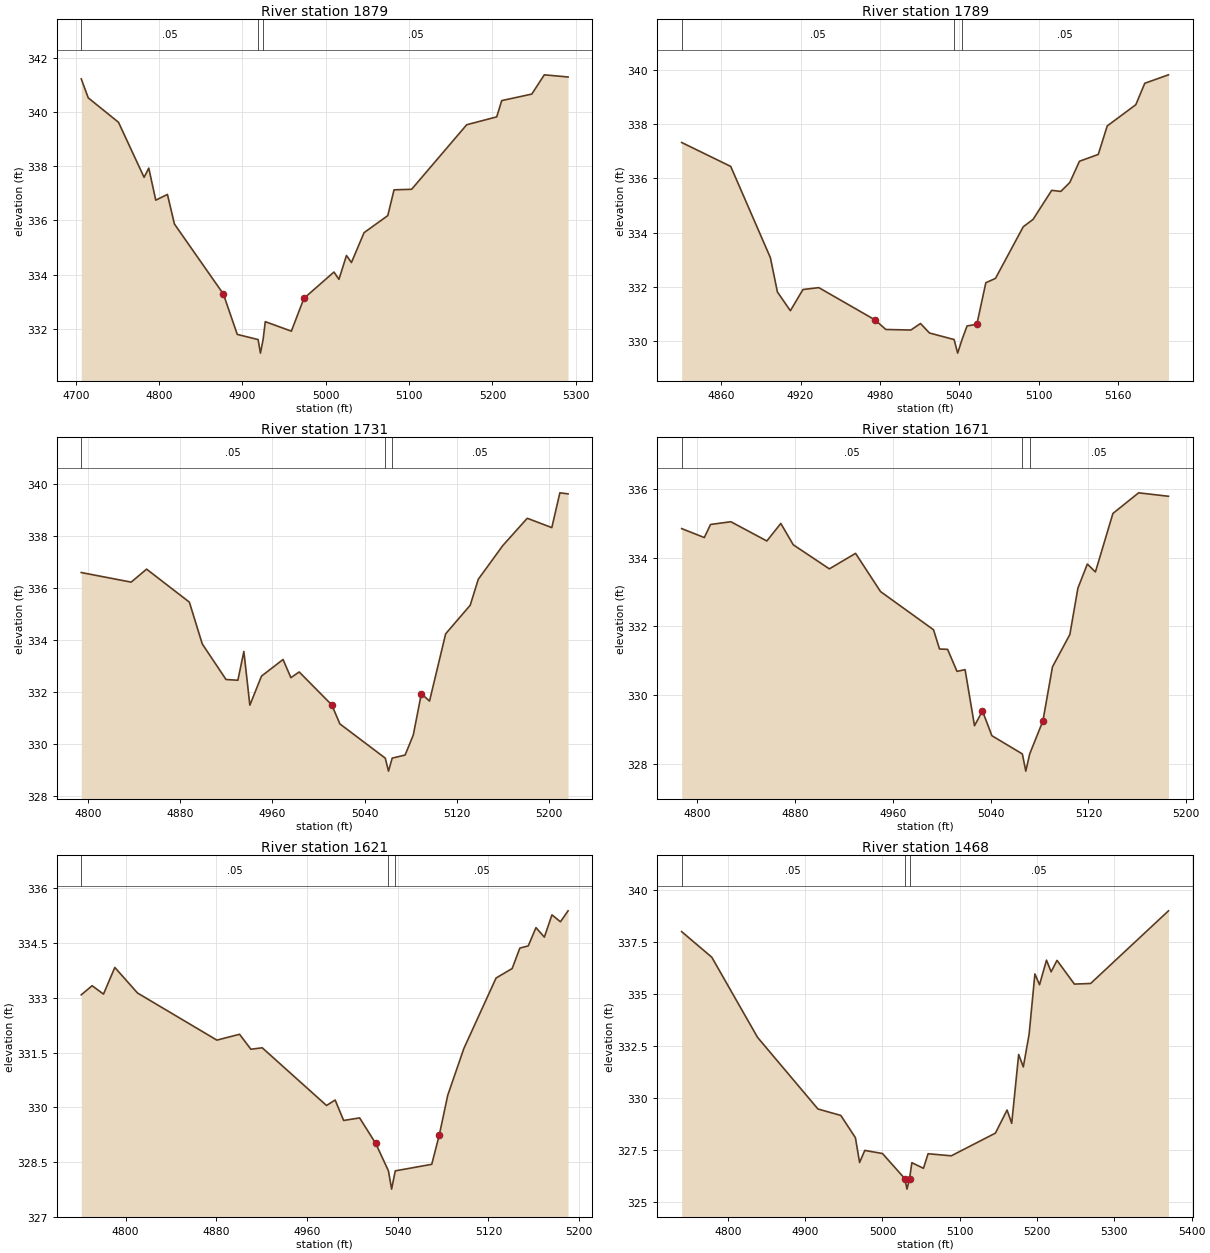
Type RM Length L Ch R = 1 ,1879    ,90,90,90
BEGIN DESCRIPTION:
UNT 01613 IN LACR 4.0
END DESCRIPTION:
XS GIS Cut Line= 3
      3650249.62     10711710.17      3650349.61     10711510.19
      3650049.64     10711310.21
#Sta/Elev= 30
  4706.6  341.22    4715  340.52  4751.3  339.62    4782  337.59  4787.6  337.93
    4796  336.75    4810  336.96  4818.4  335.87  4877.1  333.29  4893.8   331.8
  4918.8  331.61  4921.6  331.11  4924.8  331.61  4927.4  332.27  4958.7  331.92
  4973.8  333.13  5009.8   334.1  5015.8  333.83  5024.8  334.71  5030.8  334.45
  5045.9  335.55  5074.4  336.18  5081.9  337.13    5103  337.15  5169.1  339.53
  5205.1  339.82  5211.1  340.42  5247.2  340.66  5262.2  341.37  5290.7  341.29
#Mann= 3 ,-1 , 0
  4706.6     .05       0  4918.8     .03       0  4924.8     .05       0
Bank Sta=4877.1,4973.8
XS Rating Curve= 0 ,0
Exp/Cntr=0.3,0.1

Type RM Length L Ch R = 1 ,1789    ,58,58,58
BEGIN DESCRIPTION:
Mapping XS 98d84fc1
END DESCRIPTION:
XS GIS Cut Line= 3
      3650409.04     10711576.93      3650352.61     10711430.45
      3650209.41     10711275.31
#Sta/Elev= 30
  4830.1  337.32  4867.2  336.44  4897.2  333.08  4902.5  331.82  4912.3  331.13
  4921.8  331.91  4933.8  331.98  4976.4  330.79  4984.5  330.44  5003.4  330.42
  5010.7  330.66  5017.5  330.31  5036.1  330.07  5038.8  329.57  5042.1  330.07
  5045.9  330.57  5053.3  330.63  5060.1  332.16  5067.4  332.32  5088.4  334.22
  5095.8  334.49  5109.9  335.56  5116.8  335.52  5123.6  335.85  5130.9  336.63
  5145.1  336.88  5151.9  337.93  5173.5  338.71  5180.3   339.5  5198.2  339.81
#Mann= 3 ,-1 , 0
  4830.1     .05       0  5036.1     .03       0  5042.1     .05       0
Bank Sta=4976.4,5053.3
XS Rating Curve= 0 ,0
Exp/Cntr=0.3,0.1

Type RM Length L Ch R = 1 ,1731    ,60,60,60
BEGIN DESCRIPTION:
Mapping XS 50b6a5a0
END DESCRIPTION:
XS GIS Cut Line= 3
      3650437.25     10711582.36      3650396.02     10711408.75
      3650225.68     10711234.11
#Sta/Elev= 30
  4794.1   336.6  4837.4  336.23  4850.8  336.73  4887.9  335.46  4899.1  333.85
  4919.7  332.48    4930  332.45  4935.2  333.56  4940.4  331.49  4950.5  332.61
  4969.2  333.25    4976  332.55  4983.2  332.77  5011.5   331.5  5018.5  330.77
  5057.9  329.45  5060.7  328.95  5063.9  329.45  5075.1  329.57  5082.2  330.34
  5089.2  331.93  5096.3  331.65  5110.3  334.24  5131.6  335.34  5138.6  336.34
  5159.9  337.64  5181.1  338.69  5202.4  338.33  5209.4  339.67  5216.5  339.63
#Mann= 3 ,-1 , 0
  4794.1     .05       0  5057.9     .03       0  5063.9     .05       0
Bank Sta=5011.5,5089.2
XS Rating Curve= 0 ,0
Exp/Cntr=0.3,0.1

Type RM Length L Ch R = 1 ,1671    ,50,50,50
BEGIN DESCRIPTION:
Mapping XS 692a16e8
END DESCRIPTION:
XS GIS Cut Line= 3
      3650458.95     10711559.59       3650418.8     10711357.75
      3650294.29     10711211.59
#Sta/Elev= 30
  4787.6  334.84  4806.1  334.58  4811.2  334.96  4827.8  335.04  4857.2  334.48
  4868.6  334.99  4878.8  334.37  4908.3  333.67  4929.7  334.12  4950.1  333.01
  4993.4   331.9  4998.3  331.34  5004.9  331.33  5012.6  330.69  5019.2  330.74
  5026.9  329.11  5033.4  329.54  5041.1  328.82    5066  328.29  5068.8  327.79
    5072  328.29  5082.8  329.25  5090.6  330.82  5104.8  331.76  5111.4  333.11
  5119.1  333.81  5125.7  333.58    5140  335.28    5161  335.88  5185.4  335.78
#Mann= 3 ,-1 , 0
  4787.6     .05       0    5066     .03       0    5072     .05       0
Bank Sta=5033.4,5082.8
XS Rating Curve= 0 ,0
Exp/Cntr=0.3,0.1

Type RM Length L Ch R = 1 ,1621    ,153,153,153
BEGIN DESCRIPTION:
Mapping XS 10a1d44d
END DESCRIPTION:
XS GIS Cut Line= 3
       3650469.8     10711549.76      3650466.55     10711331.71
      3650324.35     10711175.52
#Sta/Elev= 30
  4760.9  333.08  4770.5  333.33  4780.5   333.1  4790.5  333.83  4810.5  333.13
  4880.5  331.84  4900.5     332  4910.5  331.59  4920.5  331.63  4977.2  330.05
  4984.8   330.2  4992.3  329.64  5006.4  329.71  5020.6  329.01  5031.8  328.26
  5034.6  327.76  5037.8  328.26    5070  328.44  5076.7  329.25  5084.1  330.33
  5098.3  331.61  5126.7  333.54  5140.9   333.8  5147.7  334.36  5155.1  334.42
  5161.9  334.92  5169.3  334.66    5176  335.27  5183.5  335.08  5190.2  335.38
#Mann= 3 ,-1 , 0
  4760.9     .05       0  5031.8     .03       0  5037.8     .05       0
Bank Sta=5020.6,5076.7
XS Rating Curve= 0 ,0
Exp/Cntr=0.3,0.1

Type RM Length L Ch R = 1 ,1468    ,188,188,188
BEGIN DESCRIPTION:
UNT 01613 IN LACR 3.0
END DESCRIPTION:
XS GIS Cut Line= 3
       3650649.6     10711460.16      3650549.61     10711210.19
       3650349.6     10710910.17
#Sta/Elev= 30
  4740.2  337.98  4779.2  336.75  4838.4   332.9  4916.5  329.46  4946.1  329.15
    4965  328.08  4970.4  326.89  4977.1  327.47    5000  327.32    5029  326.11
  5031.7  325.61    5035  326.11    5038  326.88    5053  326.61    5059  327.31
    5089  327.21  5146.1   328.3  5161.2  329.41  5167.2  328.77  5176.2  332.08
  5182.2  331.48  5189.7  333.05  5197.2  335.95  5203.2  335.43  5212.2  336.61
  5218.2  336.05  5225.8   336.6  5248.3  335.46  5269.3  335.49    5370  338.98
#Mann= 3 ,-1 , 0
  4740.2     .05       0    5029     .03       0    5035     .05       0
Bank Sta=5029,5035
XS Rating Curve= 0 ,0
Exp/Cntr=0.3,0.1

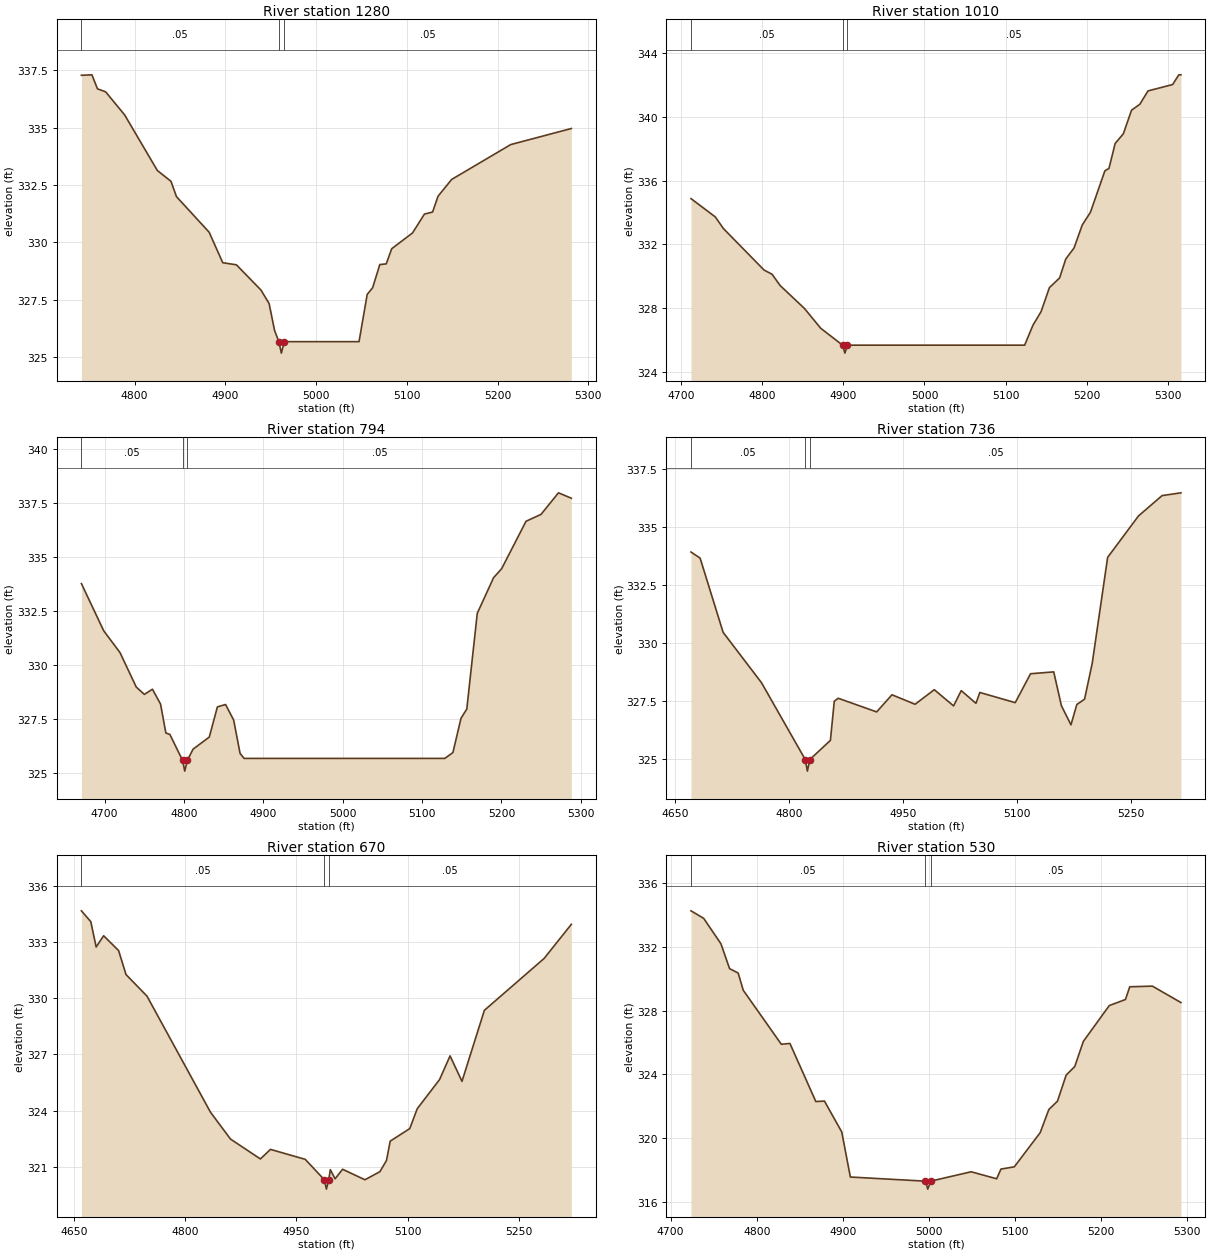
Type RM Length L Ch R = 1 ,1280    ,270,270,270
BEGIN DESCRIPTION:
Mapping XS 74fc9900
END DESCRIPTION:
XS GIS Cut Line= 2
      3650831.88     10711303.66      3650531.94     10710854.62
#Sta/Elev= 30
  4741.3  337.28  4752.9   337.3    4759  336.69    4768  336.56    4789  335.55
    4825  333.13    4840  332.66  4846.1  331.99  4882.1  330.44  4897.1  329.11
  4912.1  329.02  4939.2  327.92  4948.2  327.33  4954.2  326.16  4958.9  325.67
  4961.7  325.17  4964.9  325.67  5047.3  325.67  5056.3  327.73  5062.3  328.02
  5070.2  329.03  5077.3  329.06  5083.3  329.72  5106.3  330.41  5119.4  331.23
  5128.4  331.32  5134.4  332.01  5149.4  332.74  5214.5  334.26  5281.3  334.96
#Mann= 3 ,-1 , 0
  4741.3     .05       0  4958.9     .03       0  4964.9     .05       0
Bank Sta=4958.9,4964.9
XS Rating Curve= 0 ,0
Exp/Cntr=0.3,0.1

Type RM Length L Ch R = 1 ,1010    ,216,216,216
BEGIN DESCRIPTION:
UNT 01613 IN LACR 2.0
END DESCRIPTION:
XS GIS Cut Line= 3
      3650899.61     10711210.22      3650899.61     10710910.19
       3650849.6     10710610.16
#Sta/Elev= 30
  4712.1  334.87  4742.1  333.72  4752.1  332.99  4802.1  330.39  4812.1  330.12
  4822.1  329.41  4852.1  327.97  4872.1  326.73  4899.1  325.67  4901.9  325.17
  4905.1  325.67  5123.6  325.67  5133.8  326.92  5143.9  327.78  5154.1  329.28
  5166.7  329.89  5174.3  331.08  5184.5  331.77  5194.6  333.21  5204.7  334.01
  5222.5  336.61  5227.6  336.77  5235.2  338.33  5245.3  338.94  5255.4  340.42
  5265.6  340.79  5275.7  341.63  5306.1  342.03  5313.7  342.64  5316.3  342.64
#Mann= 3 ,-1 , 0
  4712.1     .05       0  4899.1    .033       0  4905.1     .05       0
Bank Sta=4899.1,4905.1
XS Rating Curve= 0 ,0
Exp/Cntr=0.3,0.1

Type RM Length L Ch R = 1 ,794     ,58,58,58
BEGIN DESCRIPTION:
Mapping XS 7384631a
END DESCRIPTION:
XS GIS Cut Line= 2
      3651177.34     10711197.69      3651047.31     10710594.34
#Sta/Elev= 30
  4670.9  333.78    4699  331.59  4719.5  330.58    4740  328.98  4750.2  328.64
  4760.4  328.88  4770.6  328.19  4777.3  326.85  4782.4  326.78  4798.3  325.58
  4801.1  325.08  4804.3  325.58  4811.6   326.1    4832  326.66  4842.2  328.06
  4852.5  328.17  4862.7  327.45  4870.8   325.9  4875.9  325.67  5128.7  325.67
  5138.9  325.94  5149.1  327.53  5156.4  327.96  5169.6   332.4  5190.1  334.05
  5200.3  334.47    5231  336.67  5249.9  336.99  5271.9  337.99  5288.1  337.74
#Mann= 3 ,-1 , 0
  4670.9     .05       0  4798.3    .035       0  4804.3     .05       0
Bank Sta=4798.3,4804.3
XS Rating Curve= 0 ,0
Exp/Cntr=0.3,0.1

Type RM Length L Ch R = 1 ,736     ,66,66,66
BEGIN DESCRIPTION:
Mapping XS 3bebc0a0
END DESCRIPTION:
XS GIS Cut Line= 3
      3651212.07     10711182.07      3651170.41     10710899.13
      3651109.67     10710545.09
#Sta/Elev= 30
  4671.1  333.93  4683.1  333.67  4713.4  330.46    4764  328.28  4821.6  324.96
  4824.4  324.46  4827.6  324.96  4854.7  325.79  4859.8  327.48    4865  327.61
  4915.6  327.02  4935.8  327.76  4966.2  327.35  4991.5  327.98  5016.9  327.28
    5027  327.94  5046.4  327.39  5051.5  327.86  5098.1  327.42  5118.3  328.67
  5148.8  328.75  5158.9  327.29  5171.5  326.46  5179.2  327.34  5189.4  327.57
  5199.5  329.12  5219.8   333.7  5260.4  335.49  5291.5  336.37  5316.3  336.49
#Mann= 3 ,-1 , 0
  4671.1     .05       0  4821.6     .03       0  4827.6     .05       0
Bank Sta=4821.6,4827.6
XS Rating Curve= 0 ,0
Exp/Cntr=0.3,0.1

Type RM Length L Ch R = 1 ,670     ,140,140,140
BEGIN DESCRIPTION:
Mapping XS f3b6b648
END DESCRIPTION:
XS GIS Cut Line= 2
       3651265.9     10711169.98       3651184.3     10710513.73
#Sta/Elev= 30
  4659.7  334.66  4672.4  334.08  4679.6  332.73  4689.7  333.33  4709.9  332.54
  4719.9  331.26  4748.2  330.11    4834  323.91    4861  322.48  4901.3  321.42
  4914.9  321.93  4961.8   321.4  4987.6  320.31  4990.4  319.81  4993.6  320.31
  4995.7  320.85  5002.1  320.36  5012.2  320.87  5042.4  320.31  5062.6  320.74
  5071.5  321.34  5076.5  322.37  5102.9  323.04    5113   324.1  5143.2  325.66
  5157.3  326.92  5173.4  325.56  5203.6  329.35  5284.3  332.12    5321  333.94
#Mann= 3 ,-1 , 0
  4659.7     .05       0  4987.6     .03       0  4993.6     .05       0
Bank Sta=4987.6,4993.6
XS Rating Curve= 0 ,0
Exp/Cntr=0.3,0.1

Type RM Length L Ch R = 1 ,530     ,274,274,274
BEGIN DESCRIPTION:
Mapping XS 2076aa23
END DESCRIPTION:
XS GIS Cut Line= 2
      3651378.74     10711084.87      3651340.54     10710517.15
#Sta/Elev= 30
  4723.6  334.27  4738.3   333.8  4758.4   332.2  4768.4  330.64  4778.4  330.36
  4784.3  329.28  4828.5  325.89  4838.5  325.94  4868.6  322.29  4878.6  322.32
  4898.7  320.38  4908.7  317.55  4995.9  317.29  4998.6  316.79  5001.9  317.29
    5049  317.88  5078.6  317.44  5083.6  318.05  5099.1  318.19  5129.2  320.34
  5139.2  321.79  5149.2  322.31  5159.3  323.95  5169.3  324.49  5179.3  326.07
  5209.4  328.32  5228.2   328.7  5233.2   329.5  5259.5  329.54  5292.6  328.51
#Mann= 3 ,-1 , 0
  4723.6     .05       0  4995.9     .03       0  5001.9     .05       0
Bank Sta=4995.9,5001.9
XS Rating Curve= 0 ,0
Exp/Cntr=0.3,0.1

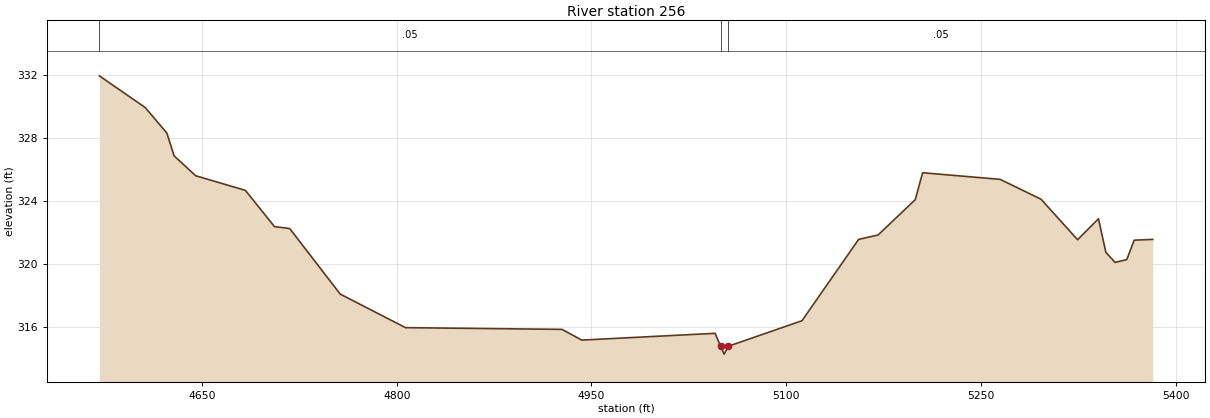
Type RM Length L Ch R = 1 ,256     ,0,0,0
BEGIN DESCRIPTION:
UNT 01613 IN LACR 1.0
END DESCRIPTION:
XS GIS Cut Line= 3
      3651490.52     10711060.45      3651629.41     10710787.01
      3651386.61     10710344.77
#Sta/Elev= 30
    4571  331.96  4606.3  329.95    4623  328.33  4628.6  326.88  4645.2  325.62
  4683.5  324.69  4705.9  322.39  4717.6  322.27  4756.5  318.11  4806.8  315.98
  4927.3  315.87  4942.5  315.19  5045.2  315.62  5049.4   314.8  5052.1   314.3
  5055.4   314.8  5112.1  316.42  5155.7  321.58  5170.7  321.86  5199.3   324.1
    5205  325.81  5264.7  325.39  5296.2  324.13  5324.3  321.56  5340.4  322.89
  5346.1  320.76  5353.2  320.12  5362.2   320.3  5367.9  321.53  5382.2  321.58
#Mann= 3 ,-1 , 0
    4571     .05       0  5049.4     .03       0  5055.4     .05       0
Bank Sta=5049.4,5055.4
XS Rating Curve= 0 ,0
Exp/Cntr=0.3,0.1
Stream Node=UNT 01613 IN LAC,Reach-1         , 0 , 0 ,Upstream end
Stream Node=UNT 01613 IN LAC,Reach-1         , 0 , 1 ,Downstream end

Chan Stop Cuts=-1
Use User Specified Reach Order=0
Composite Channel Slope=5