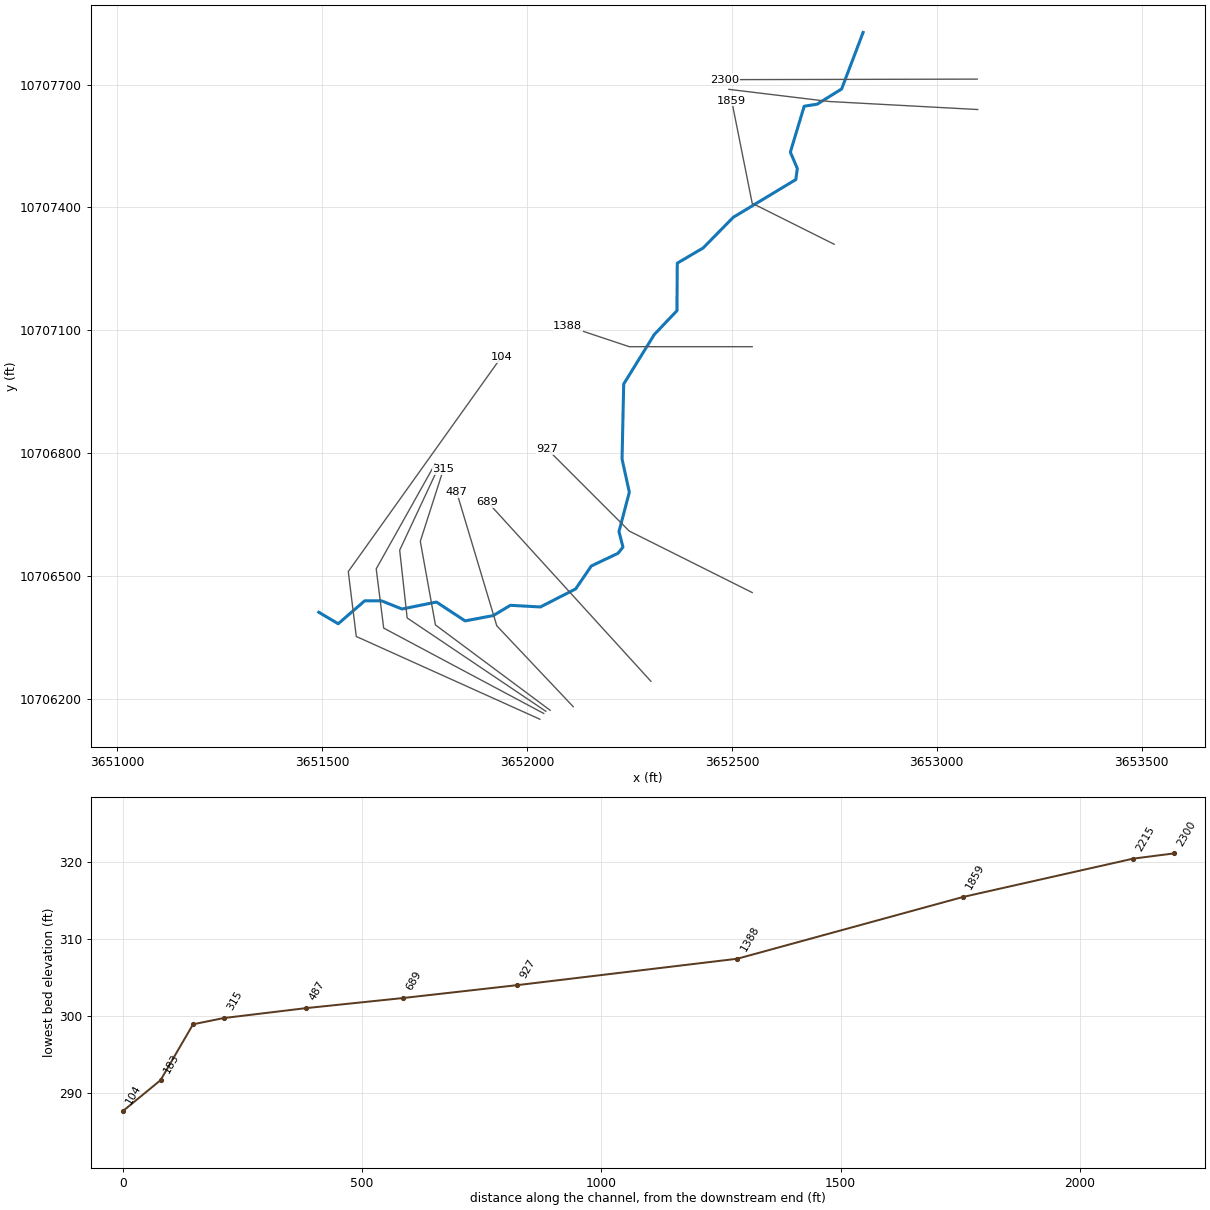
--- UNT 01616 IN LACR.prj (project) ---

Proj Title=UNT 01616 IN LACR Base Level Engineering
Current Plan=p01
Default Exp/Contr=0.3,0.1
English Units
Geom File=g01
Flow File=f01
Plan File=p01
Y Axis Title=Elevation
X Axis Title(PF)=Main Channel Distance
X Axis Title(XS)=Station
BEGIN DESCRIPTION:
UNT 01616 IN LACR
END DESCRIPTION:
DSS Export Rating Curves= 0
DSS Export Rating Curve Sorted= 0
DSS Export Volume Flow Curves= 0
DXF OffsetX= 0
DXF OffsetY= 0
DXF ScaleX= 1
DXF ScaleY= 10

--- UNT 01616 IN LACR.p01 (plan) ---

Plan Title=Multiple Run
Short Identifier=Multiple
Geom File=g01
Flow File=f01
Subcritical Flow
K Sum by GR= 0
Std Step Tol= 0.01
Critical Tol= 0.01
Num of Std Step Trials= 20
Max Error Tol= 0.3
Flow Tol Ratio= 0.001
Split Flow NTrial= 30
Split Flow Tol= 0.02
Split Flow Ratio= 0.02
Log Output Level= 0
Friction Slope Method= 1
Unsteady Friction Slope Method= 2
Unsteady Bridges Friction Slope Method= 1
Parabolic Critical Depth
Global Vel Dist=  1 , 1 , 1
Global Log Level= 0
CheckData=True
Encroach Param= -1, 0, 0, 0
BEGIN DESCRIPTION:
Multiple Run
END DESCRIPTION:

--- UNT 01616 IN LACR.f01 (steady flow) ---

Flow Title=Multiple
Program Version=4.10
Number of Profiles= 7
Profile Names=10-year,25-year,50-year,1pct_min,100-year,1pct_plu,500-year
River Rch & RM=UNT 01616 IN LAC,Reach-1         ,2300
     247     323     384     338     457     618     646
Boundary for River Rch & Prof#=UNT 01616 IN LAC,Reach-1         , 1
Up Type= 0
Dn Type= 3
Dn Slope=0.005
Boundary for River Rch & Prof#=UNT 01616 IN LAC,Reach-1         , 2
Up Type= 0
Dn Type= 3
Dn Slope=0.005
Boundary for River Rch & Prof#=UNT 01616 IN LAC,Reach-1         , 3
Up Type= 0
Dn Type= 3
Dn Slope=0.005
Boundary for River Rch & Prof#=UNT 01616 IN LAC,Reach-1         , 4
Up Type= 0
Dn Type= 3
Dn Slope=0.005
Boundary for River Rch & Prof#=UNT 01616 IN LAC,Reach-1         , 5
Up Type= 0
Dn Type= 3
Dn Slope=0.005
Boundary for River Rch & Prof#=UNT 01616 IN LAC,Reach-1         , 6
Up Type= 0
Dn Type= 3
Dn Slope=0.005
Boundary for River Rch & Prof#=UNT 01616 IN LAC,Reach-1         , 7
Up Type= 0
Dn Type= 3
Dn Slope=0.005
DSS Import GetInterval= 0
DSS Import GetPeak= 0
DSS Import FillOption= 0

--- UNT 01616 IN LACR.g01 (geometry) ---

Geom Title=Existing Conditions
Program Version=4.10

River Reach=UNT 01616 IN LAC,Reach-1
Reach XY= 30
      3652820.25       10707827.      3652767.75       10707689.
        3652708.       10707652.       3652676.5       10707647.
      3652642.75       10707535.      3652659.75       10707495.
        3652656.       10707468.       3652503.5       10707376.
      3652429.75       10707301.      3652366.75       10707264.
        3652366.       10707148.      3652310.75       10707090.
        3652236.       10706969.        3652232.       10706786.
      3652249.75       10706705.       3652224.5       10706609.
      3652234.25       10706571.      3652222.25       10706556.
        3652157.       10706525.      3652118.75       10706469.
      3652032.75       10706425.       3651959.5       10706429.
      3651917.75       10706404.        3651849.       10706391.
        3651779.       10706437.        3651695.       10706420.
      3651644.75       10706440.        3651604.       10706440.
      3651539.25       10706384.        3651492.       10706412.

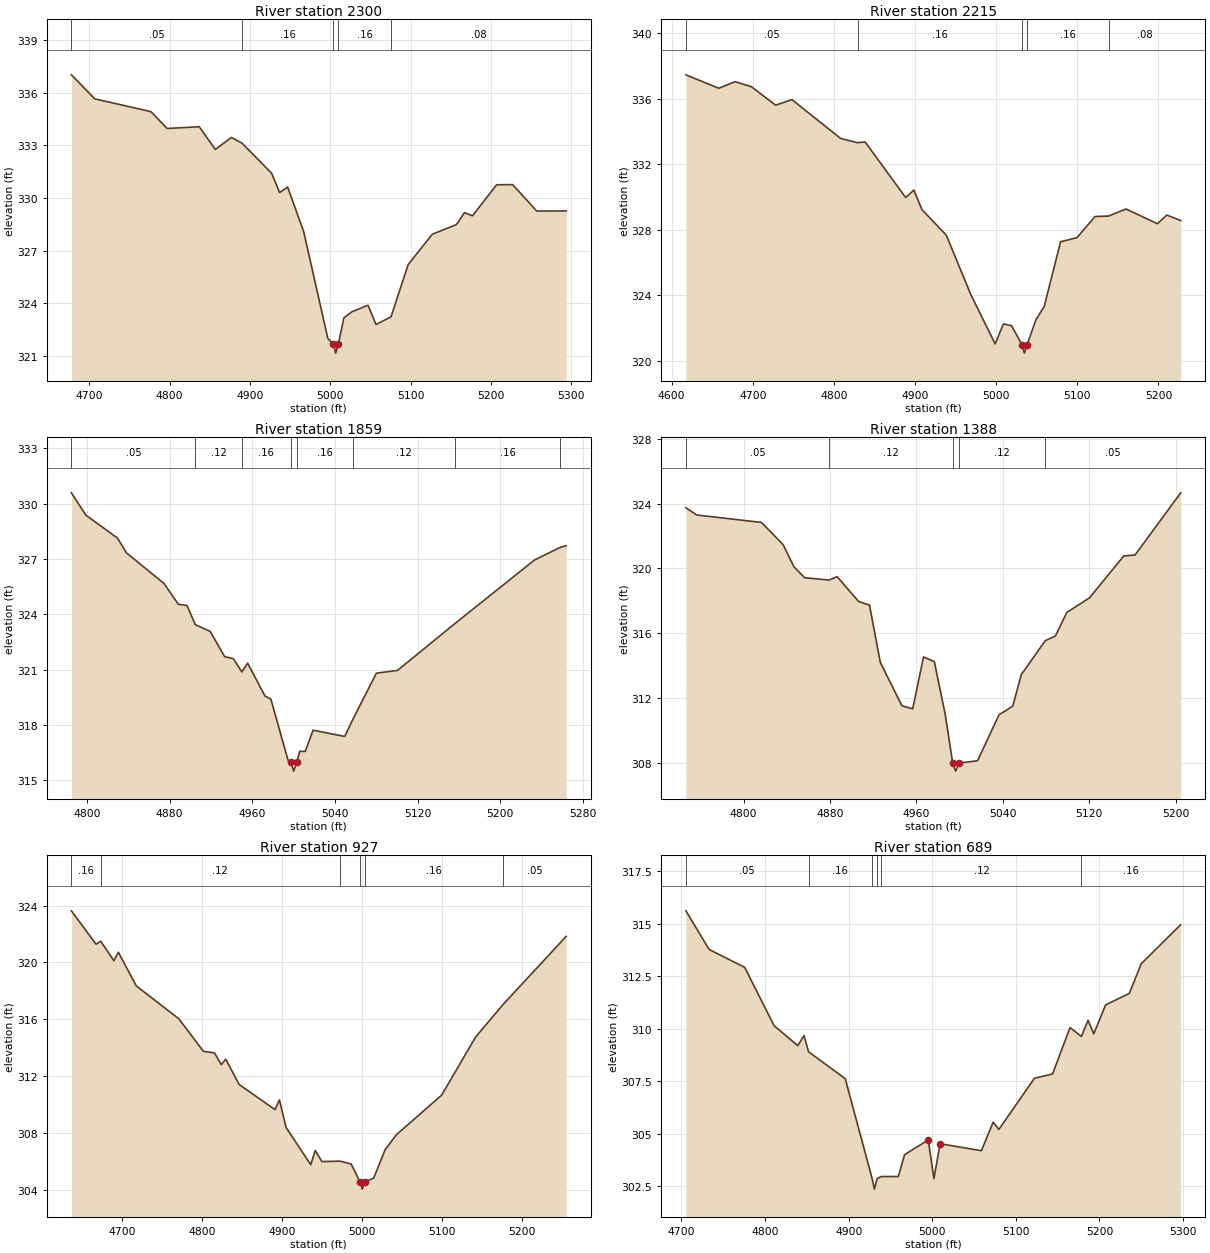
Type RM Length L Ch R = 1 ,2300    ,85,85,85
BEGIN DESCRIPTION:
UNT 01616 IN LACR 5.0
END DESCRIPTION:
XS GIS Cut Line= 2
      3653098.73     10707713.18      3652483.03     10707711.88
#Sta/Elev= 30
  4677.8  337.03  4706.9  335.66  4776.9  334.93  4796.9  333.97  4836.9  334.07
  4856.9  332.77  4876.9  333.46  4890.2  333.13  4926.9  331.42  4936.9  330.32
  4946.9  330.63  4966.9  328.08  4996.9     322  5003.9  321.66  5006.7  321.16
  5009.9  321.66  5016.9  323.17  5026.9  323.52  5046.9  323.89  5056.9  322.79
  5075.5  323.23  5096.9  326.21  5126.9  327.94  5156.9  328.49  5166.9  329.17
  5176.9  328.99  5206.9  330.76  5226.9  330.77  5256.9  329.26  5293.5  329.27
#Mann= 5 ,-1 , 0
  4677.8     .05       0  4890.2     .16       0  5003.9     .07       0
  5009.9     .16       0  5075.5     .08       0
Bank Sta=5003.9,5009.9
XS Rating Curve= 0 ,0
Exp/Cntr=0.3,0.1

Type RM Length L Ch R = 1 ,2215    ,356,356,356
BEGIN DESCRIPTION:
Mapping XS d70064c8
END DESCRIPTION:
XS GIS Cut Line= 3
      3653100.06     10707638.96      3652738.04     10707658.49
      3652492.67     10707688.19
#Sta/Elev= 30
  4617.7  337.45  4658.2  336.63  4678.2  337.03  4698.3  336.73  4728.3   335.6
  4748.3  335.94  4808.4  333.57  4829.3  333.31  4838.5  333.36  4888.5  329.97
  4898.6  330.42  4908.6  329.23  4938.6  327.67  4968.7  324.06  4998.8  321.04
  5008.9  322.26    5019  322.15    5032  320.98  5034.8  320.48    5038  320.98
  5049.2  322.53  5059.2  323.32  5079.4  327.27  5099.5  327.52    5122  328.81
  5138.7  328.84    5160  329.27  5198.8  328.37  5210.3   328.9  5227.4  328.57
#Mann= 5 ,-1 , 0
  4617.7     .05       0  4829.3     .16       0    5032     .07       0
    5038     .16       0  5138.7     .08       0
Bank Sta=5032,5038
XS Rating Curve= 0 ,0
Exp/Cntr=0.3,0.1

Type RM Length L Ch R = 1 ,1859    ,471,471,471
BEGIN DESCRIPTION:
UNT 01616 IN LACR 4.0
END DESCRIPTION:
XS GIS Cut Line= 3
      3652749.63     10707310.18      3652549.61     10707410.19
      3652499.61      10707660.2
#Sta/Elev= 30
  4785.1  330.58  4799.1  329.37  4829.8  328.12  4838.2  327.33  4874.6  325.67
  4888.5  324.54  4896.9  324.47    4905  323.43  4919.3  323.07  4933.3   321.7
  4941.7  321.59    4950  320.87  4955.6  321.34  4972.4  319.56    4978   319.4
  4994.8  316.06  4997.3  315.99  5000.1  315.49  5003.3  315.99  5005.9  316.56
  5011.3  316.56  5018.9  317.71  5049.5  317.37  5057.3  318.29  5080.1   320.8
  5100.5  320.95  5156.5  323.51  5233.1  326.94  5257.8  327.62  5263.7  327.71
#Mann= 8 ,-1 , 0
  4785.1     .05       0    4905     .12       0    4950     .16       0
  4997.3     .07       0  5003.3     .16       0  5057.3     .12       0
  5156.5     .16       0  5257.8     .08       0
Bank Sta=4997.3,5003.3
XS Rating Curve= 0 ,0
Exp/Cntr=0.3,0.1

Type RM Length L Ch R = 1 ,1388    ,461,461,461
BEGIN DESCRIPTION:
UNT 01616 IN LACR 3.0
END DESCRIPTION:
XS GIS Cut Line= 3
      3652549.56     10707060.19      3652249.61     10707060.19
      3652099.58      10707110.2
#Sta/Elev= 30
  4746.5  323.75  4756.5   323.3  4816.5  322.84  4836.5  321.47  4846.5   320.1
  4856.5  319.42  4879.2  319.28  4886.5  319.49  4906.5  317.95  4916.5  317.73
  4926.5  314.19  4946.5  311.51  4956.5  311.32  4966.5  314.53  4976.5  314.24
  4986.5  311.01  4993.5  307.97  4996.2  307.47  4999.5  307.97  5016.5  308.11
  5036.5  310.96  5049.1  311.48    5057  313.43  5079.2  315.53  5088.6  315.82
  5099.2  317.28  5120.2  318.18  5151.9  320.77  5162.4  320.83  5204.6  324.67
#Mann= 5 ,-1 , 0
  4746.5     .05       0  4879.2     .12       0  4993.5     .07       0
  4999.5     .12       0  5079.2     .05       0
Bank Sta=4993.5,4999.5
XS Rating Curve= 0 ,0
Exp/Cntr=0.3,0.1

Type RM Length L Ch R = 1 ,927     ,238,238,238
BEGIN DESCRIPTION:
UNT 01616 IN LACR 2.0
END DESCRIPTION:
XS GIS Cut Line= 3
      3652549.62     10706460.18      3652249.61     10706610.19
      3652049.58     10706810.21
#Sta/Elev= 30
  4636.9  323.63  4667.7  321.28  4673.5  321.49    4690  320.12  4695.6  320.71
    4718  318.34  4771.1  316.03  4801.8  313.74  4815.8  313.62  4824.2   312.8
  4829.8  313.18  4846.5   311.4  4891.3  309.63  4896.9  310.31  4905.2  308.37
    4936  305.75  4941.6  306.75    4950  305.97  4972.6     306  4986.5   305.8
  4997.6  304.53  5000.4  304.03  5003.6  304.53  5014.7  304.81  5028.9   306.8
    5043  307.86  5099.6  310.65    5142  314.74  5176.6  317.05  5255.2  321.83
#Mann= 6 ,-1 , 0
  4636.9     .16       0  4673.5     .12       0  4972.6     .16       0
  4997.6     .07       0  5003.6     .16       0  5176.6     .05       0
Bank Sta=4997.6,5003.6
XS Rating Curve= 0 ,0
Exp/Cntr=0.3,0.1

Type RM Length L Ch R = 1 ,689     ,202,202,202
BEGIN DESCRIPTION:
Mapping XS 0ffb2bcc
END DESCRIPTION:
XS GIS Cut Line= 2
       3652302.4     10706243.64      3651903.82     10706681.22
#Sta/Elev= 30
  4705.3  315.61  4733.1  313.77  4775.6  312.92  4810.8  310.14  4839.2  309.19
  4846.6  309.67    4852   308.9  4895.9  307.62  4928.1  302.86  4930.8  302.36
  4934.1  302.86  4939.1  302.96  4959.4  302.96  4966.9     304  4995.2   304.7
    5002  302.86  5009.4  304.52  5058.8  304.19  5072.9  305.55  5079.7   305.2
  5122.3  307.64  5143.9  307.84  5164.8  310.05  5178.5  309.63  5186.4   310.4
  5193.2  309.75  5207.4  311.13  5235.8  311.68    5250  313.09  5297.2  314.95
#Mann= 6 ,-1 , 0
  4705.3     .05       0    4852     .16       0  4928.1     .07       0
  4934.1     .16       0  4939.1     .12       0  5178.5     .16       0
Bank Sta=4995.2,5009.4
XS Rating Curve= 0 ,0
Exp/Cntr=0.3,0.1

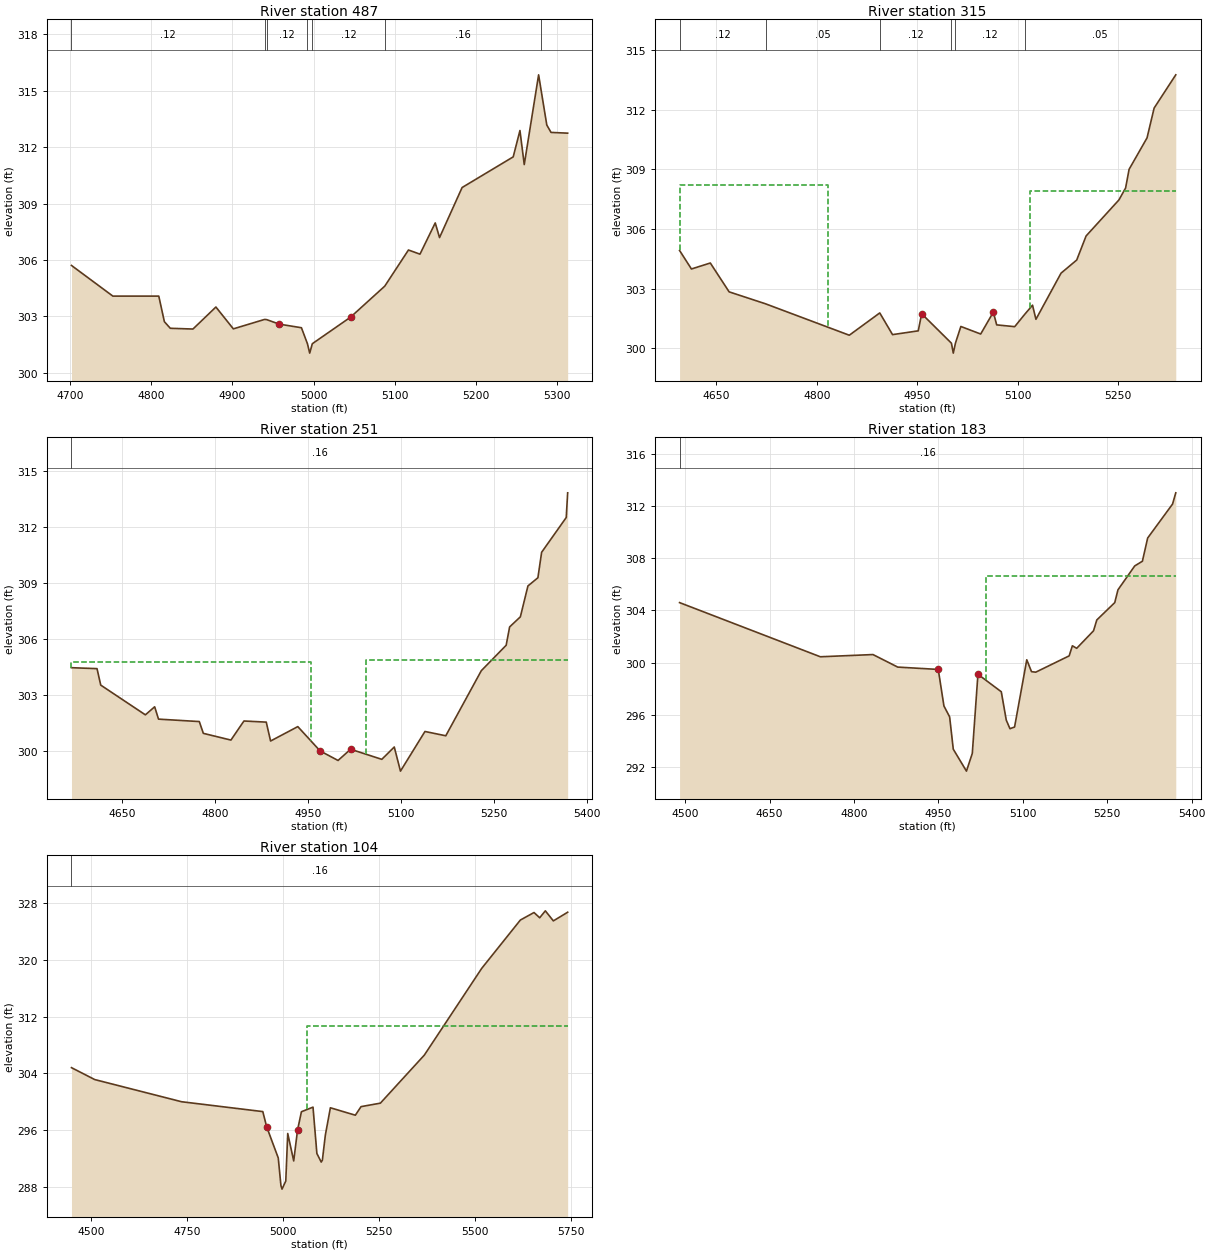
Type RM Length L Ch R = 1 ,487     ,172,172,172
BEGIN DESCRIPTION:
Mapping XS 8e611855
END DESCRIPTION:
XS GIS Cut Line= 3
      3652112.89     10706181.54      3651926.27     10706379.01
      3651828.63     10706704.48
#Sta/Elev= 30
  4701.6  305.71  4752.6  304.08  4809.2  304.08  4816.1  302.72  4823.4  302.37
  4851.3  302.33  4879.6   303.5  4901.1  302.34  4939.5  302.84  4942.2  302.83
  4957.7  302.59    4985   302.4  4992.4  301.55  4995.2  301.05  4998.4  301.55
  5045.5  302.96  5087.7  304.61  5116.9  306.53  5131.1  306.31  5149.9  307.97
  5155.2  307.19    5183  309.85    5246  311.48  5254.3  312.88  5259.6  311.07
  5277.3  315.84  5280.2  315.07  5287.4  313.17  5292.6  312.78  5313.1  312.74
#Mann= 7 ,-1 , 0
  4701.6     .12       0  4939.5     .05       0  4942.2     .12       0
  4992.4     .07       0  4998.4     .12       0  5087.7     .16       0
  5280.2     .05       0
Bank Sta=4957.7,5045.5
XS Rating Curve= 0 ,0
Exp/Cntr=0.3,0.1

Type RM Length L Ch R = 1 ,315     ,64,64,64
BEGIN DESCRIPTION:
Mapping XS 75a78e67
END DESCRIPTION:
XS GIS Cut Line= 4
      3652056.46     10706172.86      3651776.53     10706381.18
      3651739.64     10706585.17      3651796.08       10706761.
#Sta/Elev= 30
  4595.2  304.92  4612.9  303.99  4641.1  304.29  4669.2  302.84  4723.5  302.24
  4848.6  300.66  4894.1  301.78  4913.2  300.69  4951.6  300.88  4956.7  301.74
  5001.1  300.26  5003.9  299.76  5007.1  300.26  5015.2   301.1  5044.8  300.72
  5063.7  301.82  5068.7  301.18  5095.6  301.09  5110.3   301.7  5122.2  302.17
  5127.3  301.46  5164.8  303.78  5188.2  304.44  5202.2  305.65  5251.2  307.46
  5261.2  308.06  5266.4     309  5293.2  310.58  5303.8  312.08  5336.1  313.75
#Mann= 6 ,-1 , 0
  4595.2     .12       0  4723.5     .05       0  4894.1     .12       0
  5001.1     .07       0  5007.1     .12       0  5110.3     .05       0
#XS Ineff= 2 , 0
         4816.13   308.2 5118.28          307.93
Permanent Ineff=
       F       F
Bank Sta=4956.7,5063.7
XS Rating Curve= 0 ,0
Exp/Cntr=0.3,0.1

Type RM Length L Ch R = 1 ,251     ,68,68,68
BEGIN DESCRIPTION:
Mapping XS c7fe8372
END DESCRIPTION:
XS GIS Cut Line= 4
      3652046.08     10706170.35      3651707.55     10706398.21
      3651689.32     10706563.57      3651785.16      10706768.2
#Sta/Elev= 30
  4568.7  304.48  4609.9  304.43  4615.9  303.55  4687.9  301.96  4702.9  302.39
  4709.1  301.73  4774.9   301.6  4781.4  300.97  4825.9  300.61  4846.9  301.63
  4882.9  301.57  4889.9  300.56  4933.8  301.33  4969.8  300.03  4998.7  299.52
    5019  300.12  5069.3  299.58  5089.4  300.24  5099.4  298.95  5138.9  301.07
  5172.5  300.84  5229.8  304.32  5269.9  305.68  5275.5  306.66  5292.8   307.2
    5305  308.85  5321.1  309.29  5327.1  310.65  5366.8  312.51  5369.1  313.83
#Mann= 1 ,-1 , 0
  4568.7     .16       0
#XS Ineff= 2 , 0
         4955.56  304.76 5043.97          304.89
Permanent Ineff=
       F       F
Bank Sta=4969.8,5019
XS Rating Curve= 0 ,0
Exp/Cntr=0.3,0.1

Type RM Length L Ch R = 1 ,183     ,79,79,79
BEGIN DESCRIPTION:
Mapping XS c98184e2
END DESCRIPTION:
XS GIS Cut Line= 4
      3652040.91     10706165.12      3651650.26     10706373.47
      3651632.03       10706518.       3651775.4     10706773.74
#Sta/Elev= 30
  4490.2  304.59  4740.3  300.44  4833.8  300.61  4877.8  299.65  4949.8  299.47
  4959.9  296.67    4970  295.84  4976.5  293.36  4999.9  291.68  5010.3  293.04
  5020.3   299.1  5061.8  297.76  5070.7  295.58  5077.2  294.93  5085.4  295.06
  5107.1  300.21  5115.5   299.3    5123  299.26  5182.4  300.51  5188.1  301.28
  5195.8  301.09  5225.7  302.43  5231.5  303.26  5263.4  304.59  5269.1  305.57
  5298.9   307.4  5312.5  307.76  5321.9  309.54  5366.1  312.14  5371.8     313
#Mann= 1 ,-1 , 0
  4490.2     .16       0
#XS Ineff= 2 , 0
                         5034.66          306.65
Permanent Ineff=
       F       F
Bank Sta=4949.8,5020.3
XS Rating Curve= 0 ,0
Exp/Cntr=0.3,0.1

Type RM Length L Ch R = 1 ,104     ,0,0,0
BEGIN DESCRIPTION:
UNT 01616 IN LACR 1.0
END DESCRIPTION:
XS GIS Cut Line= 4
      3652031.45     10706150.99      3651583.39     10706352.96
      3651563.86     10706511.39       3651937.1     10707034.35
#Sta/Elev= 30
  4448.5  304.79  4509.1  303.11  4735.7  299.98  4947.3  298.59  4957.3  296.46
  4987.6  292.05  4994.6  288.15  4997.4  287.65  5007.2  288.79  5012.3   295.5
  5027.9  291.63  5037.9  295.99    5048  298.57  5078.2  299.22  5088.3  292.68
  5099.6  291.47  5102.6  291.73  5110.4  295.29  5123.5  299.13  5188.6  298.08
  5203.4  299.29  5253.8  299.78  5368.4  306.56    5518   318.8  5618.8  325.62
  5654.4  326.68  5669.2  325.94  5683.9  326.92  5704.8   325.5  5742.1  326.72
#Mann= 1 ,-1 , 0
  4448.5     .16       0
#XS Ineff= 2 , 0
                         5063.41          310.73
Permanent Ineff=
       F       F
Bank Sta=4957.3,5037.9
XS Rating Curve= 0 ,0
Exp/Cntr=0.3,0.1

Chan Stop Cuts=-1
Use User Specified Reach Order=0
Composite Channel Slope=5