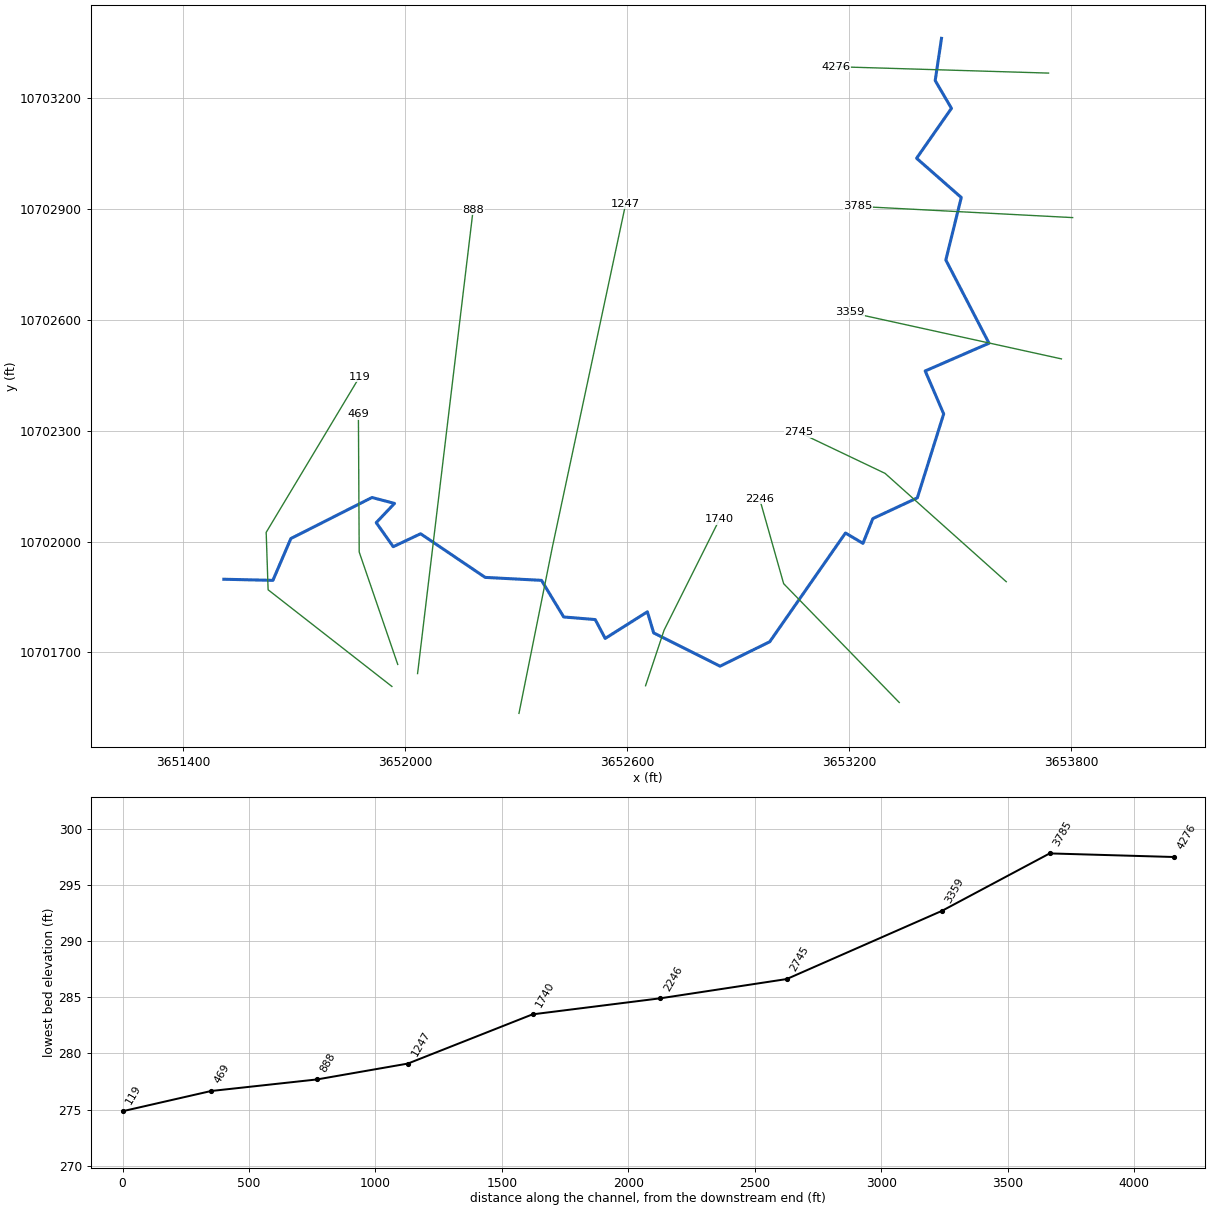
--- UNT 01618 IN LACR.prj (project) ---

Proj Title=UNT 01618 IN LACR Base Level Engineering
Current Plan=p01
Default Exp/Contr=0.3,0.1
English Units
Geom File=g01
Flow File=f01
Plan File=p01
BEGIN DESCRIPTION:
UNT 01618 IN LACR
END DESCRIPTION:

--- UNT 01618 IN LACR.p01 (plan) ---

Plan Title=Multiple Run
Short Identifier=Multiple
Geom File=g01
Flow File=f01
Subcritical Flow
K Sum by GR= 0
Std Step Tol= 0.01
Critical Tol= 0.01
Num of Std Step Trials= 20
Max Error Tol= 0.3
Flow Tol Ratio= 0.001
Split Flow NTrial= 30
Split Flow Tol= 0.02
Split Flow Ratio= 0.02
Log Output Level= 0
Friction Slope Method= 1
Unsteady Friction Slope Method= 2
Unsteady Bridges Friction Slope Method= 1
Parabolic Critical Depth
Global Vel Dist=  1 , 1 , 1
Global Log Level= 0
CheckData=True
Encroach Param= -1, 0, 0, 0
BEGIN DESCRIPTION:
Multiple Run
END DESCRIPTION:

--- UNT 01618 IN LACR.f01 (steady flow) ---

Flow Title=Multiple
Number of Profiles=7
Profile Names=10-year,25-year,50-year,1pct_min,100-year,1pct_plu,500-year
River Rch & RM= UNT 01618 IN LAC,Reach-1,4276
     448     604     732     653     883    1194    1289
Boundary for River Rch & Prof#=UNT 01618 IN LAC,Reach-1,1
Up Type=0
Dn Type=3
Dn Slope=0.005
Boundary for River Rch & Prof#=UNT 01618 IN LAC,Reach-1,2
Up Type=0
Dn Type=3
Dn Slope=0.005
Boundary for River Rch & Prof#=UNT 01618 IN LAC,Reach-1,3
Up Type=0
Dn Type=3
Dn Slope=0.005
Boundary for River Rch & Prof#=UNT 01618 IN LAC,Reach-1,4
Up Type=0
Dn Type=3
Dn Slope=0.005
Boundary for River Rch & Prof#=UNT 01618 IN LAC,Reach-1,5
Up Type=0
Dn Type=3
Dn Slope=0.005
Boundary for River Rch & Prof#=UNT 01618 IN LAC,Reach-1,6
Up Type=0
Dn Type=3
Dn Slope=0.005
Boundary for River Rch & Prof#=UNT 01618 IN LAC,Reach-1,7
Up Type=0
Dn Type=3
Dn Slope=0.005

--- UNT 01618 IN LACR.g01 (geometry) ---

Geom Title=Existing Conditions

River Reach=UNT 01618 IN LAC,Reach-1
Reach XY= 30
      3653449.61     10703360.19      3653432.50     10703246.00
      3653476.50     10703171.00      3653382.25     10703036.00
      3653503.00     10702930.00      3653461.25     10702761.00
      3653578.00     10702536.00      3653405.50     10702461.00
      3653455.50     10702345.00      3653384.25     10702118.00
      3653264.00     10702062.00      3653237.25     10701995.00
      3653190.00     10702023.00      3652985.25     10701729.00
      3652851.00     10701663.00      3652671.50     10701753.00
      3652654.50     10701810.00      3652540.50     10701738.00
      3652513.50     10701789.00      3652428.25     10701796.00
      3652368.25     10701895.00      3652216.00     10701903.00
      3652041.50     10702021.00      3651967.50     10701986.00
      3651921.50     10702051.00      3651971.00     10702103.00
      3651910.00     10702119.00      3651690.75     10702008.00
      3651642.25     10701895.00      3651509.50     10701898.00

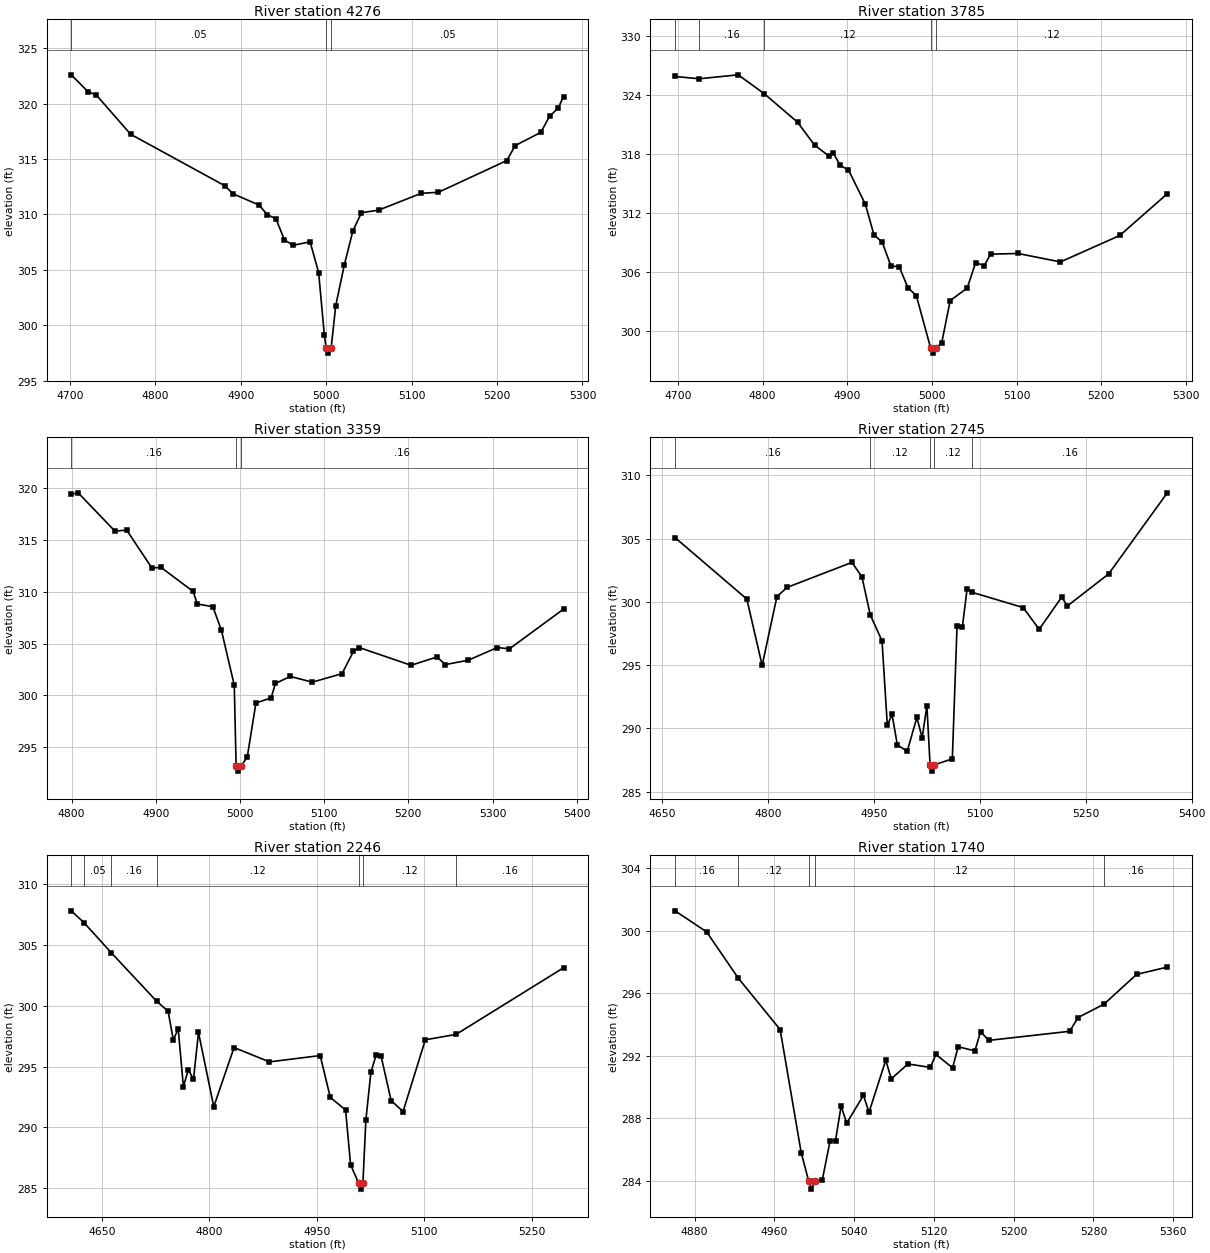
Type RM Length L Ch R = 1,4276,491,491,491
BEGIN DESCRIPTION:
UNT 01618 IN LACR 8.0
END DESCRIPTION:
XS GIS Cut Line= 2
      3653739.01     10703266.23      3653163.17     10703283.55
#Sta/Elev= 30
  4701.7  322.59  4721.1  321.08  4731.1  320.76  4771.1  317.23  4881.2  312.59
  4891.2  311.85  4921.2  310.85  4931.2  309.97  4941.2  309.60  4951.2  307.70
  4961.2  307.21  4981.2  307.52  4991.2  304.75  4997.9  299.09  4999.9  297.98
  5002.6  297.48  5005.9  297.98  5011.2  301.76  5021.2  305.42  5031.2  308.49
  5041.3  310.15  5061.3  310.38  5111.3  311.90  5131.3  311.99  5211.3  314.85
  5221.3  316.21  5251.3  317.40  5261.4  318.85  5271.4  319.57  5277.8  320.63
#Mann=3,-1,0
  4701.7    0.05       0  4999.9    0.03       0  5005.9    0.05       0
Bank Sta=4999.9,5005.9
Exp/Cntr=0.3,0.1

Type RM Length L Ch R = 1,3785,426,426,426
BEGIN DESCRIPTION:
UNT 01618 IN LACR 7.0
END DESCRIPTION:
XS GIS Cut Line= 2
      3653804.10     10702875.61      3653223.59     10702905.94
#Sta/Elev= 30
  4696.6  325.92  4725.2  325.69  4771.2  326.09  4801.8  324.18  4841.3  321.27
  4861.3  318.95  4878.3  317.84  4883.3  318.19  4891.4  316.89  4901.4  316.42
  4921.4  312.92  4931.4  309.85  4941.4  309.05  4951.4  306.69  4961.5  306.55
  4971.5  304.46  4981.5  303.65  4998.5  298.30  5001.3  297.80  5004.5  298.30
  5011.5  298.84  5021.5  303.14  5041.6  304.41  5051.6  307.01  5061.6  306.68
  5069.2  307.86  5101.6  307.93  5151.7  307.07  5221.8  309.76  5277.9  314.00
#Mann=5,-1,0
  4696.6    0.12       0  4725.2    0.16       0  4801.8    0.12       0
  4998.5    0.07       0  5004.5    0.12       0
Bank Sta=4998.5,5004.5
Exp/Cntr=0.3,0.1

Type RM Length L Ch R = 1,3359,614,614,614
BEGIN DESCRIPTION:
UNT 01618 IN LACR 6.0
END DESCRIPTION:
XS GIS Cut Line= 2
      3653773.76     10702493.66      3653202.68     10702619.12
#Sta/Elev= 30
  4799.6  319.42  4807.8  319.56  4851.6  315.85  4865.3  315.97  4895.4  312.30
  4906.2  312.36  4944.3  310.04  4949.4  308.82  4967.7  308.57  4977.9  306.30
  4993.2  300.99  4995.4  293.19  4998.1  292.69  5001.4  293.19  5008.6  294.04
  5018.9  299.26  5037.0  299.77  5042.1  301.16  5059.8  301.83  5085.9  301.28
  5121.2  302.10  5134.8  304.25  5141.7  304.62  5203.2  302.91  5233.9  303.71
  5244.1  302.98  5271.2  303.40  5305.5  304.62  5320.1  304.50  5384.3  308.33
#Mann=3,-1,0
  4799.6    0.16       0  4995.4    0.07       0  5001.4    0.16       0
Bank Sta=4995.4,5001.4
Exp/Cntr=0.3,0.1

Type RM Length L Ch R = 1,2745,499,499,499
BEGIN DESCRIPTION:
UNT 01618 IN LACR 5.0
END DESCRIPTION:
XS GIS Cut Line= 3
      3653624.62     10701891.31      3653296.94     10702184.27
      3653064.72     10702294.96
#Sta/Elev= 30
  4668.7  305.08  4770.3  300.22  4792.0  294.98  4812.9  300.41  4827.1  301.14
  4919.1  303.12  4933.3  301.97  4945.0  298.98  4961.7  296.91  4969.2  290.23
  4975.9  291.10  4983.4  288.68  4997.4  288.20  5011.0  290.86  5018.5  289.25
  5025.2  291.79  5029.7  287.12  5032.5  286.62  5035.7  287.12  5061.2  287.59
  5067.9  298.12  5075.4  298.00  5082.1  301.03  5088.9  300.76  5161.5  299.55
  5184.2  297.83  5216.1  300.38  5224.1  299.68  5282.5  302.21  5365.5  308.62
#Mann=5,-1,0
  4668.7    0.16       0  4945.0    0.12       0  5029.7    0.07       0
  5035.7    0.12       0  5088.9    0.16       0
Bank Sta=5029.7,5035.7
Exp/Cntr=0.3,0.1

Type RM Length L Ch R = 1,2246,506,506,506
BEGIN DESCRIPTION:
UNT 01618 IN LACR 4.0
END DESCRIPTION:
XS GIS Cut Line= 3
      3653335.38     10701564.84      3653022.87     10701886.03
      3652957.87     10702115.67
#Sta/Elev= 30
  4607.3  307.83  4625.1  306.85  4663.4  304.36  4726.3  300.39  4742.4  299.56
  4749.6  297.21  4756.5  298.10  4763.7  293.36  4770.7  294.75  4777.8  293.95
  4784.8  297.81  4806.1  291.70  4834.4  296.57  4883.8  295.39  4954.6  295.91
  4968.7  292.46  4990.0  291.43  4997.0  286.92  5008.2  285.41  5010.9  284.91
  5014.2  285.41  5018.3  290.58  5025.3  294.52  5032.5  295.93  5039.5  295.87
  5053.6  292.20  5070.2  291.30  5101.3  297.21  5144.1  297.65  5294.1  303.14
#Mann=7,-1,0
  4607.3     0.1       0  4625.1    0.05       0  4663.4    0.16       0
  4726.3    0.12       0  5008.2    0.07       0  5014.2    0.12       0
  5144.1    0.16       0
Bank Sta=5008.2,5014.2
Exp/Cntr=0.3,0.1

Type RM Length L Ch R = 1,1740,493,493,493
BEGIN DESCRIPTION:
UNT 01618 IN LACR 3.0
END DESCRIPTION:
XS GIS Cut Line= 3
      3652649.60     10701610.16      3652699.61     10701760.19
      3652849.63     10702060.23
#Sta/Elev= 30
  4860.4  301.29  4892.1  299.94  4923.7  296.99  4965.8  293.69  4986.9  285.81
  4994.5  283.98  4997.2  283.48  5000.5  283.98  5008.0  284.05  5015.9  286.58
  5021.3  286.58  5026.9  288.80  5032.5  287.70  5049.3  289.48  5054.9  288.40
  5071.7  291.73  5077.2  290.54  5094.0  291.49  5116.4  291.27  5122.0  292.10
  5138.7  291.24  5144.3  292.59  5161.1  292.33  5166.7  293.55  5175.1  293.00
  5256.1  293.58  5264.5  294.46  5290.6  295.32  5323.2  297.22  5354.0  297.69
#Mann=5,-1,0
  4860.4    0.16       0  4923.7    0.12       0  4994.5    0.07       0
  5000.5    0.12       0  5290.6    0.16       0
Bank Sta=4994.5,5000.5
Exp/Cntr=0.3,0.1

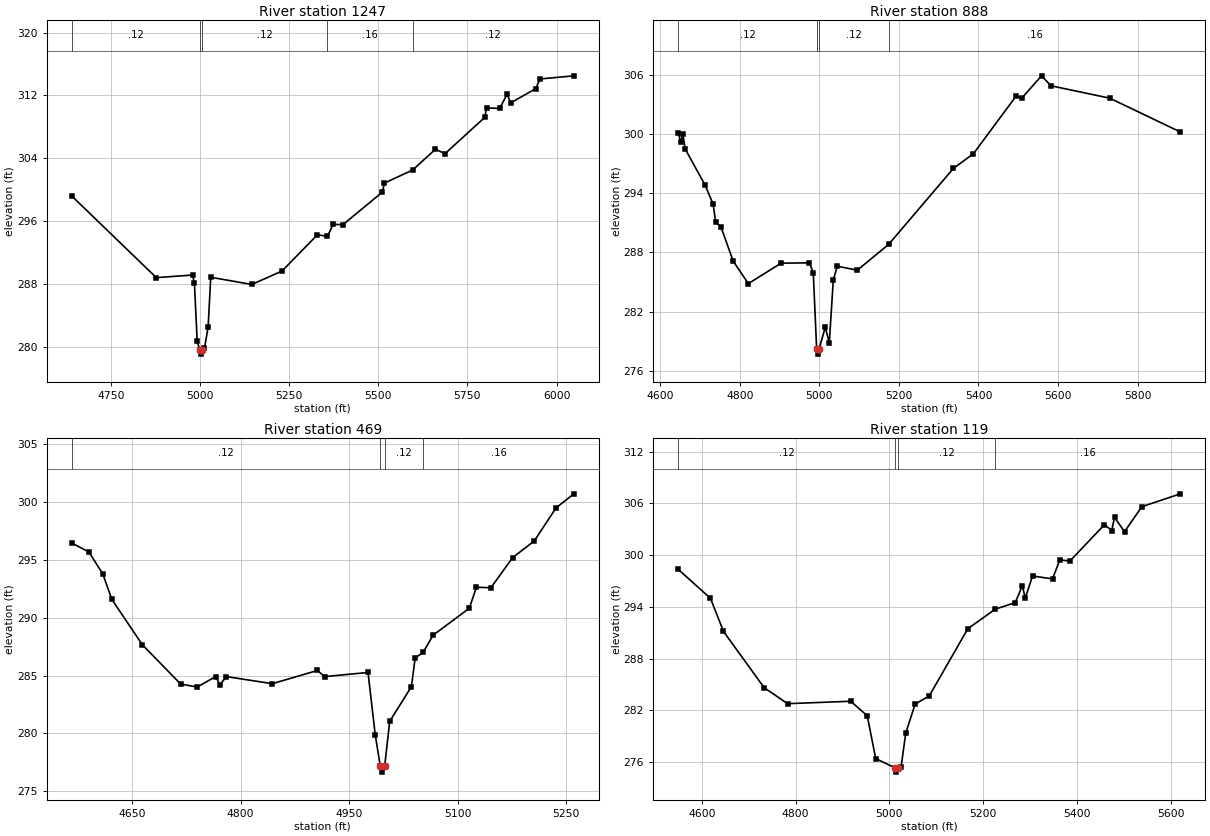
Type RM Length L Ch R = 1,1247,359,359,359
BEGIN DESCRIPTION:
UNT 01618 IN LACR 2.0
END DESCRIPTION:
XS GIS Cut Line= 3
      3652307.37     10701535.42      3652398.51     10701988.96
      3652595.98     10702913.40
#Sta/Elev= 30
  4640.6  299.21  4877.7  288.83  4979.4  289.16  4984.5  288.12  4992.3  280.73
  4999.5  279.60  5002.2  279.10  5005.5  279.60  5012.7  279.87  5022.9  282.49
  5030.3  288.88  5145.4  287.96  5230.2  289.67  5329.4  294.28  5357.5  294.08
  5373.6  295.61  5401.0  295.57  5511.9  299.72  5517.0  300.85  5596.5  302.52
  5660.4  305.16  5687.3  304.60  5798.6  309.21  5803.7  310.42  5840.7  310.35
  5861.2  312.17  5871.4  311.06  5942.0  312.88  5953.2  314.10  6048.5  314.50
#Mann=5,-1,0
  4640.6    0.12       0  4999.5    0.07       0  5005.5    0.12       0
  5357.5    0.16       0  5596.5    0.12       0
Bank Sta=4999.5,5005.5
Exp/Cntr=0.3,0.1

Type RM Length L Ch R = 1,888,419,419,419
BEGIN DESCRIPTION:
Mapping XS 823c2a6a
END DESCRIPTION:
XS GIS Cut Line= 2
      3652033.29     10701642.99      3652183.48     10702896.72
#Sta/Elev= 30
  4644.9  300.08  4651.6  299.19  4656.6  300.00  4662.2  298.50  4712.6  294.81
  4732.7  292.89  4738.9  291.09  4752.9  290.53  4783.1  287.11  4821.2  284.84
  4903.6  286.91  4974.4  286.94  4984.5  285.96  4993.0  278.19  4995.7  277.69
  4999.0  278.19  5014.7  280.43  5024.8  278.83  5034.9  285.22  5044.9  286.60
  5095.3  286.20  5174.0  288.81  5337.0  296.52  5387.4  298.01  5494.9  303.86
  5508.2  303.61  5558.6  305.90  5582.3  304.89  5729.8  303.64  5907.6  300.21
#Mann=4,-1,0
  4644.9    0.12       0  4993.0    0.07       0  4999.0    0.12       0
  5174.0    0.16       0
Bank Sta=4993,4999
Exp/Cntr=0.3,0.1

Type RM Length L Ch R = 1,469,350,350,350
BEGIN DESCRIPTION:
Mapping XS 9f756605
END DESCRIPTION:
XS GIS Cut Line= 3
      3651979.68     10701667.74      3651875.50     10701971.60
      3651873.33     10702344.87
#Sta/Elev= 30
  4566.4  296.45  4590.1  295.68  4609.4  293.77  4621.8  291.58  4664.1  287.66
  4717.0  284.27  4739.8  284.01  4765.8  284.92  4771.1  284.19  4780.4  284.91
  4843.8  284.30  4906.2  285.44  4916.2  284.91  4976.2  285.27  4986.2  279.87
  4993.2  277.16  4996.0  276.66  4999.2  277.16  5006.2  281.05  5036.2  284.04
  5041.4  286.52  5052.4  287.00  5066.2  288.49  5116.2  290.81  5126.2  292.63
  5146.2  292.59  5176.2  295.19  5206.2  296.63  5236.2  299.48  5260.9  300.70
#Mann=4,-1,0
  4566.4    0.12       0  4993.2    0.07       0  4999.2    0.12       0
  5052.4    0.16       0
Bank Sta=4993.2,4999.2
Exp/Cntr=0.3,0.1

Type RM Length L Ch R = 1,119,0,0,0
BEGIN DESCRIPTION:
UNT 01618 IN LACR 1.0
END DESCRIPTION:
XS GIS Cut Line= 4
      3651963.83     10701608.25      3651629.26     10701869.54
      3651624.05     10702024.75      3651876.82     10702445.56
#Sta/Elev= 30
  4549.7  298.35  4618.5  294.99  4646.2  291.16  4732.7  284.66  4782.8  282.79
  4917.5  283.07  4952.8  281.39  4970.8  276.43  5011.9  275.36  5014.6  274.86
  5017.9  275.36  5024.9  275.44  5034.9  279.38  5054.9  282.75  5084.9  283.68
  5167.2  291.47  5225.9  293.74  5268.3  294.50  5283.8  296.47  5289.6  294.99
  5305.2  297.58  5347.9  297.25  5363.5  299.46  5384.9  299.31  5458.7  303.53
  5474.1  302.85  5480.1  304.37  5501.4  302.72  5538.4  305.61  5620.4  307.10
#Mann=4,-1,0
  4549.7    0.12       0  5011.9    0.07       0  5017.9    0.12       0
  5225.9    0.16       0
Bank Sta=5011.9,5017.9
Exp/Cntr=0.3,0.1

Chan Stop Cuts=-1