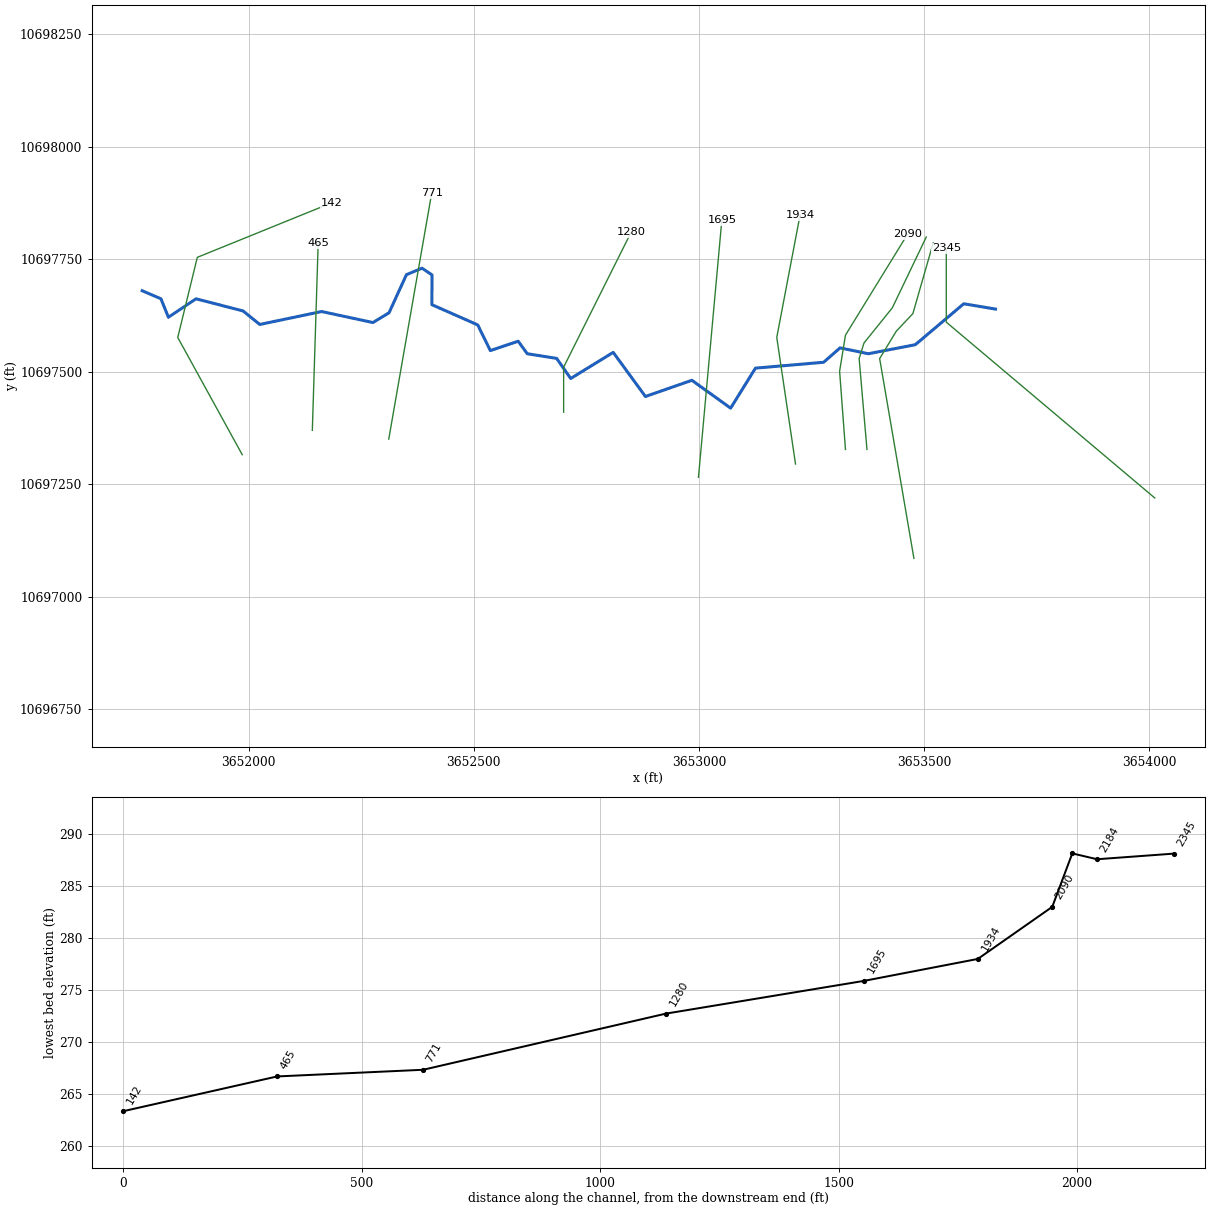
--- UNT 01624 IN LACR.prj (project) ---

Proj Title=UNT 01624 IN LACR Base Level Engineering
Current Plan=p01
Default Exp/Contr=0.3,0.1
English Units
Geom File=g01
Flow File=f01
Plan File=p01
Y Axis Title=Elevation
X Axis Title(PF)=Main Channel Distance
X Axis Title(XS)=Station
BEGIN DESCRIPTION:
UNT 01624 IN LACR
END DESCRIPTION:
DSS Export Rating Curves= 0
DSS Export Rating Curve Sorted= 0
DSS Export Volume Flow Curves= 0
DXF OffsetX= 0
DXF OffsetY= 0
DXF ScaleX= 1
DXF ScaleY= 10

--- UNT 01624 IN LACR.p01 (plan) ---

Plan Title=Multiple Run
Short Identifier=Multiple
Geom File=g01
Flow File=f01
Subcritical Flow
K Sum by GR= 0
Std Step Tol= 0.01
Critical Tol= 0.01
Num of Std Step Trials= 20
Max Error Tol= 0.3
Flow Tol Ratio= 0.001
Split Flow NTrial= 30
Split Flow Tol= 0.02
Split Flow Ratio= 0.02
Log Output Level= 0
Friction Slope Method= 1
Unsteady Friction Slope Method= 2
Unsteady Bridges Friction Slope Method= 1
Parabolic Critical Depth
Global Vel Dist=  1 , 1 , 1
Global Log Level= 0
CheckData=True
Encroach Param= -1, 0, 0, 0
BEGIN DESCRIPTION:
Multiple Run
END DESCRIPTION:

--- UNT 01624 IN LACR.f01 (steady flow) ---

Flow Title=Multiple
Program Version=4.10
Number of Profiles= 7
Profile Names=10-year,25-year,50-year,1pct_min,100-year,1pct_plu,500-year
River Rch & RM=UNT 01624 IN LAC,Reach-1         ,2345
     255     331     391     341     461     623     641
Boundary for River Rch & Prof#=UNT 01624 IN LAC,Reach-1         , 1
Up Type= 0
Dn Type= 3
Dn Slope=0.01
Boundary for River Rch & Prof#=UNT 01624 IN LAC,Reach-1         , 2
Up Type= 0
Dn Type= 3
Dn Slope=0.01
Boundary for River Rch & Prof#=UNT 01624 IN LAC,Reach-1         , 3
Up Type= 0
Dn Type= 3
Dn Slope=0.01
Boundary for River Rch & Prof#=UNT 01624 IN LAC,Reach-1         , 4
Up Type= 0
Dn Type= 3
Dn Slope=0.01
Boundary for River Rch & Prof#=UNT 01624 IN LAC,Reach-1         , 5
Up Type= 0
Dn Type= 3
Dn Slope=0.01
Boundary for River Rch & Prof#=UNT 01624 IN LAC,Reach-1         , 6
Up Type= 0
Dn Type= 3
Dn Slope=0.01
Boundary for River Rch & Prof#=UNT 01624 IN LAC,Reach-1         , 7
Up Type= 0
Dn Type= 3
Dn Slope=0.01
DSS Import GetInterval= 0
DSS Import GetPeak= 0
DSS Import FillOption= 0

--- UNT 01624 IN LACR.g01 (geometry) ---

Geom Title=Existing Conditions
Program Version=4.10

River Reach=UNT 01624 IN LAC,Reach-1
Reach XY= 30
      3653658.94      10697639.2       3653588.5       10697651.
      3653480.75       10697560.       3653376.5       10697540.
      3653313.75       10697553.        3653277.       10697521.
      3653125.75       10697508.      3653070.59     10697419.15
       3652984.5       10697481.      3652881.25       10697445.
      3652809.75       10697543.      3652715.25       10697485.
      3652684.09     10697529.61      3652618.75       10697540.
      3652598.59     10697567.81      3652536.75       10697547.
      3652508.75       10697604.      3652406.75       10697649.
      3652407.25       10697715.        3652385.       10697730.
      3652350.32     10697715.59      3652311.69     10697630.96
      3652275.89     10697609.26      3652161.95     10697633.78
       3652024.5       10697605.       3651987.5       10697635.
        3651883.       10697662.       3651821.5     10697621.02
        3651805.       10697662.      3651763.25       10697680.

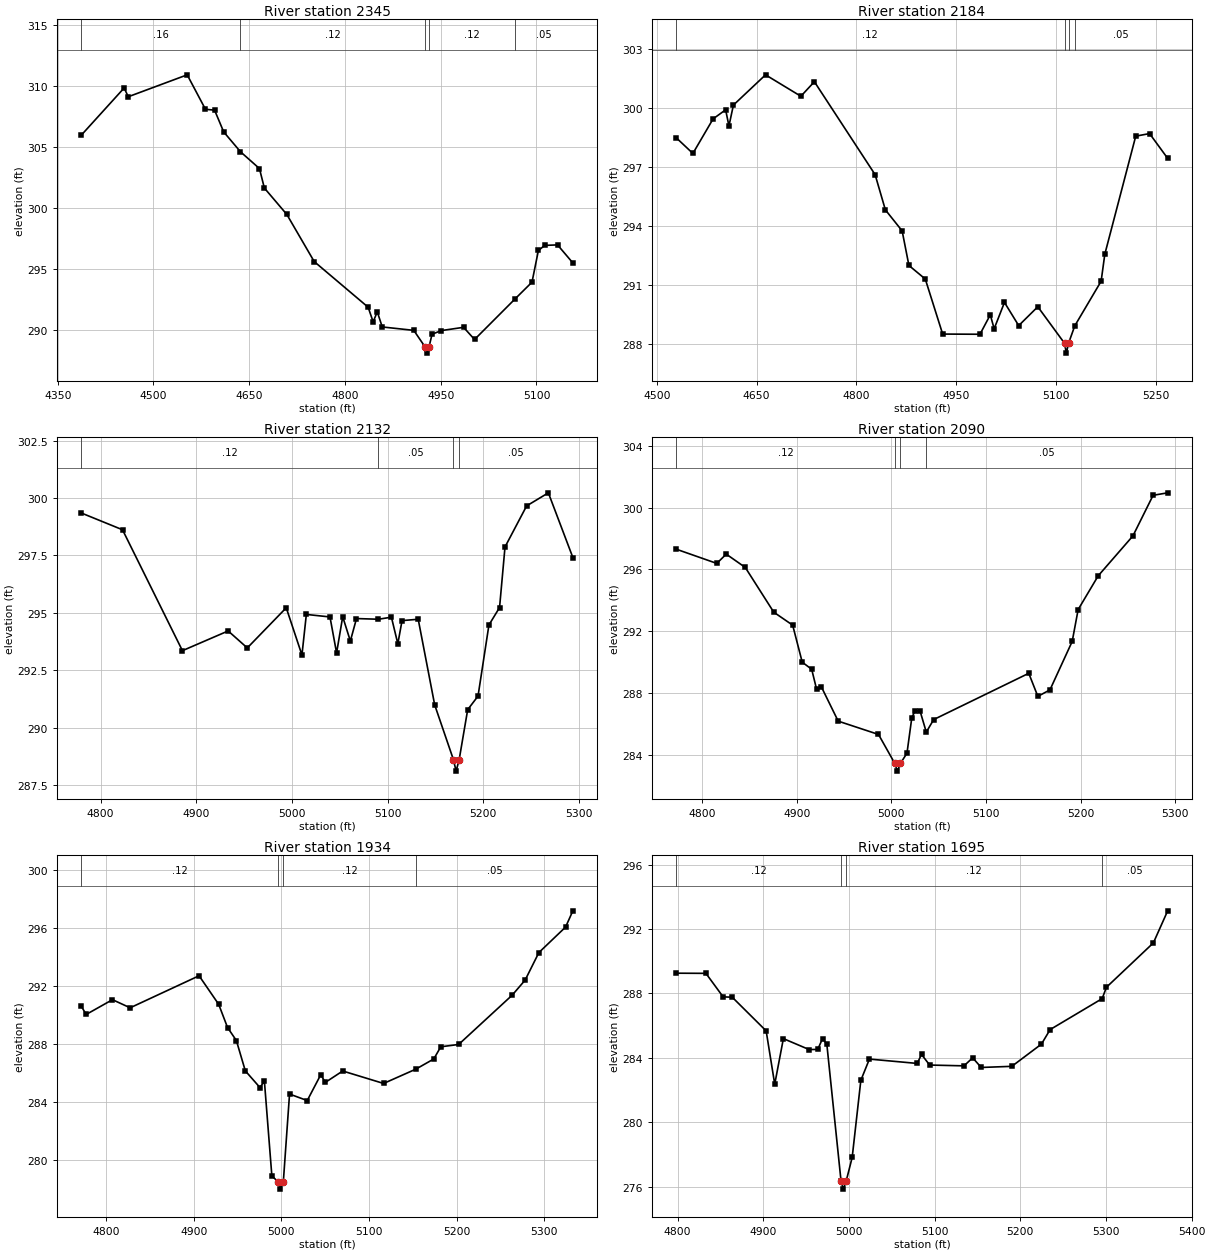
Type RM Length L Ch R = 1 ,2345    ,161,161,161
BEGIN DESCRIPTION:
UNT 01624 IN LACR 4.0
END DESCRIPTION:
XS GIS Cut Line= 3
      3654012.87     10697219.57      3653549.61     10697610.19
      3653549.61     10697774.22
#Sta/Elev= 30
    4387  305.99    4454  309.86  4460.5  309.14  4552.8  310.94  4581.4  308.11
  4595.7  308.04    4610  306.25  4636.3  304.62    4666  303.24  4673.7  301.64
  4708.9  299.47  4751.8   295.6  4836.3  291.85  4844.1  290.65  4850.6  291.47
  4858.4  290.23  4907.8  289.95  4925.6  288.58  4928.4  288.08  4931.6  288.58
  4936.4  289.63  4950.7  289.93  4985.8   290.2    5003   289.2  5066.2  292.52
    5093  293.91    5103  296.51    5113  296.93    5133  296.97    5157  295.49
#Mann= 5 ,-1 , 0
    4387     .16       0  4636.3     .12       0  4925.6     .07       0
  4931.6     .12       0  5066.2     .05       0
Bank Sta=4925.6,4931.6
XS Rating Curve= 0 ,0
Exp/Cntr=0.3,0.1

Type RM Length L Ch R = 1 ,2184    ,52,52,52
BEGIN DESCRIPTION:
Mapping XS e05679c5
END DESCRIPTION:
XS GIS Cut Line= 5
      3653477.75     10697085.45      3653401.65     10697529.26
      3653438.55     10697590.03      3653475.44     10697629.09
      3653520.66      10697786.3
#Sta/Elev= 30
  4529.1   298.5  4554.2   297.7  4584.6  299.46  4603.4  299.92  4608.4   299.1
  4615.1  300.16  4663.4   301.7  4716.5  300.61  4736.8  301.35  4828.1  296.62
  4843.5  294.83  4868.7  293.76  4878.9     292  4903.5  291.31  4929.6  288.51
  4985.7   288.5  5001.2  289.49    5007  288.78  5022.5  290.12  5043.9  288.94
  5072.6   289.9  5112.8  288.04  5115.5  287.54  5118.8  288.04  5128.2  288.93
  5167.8   291.2  5173.3  292.57  5219.8  298.58  5240.6  298.71  5267.8  297.45
#Mann= 4 ,-1 , 0
  4529.1     .12       0  5112.8     .07       0  5118.8     .12       0
  5128.2     .05       0
Bank Sta=5112.8,5118.8
XS Rating Curve= 0 ,0
Exp/Cntr=0.3,0.1

Type RM Length L Ch R = 1 ,2132    ,42,42,42
BEGIN DESCRIPTION:
Mapping XS 1dc41538
END DESCRIPTION:
XS GIS Cut Line= 5
      3653373.45      10697327.4      3653356.08     10697529.26
      3653366.93     10697563.99      3653429.87     10697642.11
      3653505.22     10697799.27
#Sta/Elev= 30
    4780  299.35    4823  298.62  4885.6  293.35  4933.4  294.21  4953.4  293.47
  4994.1  295.22  5010.5  293.16  5015.1  294.93  5039.8  294.82  5046.7  293.25
  5053.1  294.83  5061.1  293.77  5067.5  294.75  5090.5  294.72    5104  294.81
  5110.7  293.65  5115.1  294.66    5132  294.72  5149.2  290.99  5168.8   288.6
  5171.6   288.1  5174.8   288.6  5183.7  290.78  5194.5  291.37  5205.9  294.47
    5217  295.23  5222.7  297.87  5245.3  299.66    5268  300.23  5293.6  297.41
#Mann= 4 ,-1 , 0
    4780     .12       0  5090.5     .05       0  5168.8     .07       0
  5174.8     .05       0
Bank Sta=5168.8,5174.8
XS Rating Curve= 0 ,0
Exp/Cntr=0.3,0.1

Type RM Length L Ch R = 1 ,2090    ,156,156,156
BEGIN DESCRIPTION:
Mapping XS 957e6086
END DESCRIPTION:
XS GIS Cut Line= 4
       3653325.7      10697327.4      3653312.68     10697501.05
       3653325.7     10697581.35      3653464.02     10697806.12
#Sta/Elev= 30
  4772.6  297.31  4815.5  296.39  4825.5  296.99  4845.6  296.13  4875.7  293.24
  4895.7   292.4  4905.8  290.01  4915.8  289.55  4920.9  288.28  4925.9  288.43
  4943.8   286.2  4986.4  285.34  5003.6  283.47  5006.4  282.97  5009.6  283.47
  5016.5  284.13  5021.6  286.42    5025  286.86  5030.3  286.86  5036.9  285.49
  5044.7   286.3  5145.2  289.29  5154.8   287.8  5167.6  288.22  5191.1  291.35
  5197.4  293.41  5218.6  295.59  5255.3  298.17  5276.6  300.79    5292  300.95
#Mann= 4 ,-1 , 0
  4772.6     .12       0  5003.6     .07       0  5009.6     .12       0
  5036.9     .05       0
Bank Sta=5003.6,5009.6
XS Rating Curve= 0 ,0
Exp/Cntr=0.3,0.1

Type RM Length L Ch R = 1 ,1934    ,239,239,239
BEGIN DESCRIPTION:
UNT 01624 IN LACR 3.0
END DESCRIPTION:
XS GIS Cut Line= 3
      3653214.73     10697295.06      3653173.07     10697576.31
      3653224.87      10697848.3
#Sta/Elev= 30
  4771.6  290.58  4777.1  290.02  4807.1  291.04  4827.3  290.48    4906  292.69
  4928.4  290.72  4938.5  289.12  4948.6  288.22  4958.8  286.13  4975.5  284.98
  4980.6  285.42  4989.1  278.89  4996.2  278.47  4998.9  277.97  5002.2  278.47
  5009.3  284.53  5029.5  284.08    5045  285.87  5050.1  285.33    5070  286.12
  5116.7  285.26  5153.6  286.25    5174  286.95    5182  287.79  5202.4  287.95
  5263.5  291.35  5278.3  292.39    5294  294.29  5324.5  296.05  5332.8  297.17
#Mann= 4 ,-1 , 0
  4771.6     .12       0  4996.2     .07       0  5002.2     .12       0
  5153.6     .05       0
Bank Sta=4996.2,5002.2
XS Rating Curve= 0 ,0
Exp/Cntr=0.3,0.1

Type RM Length L Ch R = 1 ,1695    ,415,415,415
BEGIN DESCRIPTION:
Mapping XS 9c530383
END DESCRIPTION:
XS GIS Cut Line= 2
       3652999.1     10697265.62      3653051.03     10697836.87
#Sta/Elev= 30
  4798.4  289.26  4833.1  289.25  4853.2  287.79  4863.8  287.77  4903.4  285.68
  4913.4  282.37  4923.5   285.2  4953.6  284.52  4963.6  284.53  4969.2   285.2
  4974.2  284.86  4990.8  276.36  4993.5  275.86  4996.8  276.36  5003.8  277.83
  5013.9  282.61  5023.9  283.93  5079.7  283.66  5084.7  284.22  5094.2  283.56
  5134.3  283.51  5144.4  284.01  5154.4  283.41  5190.1  283.48  5224.7  284.86
  5234.8  285.76  5295.5  287.68  5300.6  288.39  5355.3  291.14    5372  293.13
#Mann= 4 ,-1 , 0
  4798.4     .12       0  4990.8     .07       0  4996.8     .12       0
  5295.5     .05       0
Bank Sta=4990.8,4996.8
XS Rating Curve= 0 ,0
Exp/Cntr=0.3,0.1

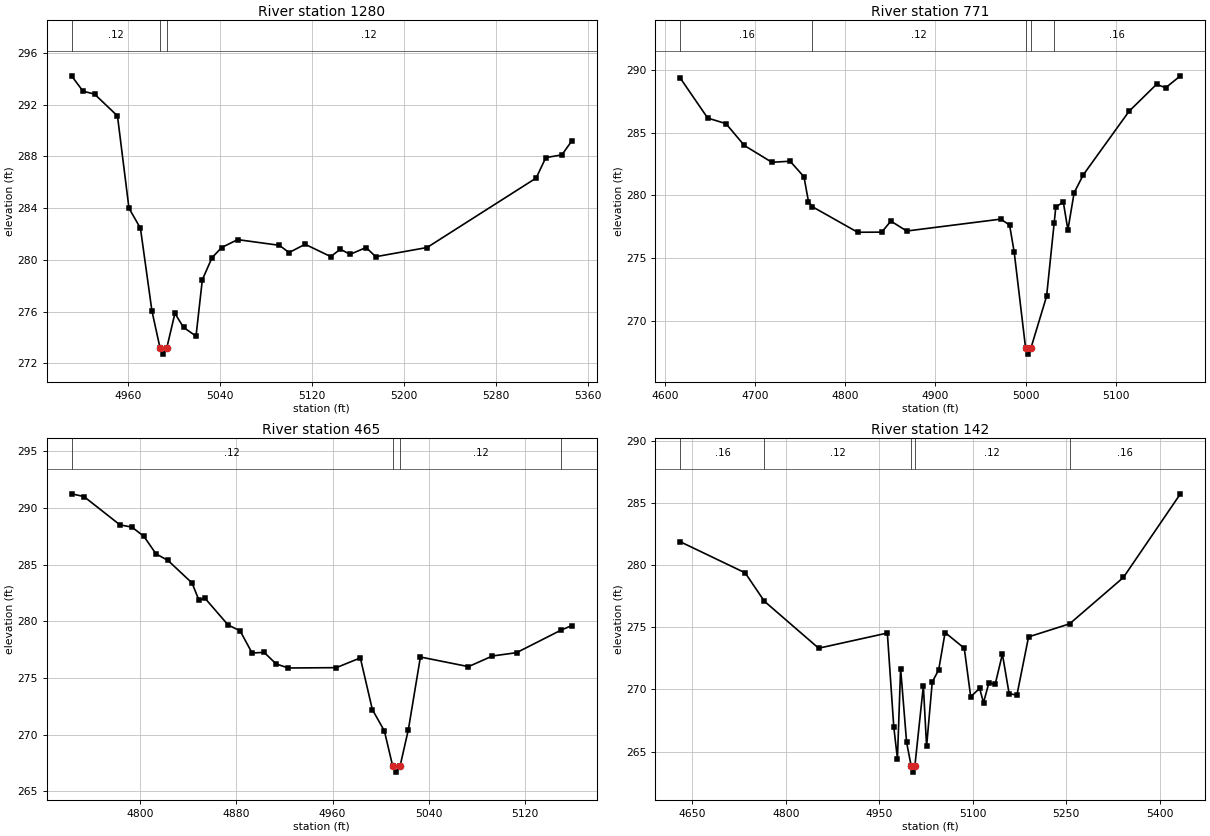
Type RM Length L Ch R = 1 ,1280    ,509,509,509
BEGIN DESCRIPTION:
UNT 01624 IN LACR 2.0
END DESCRIPTION:
XS GIS Cut Line= 3
      3652699.61     10697410.22      3652699.61     10697510.19
      3652849.62     10697810.21
#Sta/Elev= 30
  4910.6  294.23  4920.6  293.04  4930.6  292.82  4950.6  291.13  4960.6     284
  4970.6  282.45  4980.6  276.06  4987.6  273.22  4990.3  272.72  4993.6  273.22
  5000.6  275.87  5008.1  274.79    5019  274.11  5024.5  278.47  5032.9  280.17
  5041.3  280.96  5055.3  281.57  5091.6  281.13    5100  280.57    5114  281.21
  5136.3  280.26  5144.7  280.83  5153.1  280.43  5167.1  280.96  5175.5  280.25
  5220.2  280.96  5315.2  286.33  5323.6  287.91  5337.6  288.12    5346  289.17
#Mann= 3 ,-1 , 0
  4910.6     .12       0  4987.6     .08       0  4993.6     .12       0
Bank Sta=4987.6,4993.6
XS Rating Curve= 0 ,0
Exp/Cntr=0.3,0.1

Type RM Length L Ch R = 1 ,771     ,306,306,306
BEGIN DESCRIPTION:
Mapping XS a892fa82
END DESCRIPTION:
XS GIS Cut Line= 2
      3652311.06     10697350.42      3652406.36     10697896.27
#Sta/Elev= 30
  4617.4  289.35  4647.6  286.18  4667.9  285.73  4688.2  283.99  4718.7  282.65
    4739  282.73  4754.3  281.49  4759.3  279.51  4763.6   279.1  4813.8  277.06
  4840.5  277.07  4850.6  277.95  4868.2  277.16  4972.5  278.11  4982.2  277.63
  4987.3  275.47  4999.9  267.83  5002.7  267.33  5005.9  267.83  5023.2  271.95
  5031.6  277.81  5033.4  279.07  5041.7  279.48  5046.8  277.25  5053.7  280.21
  5063.8  281.64  5114.6  286.72    5145  288.87  5155.2   288.6  5171.5  289.55
#Mann= 5 ,-1 , 0
  4617.4     .16       0  4763.6     .12       0  4999.9     .07       0
  5005.9     .12       0  5031.6     .16       0
Bank Sta=4999.9,5005.9
XS Rating Curve= 0 ,0
Exp/Cntr=0.3,0.1

Type RM Length L Ch R = 1 ,465     ,323,323,323
BEGIN DESCRIPTION:
Mapping XS a7d7f5e9
END DESCRIPTION:
XS GIS Cut Line= 2
      3652141.27     10697369.92      3652154.27     10697785.92
#Sta/Elev= 30
  4742.7  291.25    4753  291.01    4783  288.51    4793  288.31    4803  287.49
    4813  285.95    4823  285.37    4843  283.38  4848.7  281.88  4853.8  282.03
    4873  279.68    4883  279.16    4893   277.2    4903  277.26    4913  276.24
  4923.1  275.88  4963.1  275.91  4983.1  276.77  4993.1  272.21  5003.1  270.33
  5010.1  267.19  5012.8  266.69  5016.1  267.19  5023.1  270.45  5033.1  276.85
  5073.1     276  5093.1  276.94  5113.1  277.23  5150.5  279.24  5158.9  279.61
#Mann= 4 ,-1 , 0
  4742.7     .12       0  5010.1     .07       0  5016.1     .12       0
  5150.5     .16       0
Bank Sta=5010.1,5016.1
XS Rating Curve= 0 ,0
Exp/Cntr=0.3,0.1

Type RM Length L Ch R = 1 ,142     ,0,0,0
BEGIN DESCRIPTION:
UNT 01624 IN LACR 1.0
END DESCRIPTION:
XS GIS Cut Line= 4
      3651985.52     10697315.75      3651842.31     10697576.13
      3651885.71     10697754.08      3652184.42      10697875.3
#Sta/Elev= 30
  4630.7  281.86  4734.6  279.37  4765.4  277.09  4852.6  273.31  4962.9  274.53
  4973.2  266.99  4979.1  264.42  4984.2  271.67  4993.8  265.75  5001.1  263.85
  5003.8  263.35  5007.1  263.85  5020.7  270.28  5025.9  265.42    5035   270.6
  5045.3  271.57  5055.6  274.57  5086.4  273.31  5096.7  269.41    5111  270.08
  5117.3  268.94    5126  270.54    5136   270.4  5147.6  272.84  5158.4  269.66
  5170.9  269.54  5189.6  274.22  5255.5  275.27  5341.9     279  5433.4  285.72
#Mann= 5 ,-1 , 0
  4630.7     .16       0  4765.4     .12       0  5001.1     .07       0
  5007.1     .12       0  5255.5     .16       0
Bank Sta=5001.1,5007.1
XS Rating Curve= 0 ,0
Exp/Cntr=0.3,0.1

Chan Stop Cuts=-1
Use User Specified Reach Order=0
Composite Channel Slope=5