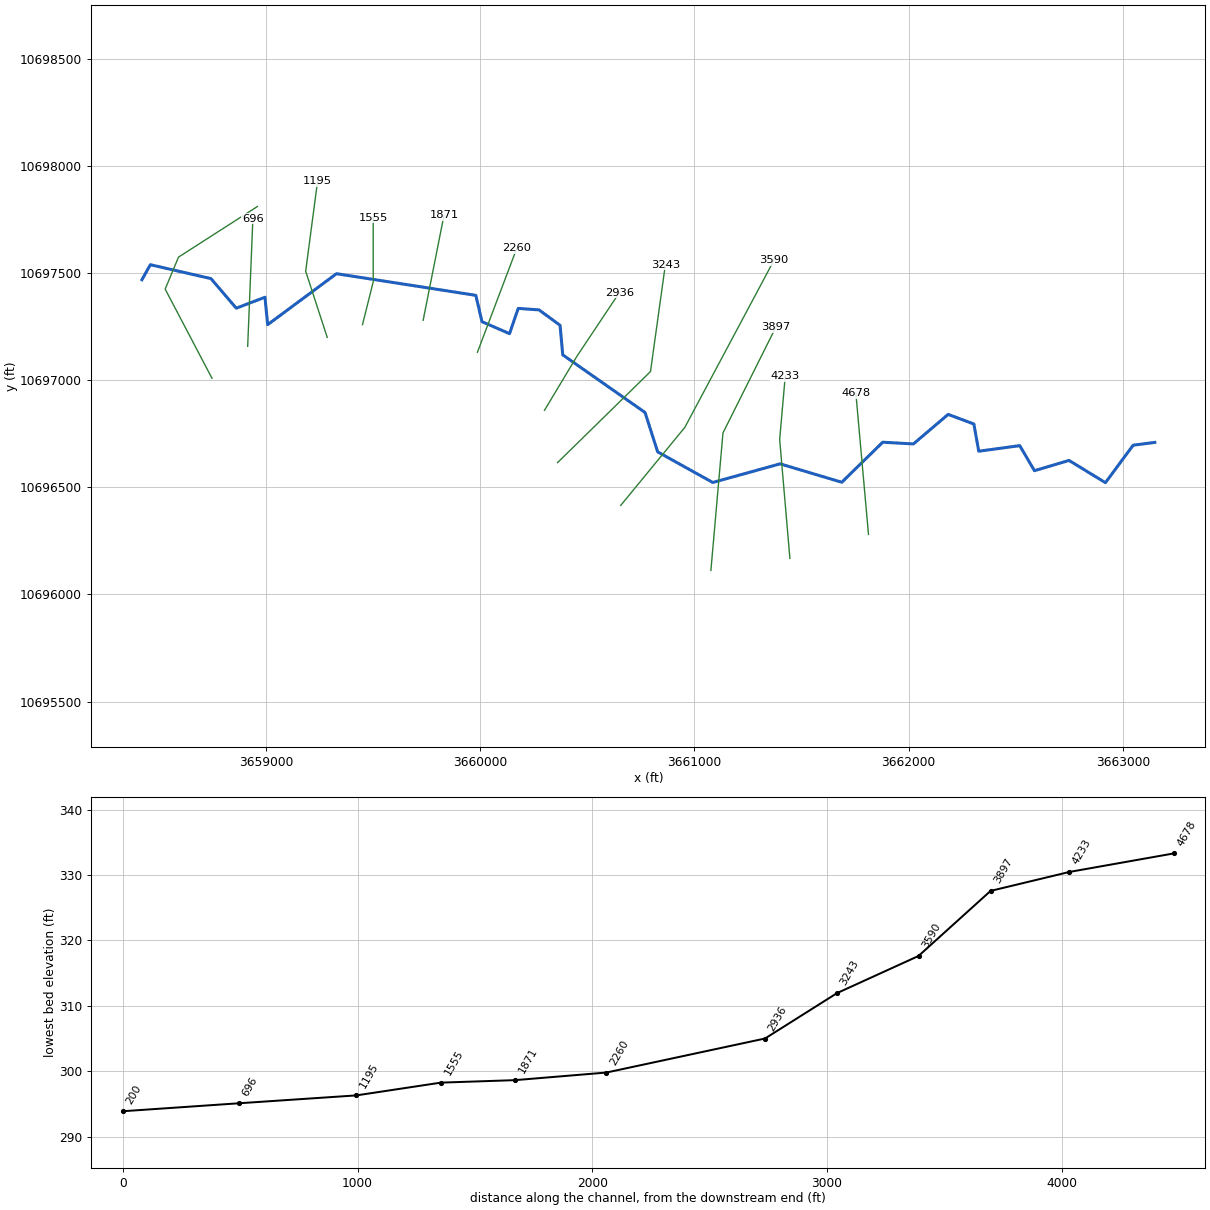
--- UNT 01648 IN LACR.prj (project) ---

Proj Title=UNT 01648 IN LACR Base Level Engineering
Current Plan=p01
Default Exp/Contr=0.3,0.1
English Units
Geom File=g01
Flow File=f01
Plan File=p01
Y Axis Title=Elevation
X Axis Title(PF)=Main Channel Distance
X Axis Title(XS)=Station
BEGIN DESCRIPTION:
UNT 01648 IN LACR
END DESCRIPTION:
DSS Export Rating Curves= 0
DSS Export Rating Curve Sorted= 0
DSS Export Volume Flow Curves= 0
DXF OffsetX= 0
DXF OffsetY= 0
DXF ScaleX= 1
DXF ScaleY= 10

--- UNT 01648 IN LACR.p01 (plan) ---

Plan Title=Multiple Run
Short Identifier=Multiple
Geom File=g01
Flow File=f01
Subcritical Flow
K Sum by GR= 0
Std Step Tol= 0.01
Critical Tol= 0.01
Num of Std Step Trials= 20
Max Error Tol= 0.3
Flow Tol Ratio= 0.001
Split Flow NTrial= 30
Split Flow Tol= 0.02
Split Flow Ratio= 0.02
Log Output Level= 0
Friction Slope Method= 1
Unsteady Friction Slope Method= 2
Unsteady Bridges Friction Slope Method= 1
Parabolic Critical Depth
Global Vel Dist=  1 , 1 , 1
Global Log Level= 0
CheckData=True
Encroach Param= -1, 0, 0, 0
BEGIN DESCRIPTION:
Multiple Run
END DESCRIPTION:

--- UNT 01648 IN LACR.f01 (steady flow) ---

Flow Title=Multiple
Number of Profiles=7
Profile Names=10-year,25-year,50-year,1pct_min,100-year,1pct_plu,500-year
River Rch & RM= UNT 01648 IN LAC,Reach-1,4678
     445     597     722     642     868    1175    1261
Boundary for River Rch & Prof#=UNT 01648 IN LAC,Reach-1,1
Up Type=0
Dn Type=3
Dn Slope=0.005
Boundary for River Rch & Prof#=UNT 01648 IN LAC,Reach-1,2
Up Type=0
Dn Type=3
Dn Slope=0.005
Boundary for River Rch & Prof#=UNT 01648 IN LAC,Reach-1,3
Up Type=0
Dn Type=3
Dn Slope=0.005
Boundary for River Rch & Prof#=UNT 01648 IN LAC,Reach-1,4
Up Type=0
Dn Type=3
Dn Slope=0.005
Boundary for River Rch & Prof#=UNT 01648 IN LAC,Reach-1,5
Up Type=0
Dn Type=3
Dn Slope=0.005
Boundary for River Rch & Prof#=UNT 01648 IN LAC,Reach-1,6
Up Type=0
Dn Type=3
Dn Slope=0.005
Boundary for River Rch & Prof#=UNT 01648 IN LAC,Reach-1,7
Up Type=0
Dn Type=3
Dn Slope=0.005

--- UNT 01648 IN LACR.g01 (geometry) ---

Geom Title=Existing Conditions
Program Version=4.10

River Reach=UNT 01648 IN LAC,Reach-1
Reach XY= 30
      3663149.61     10696710.19       3663048.5       10696697.
      3662919.25       10696522.      3662749.25       10696626.
      3662587.75       10696578.        3662519.       10696695.
       3662327.5       10696669.      3662304.75       10696796.
      3662184.75       10696841.       3662022.5       10696703.
        3661879.       10696711.        3661688.       10696524.
      3661399.75       10696610.       3661085.5       10696523.
        3660828.       10696666.        3660769.       10696850.
      3660384.75       10697119.      3660372.25       10697257.
        3660274.       10697329.      3660176.75       10697336.
      3660136.25       10697218.       3660007.5       10697274.
      3659978.75       10697397.        3659328.       10697498.
      3659006.75       10697260.        3658994.       10697388.
        3658860.       10697337.        3658742.       10697475.
        3658459.       10697540.       3658419.5       10697470.

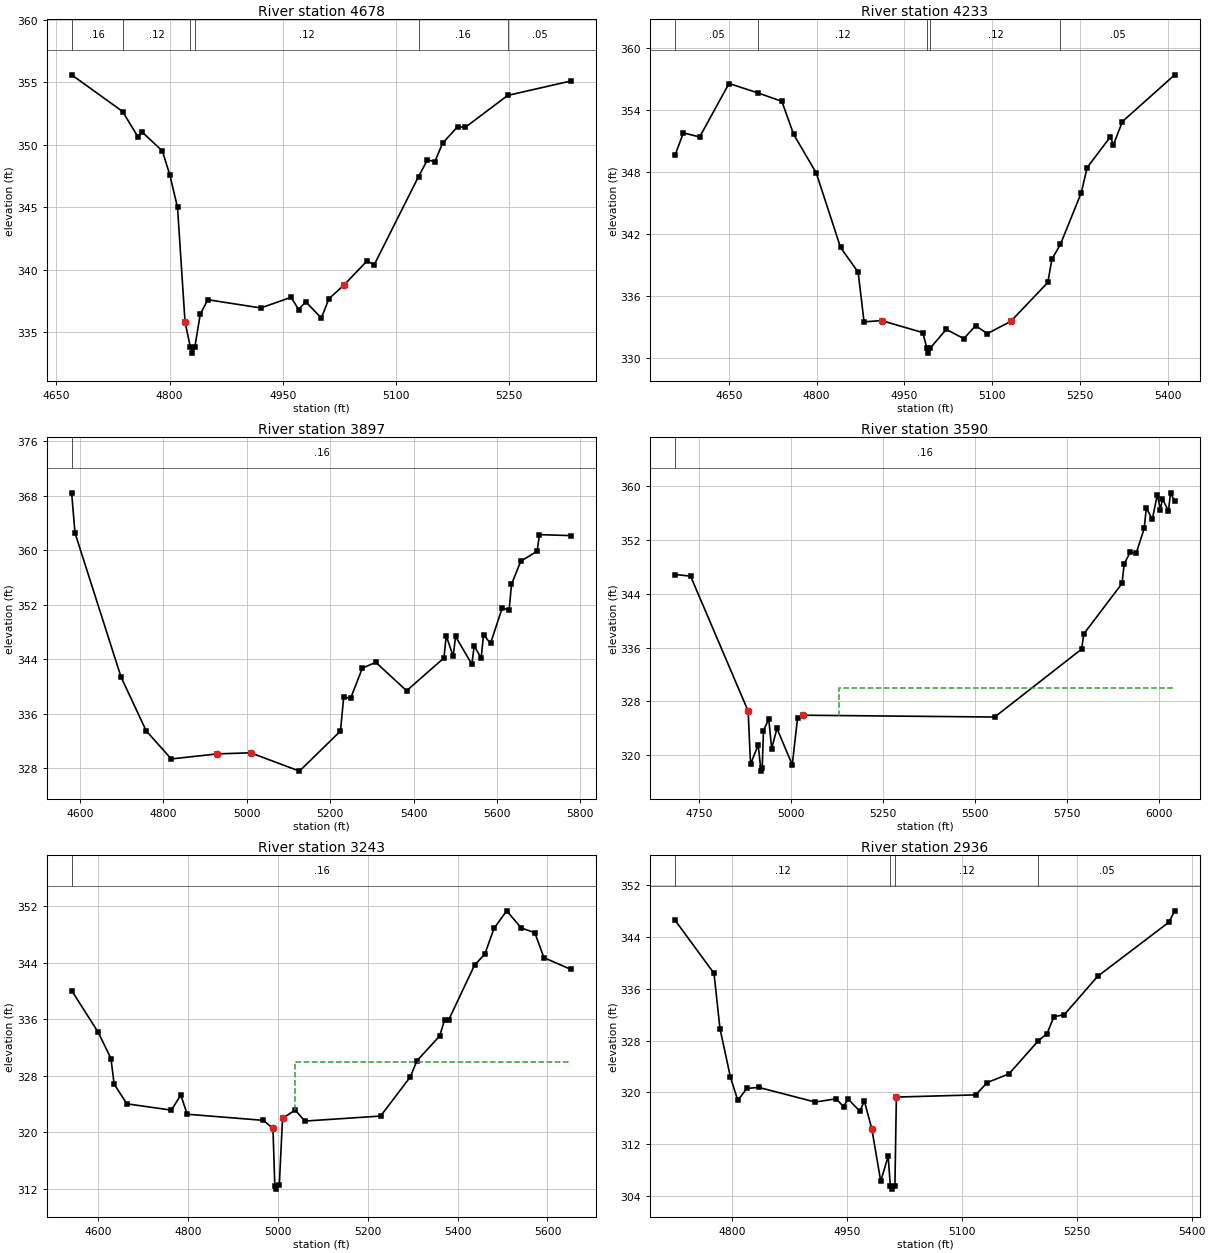
Type RM Length L Ch R = 1 ,4678    ,445,445,445
BEGIN DESCRIPTION:
UNT 01648 IN LACR 13.0
END DESCRIPTION:
XS GIS Cut Line= 2
      3661812.67     10696280.39      3661753.64     10696940.05
#Sta/Elev= 30
  4670.1   355.6  4737.7  352.66  4757.9  350.64  4762.9  351.05  4790.4   349.5
  4800.4  347.55  4810.5  344.97  4820.5  335.76  4827.5   333.8  4830.3   333.3
  4833.5   333.8  4840.6  336.41  4850.6  337.58  4920.9  336.92  4961.1  337.77
  4971.1  336.79  4980.5  337.42  5001.2  336.11  5011.3  337.66  5031.3  338.76
  5061.5  340.67  5071.5   340.4  5130.1  347.45  5141.8  348.78  5151.8  348.65
  5161.9  350.11  5181.9  351.45    5192  351.39  5248.3  353.95  5332.4  355.11
#Mann= 6 ,-1 , 0
  4670.1     .16       0  4737.7     .12       0  4827.5     .07       0
  4833.5     .12       0  5130.1     .16       0  5248.3     .05       0
Bank Sta=4820.5,5031.3
XS Rating Curve= 0 ,0
Exp/Cntr=0.3,0.1

Type RM Length L Ch R = 1 ,4233    ,336,336,336
BEGIN DESCRIPTION:
UNT 01648 IN LACR 8.0
END DESCRIPTION:
XS GIS Cut Line= 3
      3661445.56     10696168.59      3661397.82     10696724.15
      3661423.86      10697019.3
#Sta/Elev= 30
  4558.2  349.69  4572.1   351.8  4599.9   351.4  4650.1  356.58    4700  355.66
  4740.5  354.85  4760.5  351.67  4799.3  347.91  4840.8   340.7  4870.9  338.31
    4881   333.5  4911.1  333.62  4981.3  332.46  4988.4  330.97  4991.1  330.47
  4994.4  330.97  5021.5  332.77  5051.6  331.87  5071.7  333.13  5091.8  332.36
  5131.9  333.55  5195.1  337.31  5202.2  339.58  5216.7     341  5252.4  346.01
  5262.4  348.44  5302.2  351.42  5307.2  350.62  5322.6  352.89  5412.1  357.42
#Mann= 5 ,-1 , 0
  4558.2     .05       0    4700     .12       0  4988.4     .07       0
  4994.4     .12       0  5216.7     .05       0
Bank Sta=4911.1,5131.9
XS Rating Curve= 0 ,0
Exp/Cntr=0.3,0.1

Type RM Length L Ch R = 1 ,3897    ,307,307,307
BEGIN DESCRIPTION:
Mapping XS 56166370
END DESCRIPTION:
XS GIS Cut Line= 3
      3661076.64     10696112.21      3661133.06     10696754.54
      3661380.46     10697249.33
#Sta/Elev= 30
  4579.9  368.43  4587.9  362.56  4698.3   341.4  4758.6   333.5  4818.8  329.36
  4929.2   330.1  5009.2  330.26  5126.3  327.57  5224.7  333.46  5232.4  338.41
  5249.2  338.29  5277.1  342.68  5309.3  343.55  5383.3  339.37  5472.8  344.18
  5478.4  347.44  5495.1  344.43  5500.7  347.35  5539.8  343.26  5545.4  345.94
  5562.2  344.17  5567.8  347.62  5584.6  346.31  5612.5  351.51  5629.3  351.24
  5634.9     355  5657.2  358.39  5696.4  359.85    5702  362.29  5777.9  362.15
#Mann= 1 ,-1 , 0
  4579.9     .16       0
Bank Sta=4929.2,5009.2
XS Rating Curve= 0 ,0
Exp/Cntr=0.3,0.1

Type RM Length L Ch R = 1 ,3590    ,347,347,347
BEGIN DESCRIPTION:
Mapping XS 518543b8
END DESCRIPTION:
XS GIS Cut Line= 3
      3660655.64     10696416.01      3660955.11     10696780.58
      3661371.77     10697561.81
#Sta/Elev= 30
  4685.7  346.85  4727.4  346.61  4883.8  326.55  4890.3  318.67  4911.1  321.53
  4918.7  317.63    4922  318.13  4925.5  323.66  4939.8  325.39  4947.7  320.94
    4962  323.99  5003.7  318.57    5018  325.51  5032.4  325.94  5553.7  325.67
    5790  335.77  5795.7  338.01  5899.8  345.53  5905.5   348.4  5921.7  350.15
    5938  349.99    5960  353.69  5965.7  356.75    5982  355.04  5995.7  358.73
  6003.9  356.51  6009.6  358.09  6025.9  356.29  6031.5  358.99  6042.9  357.72
#Mann= 1 ,-1 , 0
  4685.7     .16       0
#XS Ineff= 2 , 0
       0                 5131.42       0     330
Permanent Ineff=
       F       F
Bank Sta=4883.8,5032.4
XS Rating Curve= 0 ,0
Exp/Cntr=0.3,0.1

Type RM Length L Ch R = 1 ,3243    ,307,307,307
BEGIN DESCRIPTION:
UNT 01648 IN LACR 7.0
END DESCRIPTION:
XS GIS Cut Line= 3
      3660360.46     10696615.62      3660794.52       10697041.
      3660863.97     10697540.15
#Sta/Elev= 30
  4540.9  340.06  4600.1  334.15  4628.4  330.43  4635.5  326.82  4663.8  324.03
  4762.8  323.14  4783.9  325.27  4798.1  322.56  4967.8  321.69    4989  320.54
  4993.1  312.46  4995.9  311.96  5003.1  312.53  5010.3  321.96  5038.5  323.16
  5059.7  321.59  5228.6   322.3  5294.3   327.8  5309.4  330.12  5359.9  333.62
    5371  335.88    5380   335.9  5437.6  343.64  5460.8  345.25    5481  348.85
  5509.2  351.34  5541.6  348.92  5571.9  348.23  5592.1  344.71  5652.6  343.04
#Mann= 1 ,-1 , 0
  4540.9     .16       0
#XS Ineff= 2 , 0
       0                 5037.28       0     330
Permanent Ineff=
       F       F
Bank Sta=4989,5010.3
XS Rating Curve= 0 ,0
Exp/Cntr=0.3,0.1

Type RM Length L Ch R = 1 ,2936    ,676,676,676
BEGIN DESCRIPTION:
UNT 01648 IN LACR 6.0
END DESCRIPTION:
XS GIS Cut Line= 3
      3660299.59     10696860.15      3660449.61     10697110.19
      3660649.58     10697410.15
#Sta/Elev= 30
  4725.8  346.58  4776.4   338.4  4784.2  329.86  4797.8  322.36  4807.5  318.73
  4819.1  320.59  4834.7  320.76  4908.5  318.49  4935.8  318.99  4945.5   317.8
  4951.3  318.97  4966.9  317.07  4972.7  318.65  4982.4  314.36  4994.1  306.24
  5003.8  310.13  5006.6  305.52  5009.4  305.02  5012.6  305.52  5014.5  319.26
    5118   319.6  5133.1   321.5  5161.6  322.86    5200  327.99  5211.2  329.08
  5220.2  331.69  5233.7     332  5277.3  337.94  5370.4  346.32  5377.9  348.07
#Mann= 4 ,-1 , 0
  4725.8     .12       0  5006.6     .07       0  5012.6     .12       0
    5200     .05       0
Bank Sta=4982.4,5014.5
XS Rating Curve= 0 ,0
Exp/Cntr=0.3,0.1

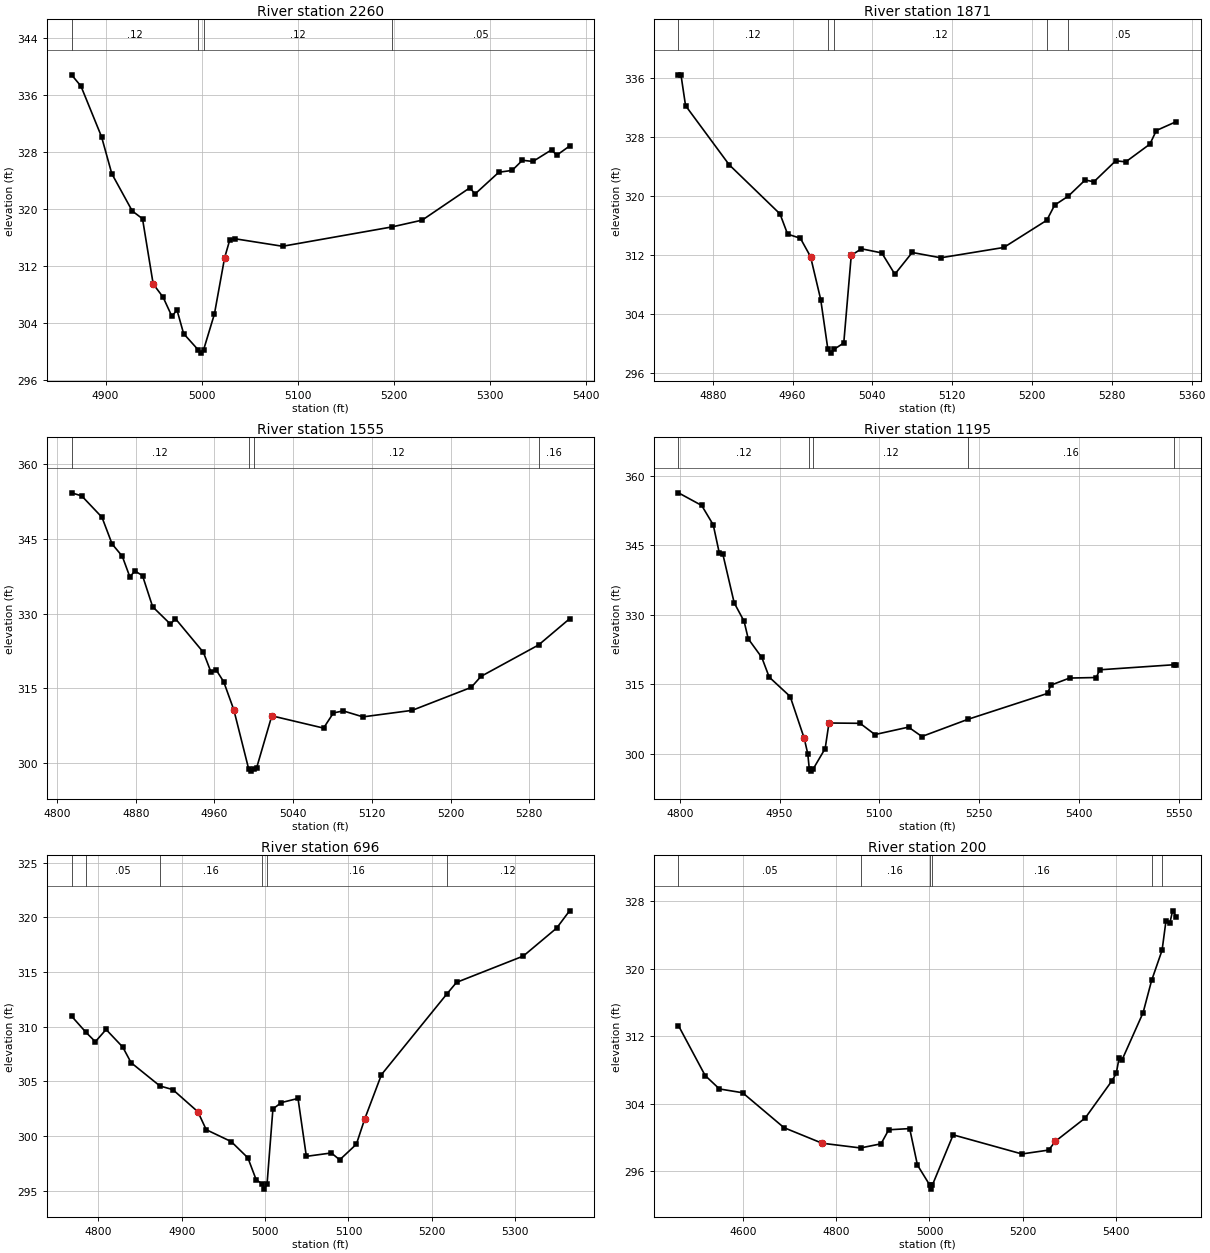
Type RM Length L Ch R = 1 ,2260    ,389,389,389
BEGIN DESCRIPTION:
UNT 01648 IN LACR 5.0
END DESCRIPTION:
XS GIS Cut Line= 2
      3659986.28     10697131.05      3660169.92     10697616.15
#Sta/Elev= 30
  4864.6  338.78  4874.4  337.19  4895.8  330.12  4906.5  324.94  4927.8  319.72
  4938.5  318.63  4949.6   309.5  4959.9  307.66  4969.1  304.97  4974.4  305.86
  4981.3  302.55  4996.2  300.32    4999  299.82  5002.2  300.32  5013.4   305.3
    5024  313.16  5029.4  315.68  5034.8  315.83  5084.4  314.78  5198.4  317.49
  5229.8  318.44  5279.5  322.97  5284.8  322.09  5309.6  325.14  5323.5   325.4
  5334.2  326.82  5345.1  326.65  5364.6  328.28  5369.9  327.52  5383.3  328.81
#Mann= 4 ,-1 , 0
  4864.6     .12       0  4996.2     .07       0  5002.2     .12       0
  5198.4     .05       0
Bank Sta=4949.6,5024
XS Rating Curve= 0 ,0
Exp/Cntr=0.3,0.1

Type RM Length L Ch R = 1 ,1871    ,316,316,316
BEGIN DESCRIPTION:
UNT 01648 IN LACR 4.0
END DESCRIPTION:
XS GIS Cut Line= 2
       3659732.8     10697280.33      3659830.03     10697769.97
#Sta/Elev= 30
  4845.6  336.43  4848.1  336.43  4852.7  332.25  4896.4  324.23  4947.4  317.55
    4955  314.81  4967.8  314.25    4978  311.75  4988.2  305.92  4995.4  299.16
  4998.1  298.66  5001.4  299.16  5011.3  300.04  5018.8  311.93    5029  312.82
  5049.4  312.26  5062.5  309.37  5079.9  312.32  5108.5   311.6  5171.7     313
  5214.8  316.69  5222.7  318.75  5236.4  319.97  5253.3  322.16    5262  321.91
  5283.9  324.76    5294  324.62  5318.2  327.03  5324.6  328.87  5344.8  330.09
#Mann= 5 ,-1 , 0
  4845.6     .12       0  4995.4     .07       0  5001.4     .12       0
  5214.8     .16       0  5236.4     .05       0
Bank Sta=4978,5018.8
XS Rating Curve= 0 ,0
Exp/Cntr=0.3,0.1

Type RM Length L Ch R = 1 ,1555    ,360,360,360
BEGIN DESCRIPTION:
UNT 01648 IN LACR 3.0
END DESCRIPTION:
XS GIS Cut Line= 3
      3659449.62     10697260.22      3659499.61     10697460.19
      3659499.61     10697760.17
#Sta/Elev= 30
  4814.8  354.29  4825.1  353.67  4845.7  349.37    4856  343.99  4866.3  341.54
    4874  337.39  4879.2  338.55  4886.9  337.63  4897.2  331.36  4915.3  327.86
  4920.4  328.95  4948.8  322.18  4956.5   318.2  4961.7  318.66  4969.4  316.27
  4979.7  310.61  4994.7  298.78  4997.5  298.28  5000.7  298.78  5002.9  298.96
  5018.3  309.41  5070.9  306.94  5080.9  309.99  5090.9   310.4  5110.9   309.2
  5160.9  310.51  5220.9  315.13  5230.9  317.35  5289.4  323.67  5320.9  328.94
#Mann= 4 ,-1 , 0
  4814.8     .12       0  4994.7     .07       0  5000.7     .12       0
  5289.4     .16       0
Bank Sta=4979.7,5018.3
XS Rating Curve= 0 ,0
Exp/Cntr=0.3,0.1

Type RM Length L Ch R = 1 ,1195    ,499,499,499
BEGIN DESCRIPTION:
UNT 01648 IN LACR 2.0
END DESCRIPTION:
XS GIS Cut Line= 3
      3659284.89     10697200.48       3659184.2     10697509.53
      3659239.75     10697929.64
#Sta/Elev= 30
  4797.9  356.29  4832.8  353.57  4850.2  349.39  4859.4  343.25  4864.7  343.03
  4881.7  332.58  4896.6  328.61  4902.8  324.84  4923.2  320.82  4934.3  316.59
  4965.9   312.4  4986.9  303.43  4992.3  300.09  4994.6  296.83  4997.3  296.33
  5000.6  296.83  5018.5   301.2  5024.2   306.7    5071  306.63  5093.3  304.21
  5143.8  305.81  5163.9  303.79  5233.3   307.5  5352.8  313.07  5357.8  314.85
  5385.9  316.38  5426.2   316.5  5431.2  318.16  5542.7  319.25  5546.7  319.21
#Mann= 5 ,-1 , 0
  4797.9     .12       0  4994.6     .07       0  5000.6     .12       0
  5233.3     .16       0  5542.7     .05       0
Bank Sta=4986.9,5024.2
XS Rating Curve= 0 ,0
Exp/Cntr=0.3,0.1

Type RM Length L Ch R = 1 ,696     ,496,496,496
BEGIN DESCRIPTION:
Mapping XS ab19364b
END DESCRIPTION:
XS GIS Cut Line= 2
      3658913.36     10697158.85      3658937.65     10697755.65
#Sta/Elev= 30
  4767.9  310.96  4785.2  309.48  4796.4  308.62  4809.3  309.74  4829.3  308.13
  4839.3   306.7  4873.9  304.57  4889.3  304.24  4919.4  302.21  4929.4  300.57
  4959.4  299.48  4979.4  297.99  4989.4  295.97  4996.4  295.63  4999.2  295.13
  5002.4  295.63  5009.4  302.47  5019.5  303.05  5039.5  303.43  5049.5  298.13
  5079.5  298.44  5089.5  297.81  5109.5  299.24  5119.5  301.55  5139.6  305.61
    5218  312.99  5229.6  314.05  5309.7  316.46  5349.7  319.02  5365.2   320.6
#Mann= 6 ,-1 , 0
  4767.9     .16       0  4785.2     .05       0  4873.9     .16       0
  4996.4     .07       0  5002.4     .16       0    5218     .12       0
Bank Sta=4919.4,5119.5
XS Rating Curve= 0 ,0
Exp/Cntr=0.3,0.1

Type RM Length L Ch R = 1 ,200     ,0,0,0
BEGIN DESCRIPTION:
UNT 01648 IN LACR 1.0
END DESCRIPTION:
XS GIS Cut Line= 4
      3658746.72     10697009.49      3658527.95      10697426.2
      3658590.45      10697575.5      3658958.52     10697811.62
#Sta/Elev= 30
  4460.8  313.25  4518.1  307.35  4548.8  305.76  4598.6  305.31  4687.5  301.18
  4769.4  299.34  4851.9  298.78    4896  299.27  4912.4  300.93  4957.5  301.07
  4974.2  296.75  5000.4  294.41  5003.1  293.91  5006.4  294.41  5050.9  300.33
  5198.6  298.07  5256.1  298.53  5270.5  299.57  5334.7  302.33  5392.2  306.74
  5401.2  307.59  5407.4  309.42  5413.3  309.15  5458.9  314.78  5477.2  318.59
  5499.7  322.17  5508.1  325.65  5516.4  325.39  5522.3  326.83  5530.6  326.13
#Mann= 6 ,-1 , 0
  4460.8     .05       0  4851.9     .16       0  5000.4     .07       0
  5006.4     .16       0  5477.2     .12       0  5499.7     .16       0
Bank Sta=4769.4,5270.5
XS Rating Curve= 0 ,0
Exp/Cntr=0.3,0.1

Chan Stop Cuts=-1
Use User Specified Reach Order=0
Composite Channel Slope=5