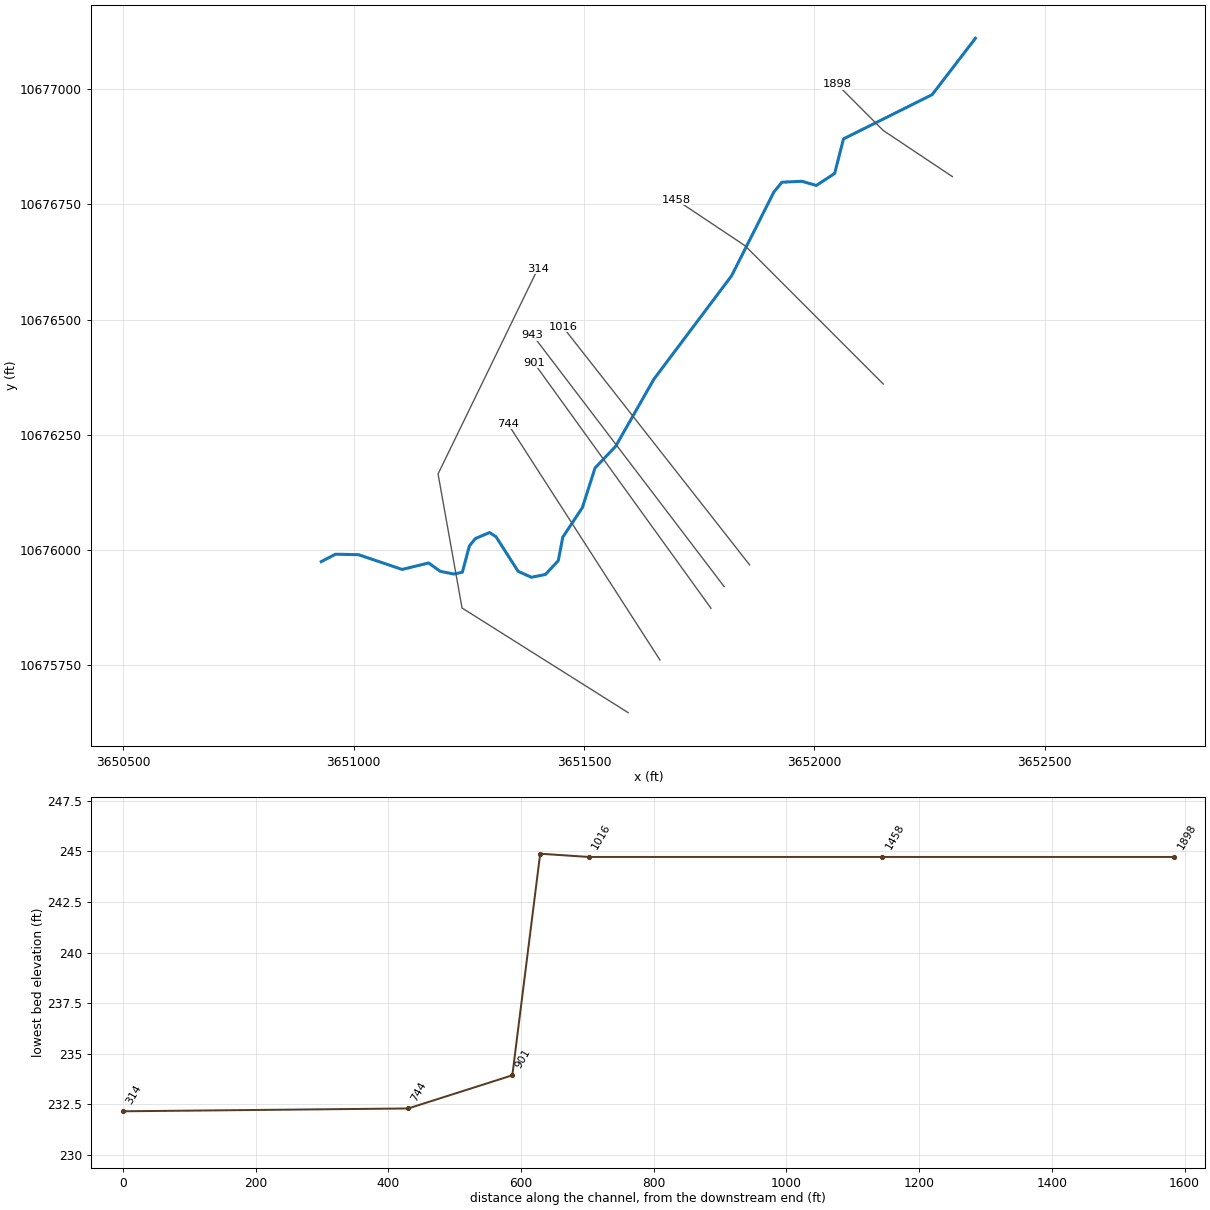
--- UNT 0168 IN LACR.prj (project) ---

Proj Title=UNT 0168 IN LACR Base Level Engineering
Current Plan=p01
Default Exp/Contr=0.3,0.1
English Units
Geom File=g01
Flow File=f01
Plan File=p01
BEGIN DESCRIPTION:
UNT 0168 IN LACR
END DESCRIPTION:

--- UNT 0168 IN LACR.p01 (plan) ---

Plan Title=Multiple Run
Short Identifier=Multiple
Geom File=g01
Flow File=f01
Subcritical Flow
K Sum by GR= 0
Std Step Tol= 0.01
Critical Tol= 0.01
Num of Std Step Trials= 20
Max Error Tol= 0.3
Flow Tol Ratio= 0.001
Split Flow NTrial= 30
Split Flow Tol= 0.02
Split Flow Ratio= 0.02
Log Output Level= 0
Friction Slope Method= 1
Unsteady Friction Slope Method= 2
Unsteady Bridges Friction Slope Method= 1
Parabolic Critical Depth
Global Vel Dist=  1 , 1 , 1
Global Log Level= 0
CheckData=True
Encroach Param= -1, 0, 0, 0
BEGIN DESCRIPTION:
Multiple Run
END DESCRIPTION:

--- UNT 0168 IN LACR.f01 (steady flow) ---

Flow Title=Multiple
Number of Profiles=7
Profile Names=10-year,25-year,50-year,1pct_min,100-year,1pct_plu,500-year
River Rch & RM= UNT 0168 IN LACR,Reach-1,1898
     133     165     189     160     216     292     284
Boundary for River Rch & Prof#=UNT 0168 IN LACR,Reach-1,1
Up Type=0
Dn Type=3
Dn Slope=0.005
Boundary for River Rch & Prof#=UNT 0168 IN LACR,Reach-1,2
Up Type=0
Dn Type=3
Dn Slope=0.005
Boundary for River Rch & Prof#=UNT 0168 IN LACR,Reach-1,3
Up Type=0
Dn Type=3
Dn Slope=0.005
Boundary for River Rch & Prof#=UNT 0168 IN LACR,Reach-1,4
Up Type=0
Dn Type=3
Dn Slope=0.005
Boundary for River Rch & Prof#=UNT 0168 IN LACR,Reach-1,5
Up Type=0
Dn Type=3
Dn Slope=0.005
Boundary for River Rch & Prof#=UNT 0168 IN LACR,Reach-1,6
Up Type=0
Dn Type=3
Dn Slope=0.005
Boundary for River Rch & Prof#=UNT 0168 IN LACR,Reach-1,7
Up Type=0
Dn Type=3
Dn Slope=0.005

--- UNT 0168 IN LACR.g01 (geometry) ---

Geom Title=Existing Conditions

River Reach=UNT 0168 IN LACR,Reach-1
Reach XY= 30
      3652349.61     10677110.19      3652255.75     10676988.00
      3652063.25     10676892.00      3652044.00     10676817.00
      3652004.25     10676791.00      3651973.00     10676800.00
      3651929.50     10676798.00      3651912.25     10676777.00
      3651820.25     10676595.00      3651651.75     10676371.00
      3651568.50     10676225.00      3651523.75     10676178.00
      3651496.25     10676092.00      3651453.75     10676028.00
      3651444.00     10675977.00      3651416.00     10675947.00
      3651385.50     10675941.00      3651356.75     10675954.00
      3651308.75     10676029.00      3651294.75     10676038.00
      3651264.00     10676025.00      3651251.00     10676009.00
      3651235.75     10675952.00      3651217.50     10675948.00
      3651187.50     10675954.00      3651162.50     10675972.00
      3651105.00     10675958.00      3651010.25     10675990.00
      3650960.25     10675991.00      3650929.50     10675975.00

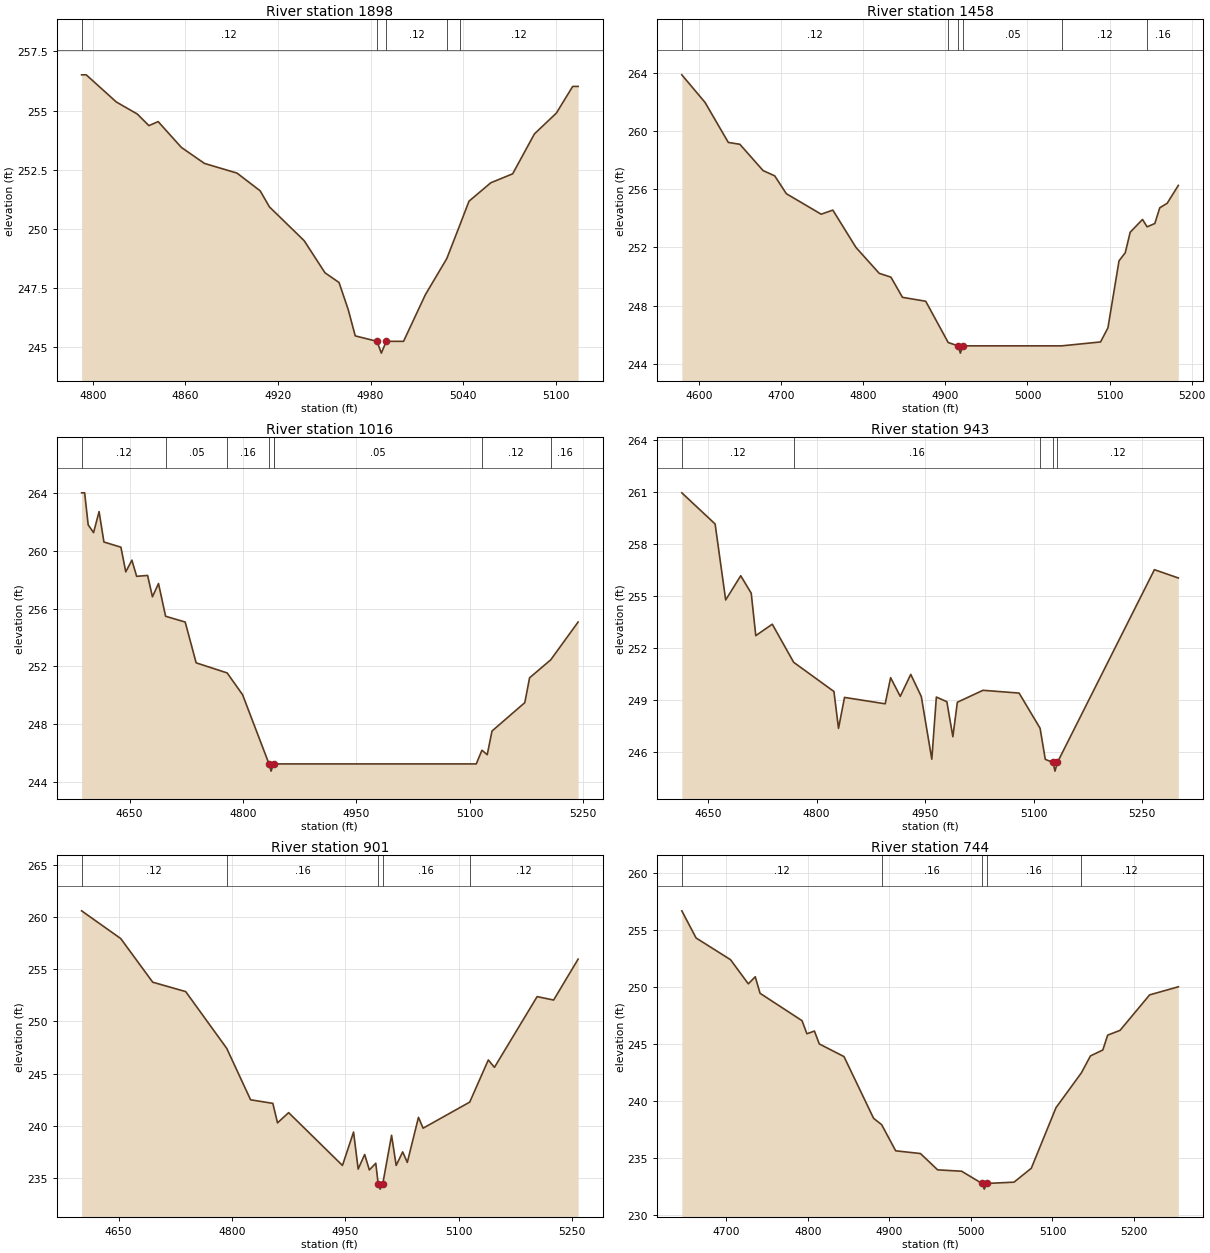
Type RM Length L Ch R = 1,1898,440,440,440
BEGIN DESCRIPTION:
UNT 0168 IN LACR 4.0
END DESCRIPTION:
XS GIS Cut Line= 3
      3652299.61     10676810.19      3652149.61     10676910.19
      3652049.61     10677010.19
#Sta/Elev= 30
  4792.8  256.51  4795.8  256.51  4815.3  255.36  4828.9  254.85  4836.4  254.36
  4842.4  254.53  4857.4  253.44  4872.4  252.76  4893.5  252.35  4908.5  251.60
  4914.5  250.92  4937.0  249.49  4950.5  248.13  4959.6  247.72  4965.6  246.56
  4970.1  245.46  4984.2  245.23  4987.0  244.73  4990.2  245.23  5001.4  245.23
  5015.5  247.20  5029.4  248.73  5037.8  250.14  5043.8  251.16  5057.9  251.94
  5072.1  252.32  5086.2  254.01  5100.4  254.89  5111.0  256.02  5114.5  256.02
#Mann=5,-1,0
  4792.8    0.12       0  4984.2    0.07       0  4990.2    0.12       0
  5029.4    0.16       0  5037.8    0.12       0
Bank Sta=4984.2,4990.2
Exp/Cntr=0.3,0.1

Type RM Length L Ch R = 1,1458,442,442,442
BEGIN DESCRIPTION:
UNT 0168 IN LACR 3.0
END DESCRIPTION:
XS GIS Cut Line= 3
      3652149.62     10676360.18      3651849.61     10676660.19
      3651699.57     10676760.21
#Sta/Elev= 30
  4579.1  263.88  4607.4  261.98  4635.7  259.23  4649.8  259.10  4678.1  257.29
  4692.2  256.93  4706.4  255.70  4748.8  254.29  4763.0  254.57  4791.2  252.00
  4819.5  250.22  4833.7  249.96  4847.8  248.57  4876.1  248.30  4903.5  245.46
  4915.5  245.23  4918.3  244.73  4921.5  245.23  5041.7  245.23  5089.0  245.50
  5098.0  246.47  5111.5  251.08  5119.1  251.64  5125.1  253.05  5140.1  253.93
  5145.7  253.42  5155.1  253.65  5161.1  254.73  5170.1  255.04  5183.7  256.27
#Mann=6,-1,0
  4579.1    0.12       0  4903.5    0.05       0  4915.5   0.033       0
  4921.5    0.05       0  5041.7    0.12       0  5145.7    0.16       0
Bank Sta=4915.5,4921.5
Exp/Cntr=0.3,0.1

Type RM Length L Ch R = 1,1016,73,73,73
BEGIN DESCRIPTION:
UNT 0168 IN LACR 2.0
END DESCRIPTION:
XS GIS Cut Line= 2
      3651859.52     10675967.80      3651453.85     10676484.22
#Sta/Elev= 30
  4586.5  264.03  4590.5  264.03  4595.2  261.81  4602.3  261.27  4609.6  262.73
  4616.0  260.62  4638.5  260.26  4644.9  258.55  4653.0  259.36  4659.3  258.24
  4673.8  258.30  4680.2  256.82  4688.2  257.74  4697.6  255.47  4723.5  255.07
  4738.0  252.24  4779.0  251.54  4799.4  250.03  4834.4  245.23  4837.1  244.73
  4840.4  245.23  4841.1  245.23  5108.5  245.23  5116.0  246.18  5123.0  245.87
  5129.3  247.51  5172.7  249.48  5179.0  251.20  5207.0  252.45  5243.2  255.07
#Mann=8,-1,0
  4586.5    0.12       0  4697.6    0.05       0  4779.0    0.16       0
  4834.4   0.033       0  4840.4    0.16       0  4841.1    0.05       0
  5116.0    0.12       0  5207.0    0.16       0
Bank Sta=4834.4,4840.4
Exp/Cntr=0.3,0.1

Type RM Length L Ch R = 1,943,42,42,42
BEGIN DESCRIPTION:
Mapping XS 1d0718f6
END DESCRIPTION:
XS GIS Cut Line= 2
      3651804.14     10675920.73      3651388.40     10676466.40
#Sta/Elev= 30
  4613.7  260.97  4659.7  259.17  4674.3  254.78  4695.1  256.18  4709.6  255.17
  4715.9  252.72  4738.7  253.38  4768.2  251.18  4823.9  249.49  4830.2  247.36
  4838.5  249.15  4894.7  248.78  4902.2  250.29  4915.5  249.21  4930.0  250.48
  4944.6  249.20  4959.1  245.58  4965.4  249.17  4979.9  248.90  4988.2  246.88
  4994.4  248.87  5029.8  249.56  5079.7  249.40  5108.7  247.37  5115.9  245.57
  5126.6  245.39  5129.3  244.89  5132.6  245.39  5266.7  256.53  5299.7  256.05
#Mann=5,-1,0
  4613.7    0.12       0  4768.2    0.16       0  5108.7    0.12       0
  5126.6    0.07       0  5132.6    0.12       0
Bank Sta=5126.6,5132.6
Exp/Cntr=0.3,0.1

Type RM Length L Ch R = 1,901,157,157,157
BEGIN DESCRIPTION:
Mapping XS 9ce876a2
END DESCRIPTION:
XS GIS Cut Line= 2
      3651775.48     10675873.88      3651390.97     10676406.48
#Sta/Elev= 30
  4601.2  260.60  4653.0  257.94  4695.3  253.76  4738.9  252.86  4793.2  247.42
  4824.8  242.49  4854.2  242.15  4860.4  240.28  4875.1  241.26  4946.3  236.20
  4961.0  239.40  4967.1  235.85  4975.7  237.25  4981.9  235.77  4990.4  236.41
  4993.6  234.43  4996.3  233.93  4999.6  234.43  5011.3  239.09  5017.4  236.20
  5026.0  237.50  5032.1  236.49  5046.9  240.81  5053.0  239.77  5114.7  242.27
  5139.3  246.31  5147.4  245.60  5203.9  252.38  5225.7  252.05  5258.1  255.97
#Mann=5,-1,0
  4601.2    0.12       0  4793.2    0.16       0  4993.6    0.07       0
  4999.6    0.16       0  5114.7    0.12       0
Bank Sta=4993.6,4999.6
Exp/Cntr=0.3,0.1

Type RM Length L Ch R = 1,744,430,430,430
BEGIN DESCRIPTION:
Mapping XS dce855e5
END DESCRIPTION:
XS GIS Cut Line= 2
      3651664.74     10675761.54      3651334.87     10676273.71
#Sta/Elev= 30
  4645.2  256.69  4662.7  254.31  4704.9  252.41  4726.8  250.29  4735.3  250.91
  4741.2  249.46  4792.7  247.06  4798.7  245.91  4807.9  246.15  4813.9  245.02
  4844.2  243.91  4880.5  238.50  4890.4  237.94  4907.6  235.65  4938.0  235.41
  4959.1  233.98  4988.5  233.86  5013.5  232.79  5016.3  232.29  5019.5  232.79
  5052.8  232.90  5074.0  234.12  5104.3  239.43  5135.5  242.49  5146.6  243.97
  5161.8  244.49  5167.7  245.79  5182.9  246.21  5219.2  249.32  5254.4  250.03
#Mann=5,-1,0
  4645.2    0.12       0  4890.4    0.16       0  5013.5    0.07       0
  5019.5    0.16       0  5135.5    0.12       0
Bank Sta=5013.5,5019.5
Exp/Cntr=0.3,0.1

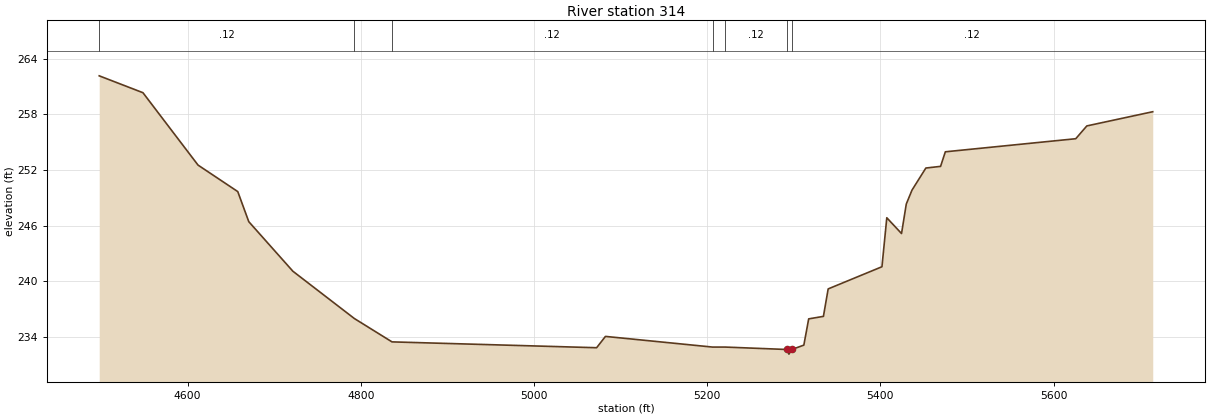
Type RM Length L Ch R = 1,314,0,0,0
BEGIN DESCRIPTION:
UNT 0168 IN LACR 1.0
END DESCRIPTION:
XS GIS Cut Line= 4
      3651595.80     10675647.29      3651235.07     10675874.37
      3651182.98     10676165.17      3651399.60     10676610.16
#Sta/Elev= 30
  4498.0  262.15  4548.5  260.33  4612.1  252.53  4658.0  249.67  4670.7  246.43
  4721.6  241.09  4792.6  235.99  4836.1  233.47  5072.4  232.84  5082.6  234.06
  5206.3  232.91  5221.1  232.91  5291.8  232.65  5294.5  232.15  5297.8  232.65
  5311.7  233.12  5317.3  235.95  5334.3  236.22  5339.8  239.18  5401.9  241.57
  5407.5  246.85  5424.5  245.15  5430.0  248.33  5436.6  249.83  5452.6  252.21
  5469.6  252.39  5475.1  253.96  5625.7  255.37  5638.5  256.75  5714.6  258.28
#Mann=7,-1,0
  4498.0    0.12       0  4792.6    0.16       0  4836.1    0.12       0
  5206.3    0.07       0  5221.1    0.12       0  5291.8    0.07       0
  5297.8    0.12       0
Bank Sta=5291.8,5297.8
Exp/Cntr=0.3,0.1

Chan Stop Cuts=-1