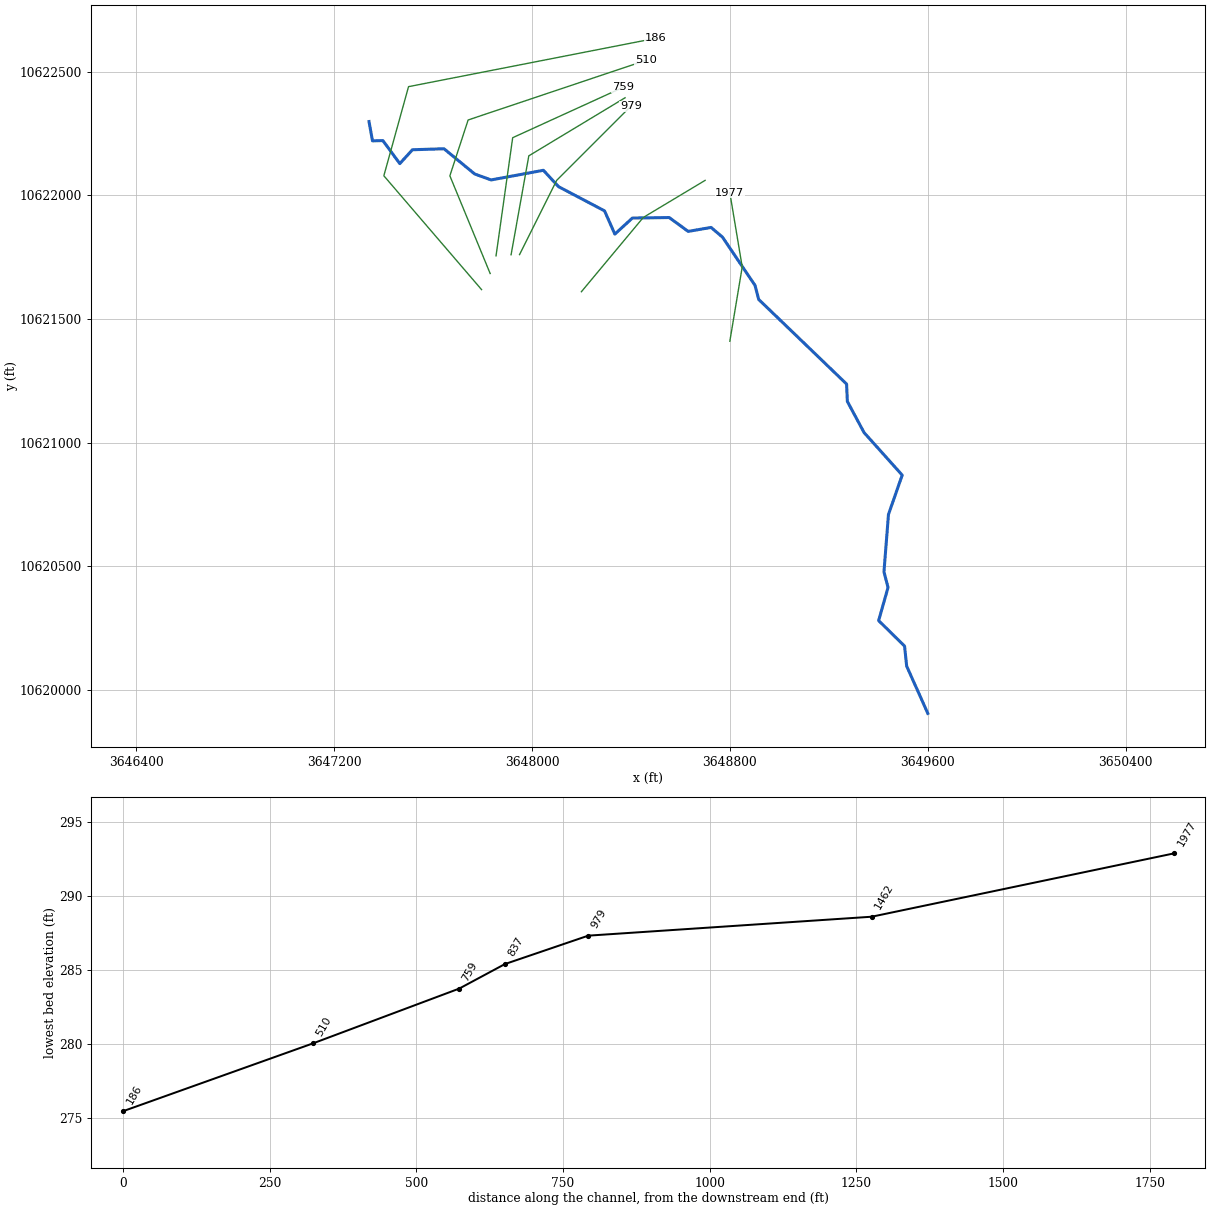
--- UNT 01873 IN LACR.prj (project) ---

Proj Title=UNT 01873 IN LACR Base Level Engineering
Current Plan=p01
Default Exp/Contr=0.3,0.1
English Units
Geom File=g01
Flow File=f01
Plan File=p01
Y Axis Title=Elevation
X Axis Title(PF)=Main Channel Distance
X Axis Title(XS)=Station
BEGIN DESCRIPTION:
UNT 01873 IN LACR
END DESCRIPTION:
DSS Export Rating Curves= 0
DSS Export Rating Curve Sorted= 0
DSS Export Volume Flow Curves= 0
DXF OffsetX= 0
DXF OffsetY= 0
DXF ScaleX= 1
DXF ScaleY= 10

--- UNT 01873 IN LACR.p01 (plan) ---

Plan Title=Multiple Run
Short Identifier=Multiple
Geom File=g01
Flow File=f01
Subcritical Flow
K Sum by GR= 0
Std Step Tol= 0.01
Critical Tol= 0.01
Num of Std Step Trials= 20
Max Error Tol= 0.3
Flow Tol Ratio= 0.001
Split Flow NTrial= 30
Split Flow Tol= 0.02
Split Flow Ratio= 0.02
Log Output Level= 0
Friction Slope Method= 1
Unsteady Friction Slope Method= 2
Unsteady Bridges Friction Slope Method= 1
Parabolic Critical Depth
Global Vel Dist=  1 , 1 , 1
Global Log Level= 0
CheckData=True
Encroach Param= -1, 0, 0, 0
BEGIN DESCRIPTION:
Multiple Run
END DESCRIPTION:

--- UNT 01873 IN LACR.f01 (steady flow) ---

Flow Title=Multiple
Program Version=4.10
Number of Profiles= 7
Profile Names=10-year,25-year,50-year,1pct_min,100-year,1pct_plu,500-year
River Rch & RM=UNT 01873 IN LAC,Reach-1         ,1977
     304     400     479     422     571     772     814
Boundary for River Rch & Prof#=UNT 01873 IN LAC,Reach-1         , 1
Up Type= 0
Dn Type= 3
Dn Slope=0.014
Boundary for River Rch & Prof#=UNT 01873 IN LAC,Reach-1         , 2
Up Type= 0
Dn Type= 3
Dn Slope=0.014
Boundary for River Rch & Prof#=UNT 01873 IN LAC,Reach-1         , 3
Up Type= 0
Dn Type= 3
Dn Slope=0.014
Boundary for River Rch & Prof#=UNT 01873 IN LAC,Reach-1         , 4
Up Type= 0
Dn Type= 3
Dn Slope=0.014
Boundary for River Rch & Prof#=UNT 01873 IN LAC,Reach-1         , 5
Up Type= 0
Dn Type= 3
Dn Slope=0.014
Boundary for River Rch & Prof#=UNT 01873 IN LAC,Reach-1         , 6
Up Type= 0
Dn Type= 3
Dn Slope=0.014
Boundary for River Rch & Prof#=UNT 01873 IN LAC,Reach-1         , 7
Up Type= 0
Dn Type= 3
Dn Slope=0.014
DSS Import GetInterval= 0
DSS Import GetPeak= 0
DSS Import FillOption= 0

--- UNT 01873 IN LACR.g01 (geometry) ---

Geom Title=Existing Conditions
Program Version=4.10

River Reach=UNT 01873 IN LAC,Reach-1
Reach XY= 30
      3649599.75       10619906.      3649514.25       10620097.
      3649505.75       10620178.        3649401.       10620281.
        3649439.       10620415.       3649422.5       10620478.
      3649440.75       10620710.      3649496.25       10620869.
        3649342.       10621041.       3649274.5       10621167.
       3649271.5       10621237.      3648916.25       10621579.
      3648901.25       10621636.      3648769.75       10621831.
      3648723.75       10621870.      3648631.25       10621854.
       3648554.5       10621910.      3648405.75       10621908.
      3648334.75       10621843.      3648293.25       10621937.
        3648107.       10622035.        3648046.       10622101.
      3647834.75       10622062.       3647768.5       10622086.
      3647644.25       10622188.      3647516.75       10622184.
      3647465.75       10622128.      3647397.25       10622221.
      3647355.25       10622220.      3647341.25       10622298.

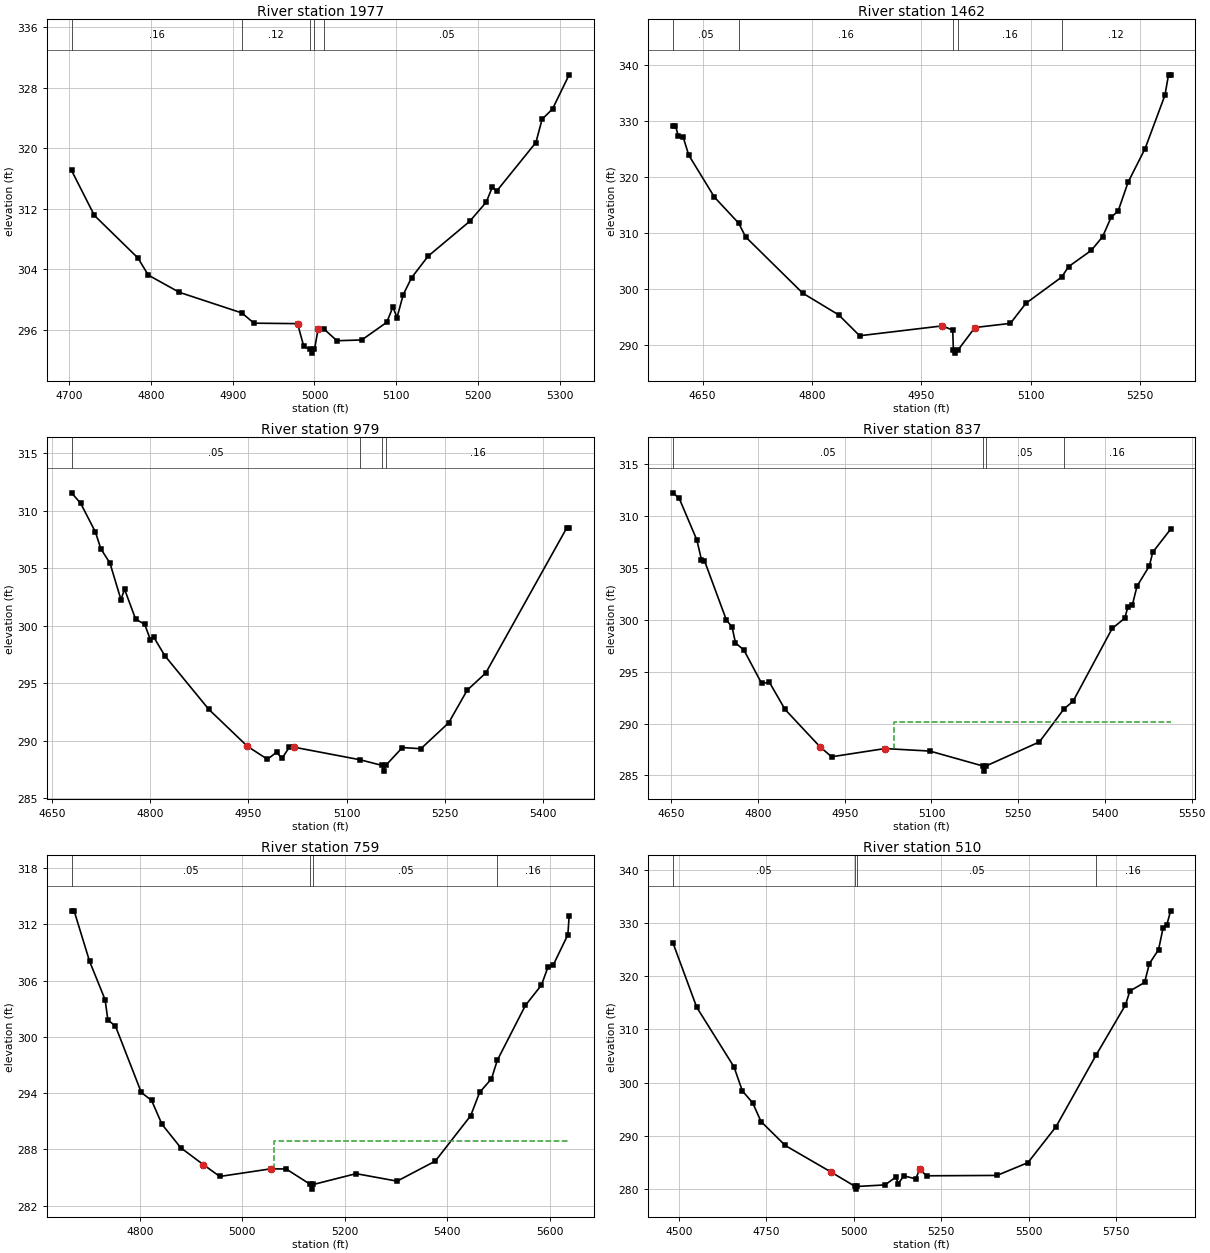
Type RM Length L Ch R = 1 ,1977    ,515,515,515
BEGIN DESCRIPTION:
UNT 01873 IN LACR 4.0
END DESCRIPTION:
XS GIS Cut Line= 3
      3648799.61     10621410.18      3648849.61     10621710.19
      3648799.61      10622010.2
#Sta/Elev= 30
    4703  317.06  4730.9  311.11  4784.1  305.49  4796.8  303.22  4834.8  300.94
  4911.3  298.21    4926  296.86  4979.3   296.8  4986.9  293.79    4994   293.4
  4996.8   292.9    5000   293.4  5004.6  296.15  5011.3  296.12  5027.4  294.54
  5057.8  294.64  5088.3  296.97  5095.9     299  5100.9   297.6  5108.5  300.63
  5118.7  302.87  5138.9  305.72  5189.6  310.31  5209.9  312.85  5217.5  314.86
  5222.6  314.31  5270.7  320.75  5278.3  323.83    5291  325.18  5311.3   329.7
#Mann= 5 ,-1 , 0
    4703     .16       0  4911.3     .12       0    4994     .07       0
    5000     .12       0  5011.3     .05       0
Bank Sta=4979.3,5004.6
XS Rating Curve= 0 ,0
Exp/Cntr=0.3,0.1

Type RM Length L Ch R = 1 ,1462    ,483,483,483
BEGIN DESCRIPTION:
UNT 01873 IN LACR 3.0
END DESCRIPTION:
XS GIS Cut Line= 3
      3648199.59     10621610.16      3648449.61     10621910.19
      3648699.61     10622060.19
#Sta/Elev= 30
  4609.5  329.21  4612.8  329.21  4616.7  327.32  4623.2  327.23    4631  323.95
  4666.2  316.45  4699.3  311.83  4709.1  309.34  4787.2  299.33  4836.7  295.43
  4865.3  291.72  4978.6  293.48  4992.9  292.72  4993.8  289.12  4996.5  288.62
  4999.8  289.12  5023.4  293.19    5072  293.93  5093.3  297.52  5142.3  302.19
  5151.7  304.05  5182.8  306.94  5198.3  309.38    5210  312.84  5219.7  313.98
  5233.3  319.11  5256.6  325.11  5283.8  334.62  5288.7  338.27  5291.6  338.27
#Mann= 5 ,-1 , 0
  4609.5     .05       0  4699.3     .16       0  4993.8     .07       0
  4999.8     .16       0  5142.3     .12       0
Bank Sta=4978.6,5023.4
XS Rating Curve= 0 ,0
Exp/Cntr=0.3,0.1

Type RM Length L Ch R = 1 ,979     ,142,142,142
BEGIN DESCRIPTION:
UNT 01873 IN LACR 2.0
END DESCRIPTION:
XS GIS Cut Line= 3
      3647949.62     10621760.21      3648099.61     10622060.19
      3648399.64     10622360.22
#Sta/Elev= 30
  4680.1  311.54  4694.1  310.62  4716.4  308.15  4724.8  306.68  4738.8  305.42
  4755.5  302.26  4761.1  303.15  4777.9  300.56  4791.9   300.1  4800.3  298.78
  4805.9  298.96  4822.6  297.37  4889.7  292.71  4948.4  289.51  4979.2  288.37
  4993.1  288.98  5001.5  288.45  5012.7  289.43    5019  289.43  5120.5  288.33
  5153.9  287.84  5156.7  287.34  5159.9  287.84  5185.2  289.39  5213.5  289.29
  5255.9  291.54  5284.2  294.38  5312.5  295.87  5436.2  308.49  5439.8  308.49
#Mann= 4 ,-1 , 0
  4680.1     .05       0  5120.5     .16       0  5153.9     .03       0
  5159.9     .16       0
Bank Sta=4948.4,5019
XS Rating Curve= 0 ,0
Exp/Cntr=0.3,0.1

Type RM Length L Ch R = 1 ,837     ,78,78,78
BEGIN DESCRIPTION:
Mapping XS ce482ebf
END DESCRIPTION:
XS GIS Cut Line= 3
      3647915.45     10621759.63      3647987.05     10622159.34
      3648376.15      10622394.1
#Sta/Elev= 30
  4653.1  312.19  4663.8  311.65  4694.3  307.65  4702.2  305.76  4707.3  305.68
  4745.1  299.99  4755.3  299.25  4761.1  297.75  4775.6  297.07  4806.1  293.88
  4819.9  293.95  4846.7  291.36  4907.6  287.74  4927.4   286.8  5019.4  287.59
  5097.2  287.35  5188.5  285.92  5191.3  285.42  5194.5  285.92  5286.7  288.23
  5329.3  291.41  5344.9  292.14  5412.5  299.14  5434.2  300.13    5440  301.25
  5447.6  301.44  5455.5  303.21  5476.9  305.16  5482.7  306.48  5513.6  308.69
#Mann= 4 ,-1 , 0
  4653.1     .05       0  5188.5     .03       0  5194.5     .05       0
  5329.3     .16       0
#XS Ineff= 2 , 0
                         5034.89          290.14
Permanent Ineff=
       F       F
Bank Sta=4907.6,5019.4
XS Rating Curve= 0 ,0
Exp/Cntr=0.3,0.1

Type RM Length L Ch R = 1 ,759     ,249,249,249
BEGIN DESCRIPTION:
Mapping XS e94fa1fe
END DESCRIPTION:
XS GIS Cut Line= 3
      3647854.66      10621755.3      3647921.93     10622232.71
      3648367.32     10622435.95
#Sta/Elev= 30
  4666.3  313.43  4671.3  313.43  4701.5  308.05  4731.8  303.96  4737.3  301.78
    4752  301.15  4802.5  294.07  4822.7  293.21  4842.9  290.67  4879.6  288.17
  4923.7  286.37  4955.8  285.11    5055  285.92  5085.3  285.91  5132.8  284.26
  5135.5  283.76  5138.8  284.26    5222  285.41  5302.1  284.61  5376.7  286.75
  5445.8  291.59  5463.3  294.08  5486.4  295.52  5497.7  297.49  5552.6  303.34
    5584  305.52  5596.5   307.4  5607.1  307.66  5635.6  310.89    5638  312.84
#Mann= 4 ,-1 , 0
  4666.3     .05       0  5132.8     .03       0  5138.8     .05       0
  5497.7     .16       0
#XS Ineff= 2 , 0
                         5061.65          288.85
Permanent Ineff=
       F       F
Bank Sta=4923.7,5055
XS Rating Curve= 0 ,0
Exp/Cntr=0.3,0.1

Type RM Length L Ch R = 1 ,510     ,324,324,324
BEGIN DESCRIPTION:
Mapping XS d408b12f
END DESCRIPTION:
XS GIS Cut Line= 4
      3647830.89     10621683.77      3647668.02     10622078.63
      3647741.81     10622304.33      3648460.11     10622545.21
#Sta/Elev= 30
  4483.4  326.19  4551.1  314.16  4657.6  302.98  4681.5  298.48  4710.9  296.25
  4734.8  292.74    4804  288.25  4935.1  283.26  5003.9  280.56  5006.6  280.06
  5009.9  280.56  5089.2  280.85  5121.1  282.36  5126.3  281.03  5143.2  282.55
  5177.1  281.98  5187.9  283.75  5208.6  282.56  5409.4  282.63  5497.8  285.03
  5578.1  291.77    5692  305.13  5776.5  314.59  5789.1   317.2  5831.2  318.82
  5844.9  322.35  5871.1  324.96    5884  329.03  5894.5  329.55  5905.6  332.25
#Mann= 4 ,-1 , 0
  4483.4     .05       0  5003.9     .03       0  5009.9     .05       0
    5692     .16       0
Bank Sta=4935.1,5187.9
XS Rating Curve= 0 ,0
Exp/Cntr=0.3,0.1

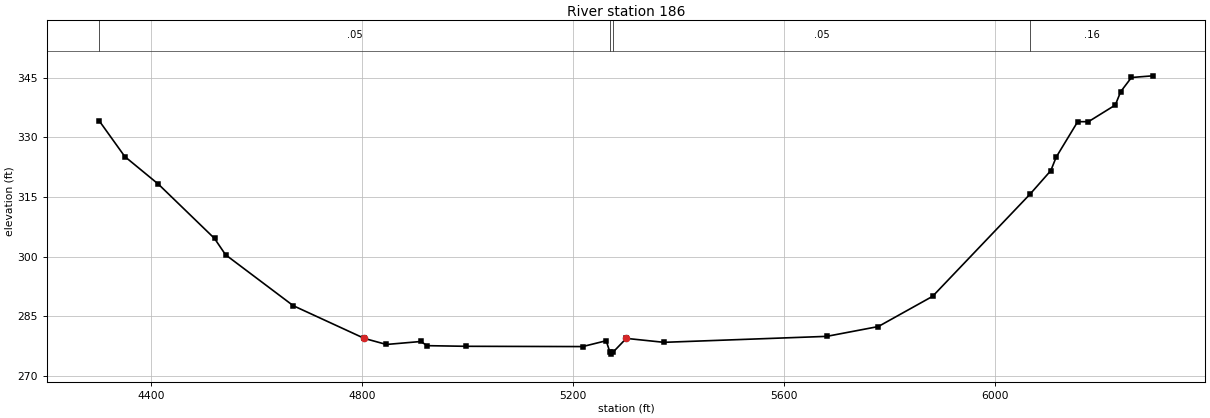
Type RM Length L Ch R = 1 ,186     ,0,0,0
BEGIN DESCRIPTION:
UNT 01873 IN LACR 1.0
END DESCRIPTION:
XS GIS Cut Line= 4
      3647796.18     10621618.66      3647401.19     10622078.76
      3647501.01     10622439.01      3648499.28     10622634.32
#Sta/Elev= 30
  4302.4  334.14  4350.7  325.19  4414.4  318.24  4520.8  304.58  4541.7  300.48
  4670.1  287.66    4805  279.42  4846.7   277.9  4912.1  278.65  4923.7   277.6
  4997.5  277.44  5218.8  277.37  5263.4  278.84  5270.5  275.97  5273.2  275.47
  5276.5  275.97  5301.6  279.43  5372.9  278.44  5681.5  279.94  5779.4  282.41
  5882.4  290.02  6067.2  315.74  6106.5  321.65  6116.7  325.04  6157.5  333.97
  6177.9  333.97  6228.8  338.16    6239  341.52  6259.4  345.09  6299.8  345.51
#Mann= 4 ,-1 , 0
  4302.4     .05       0  5270.5     .03       0  5276.5     .05       0
  6067.2     .16       0
Bank Sta=4805,5301.6
XS Rating Curve= 0 ,0
Exp/Cntr=0.3,0.1

Chan Stop Cuts=-1
Use User Specified Reach Order=0
Composite Channel Slope=5