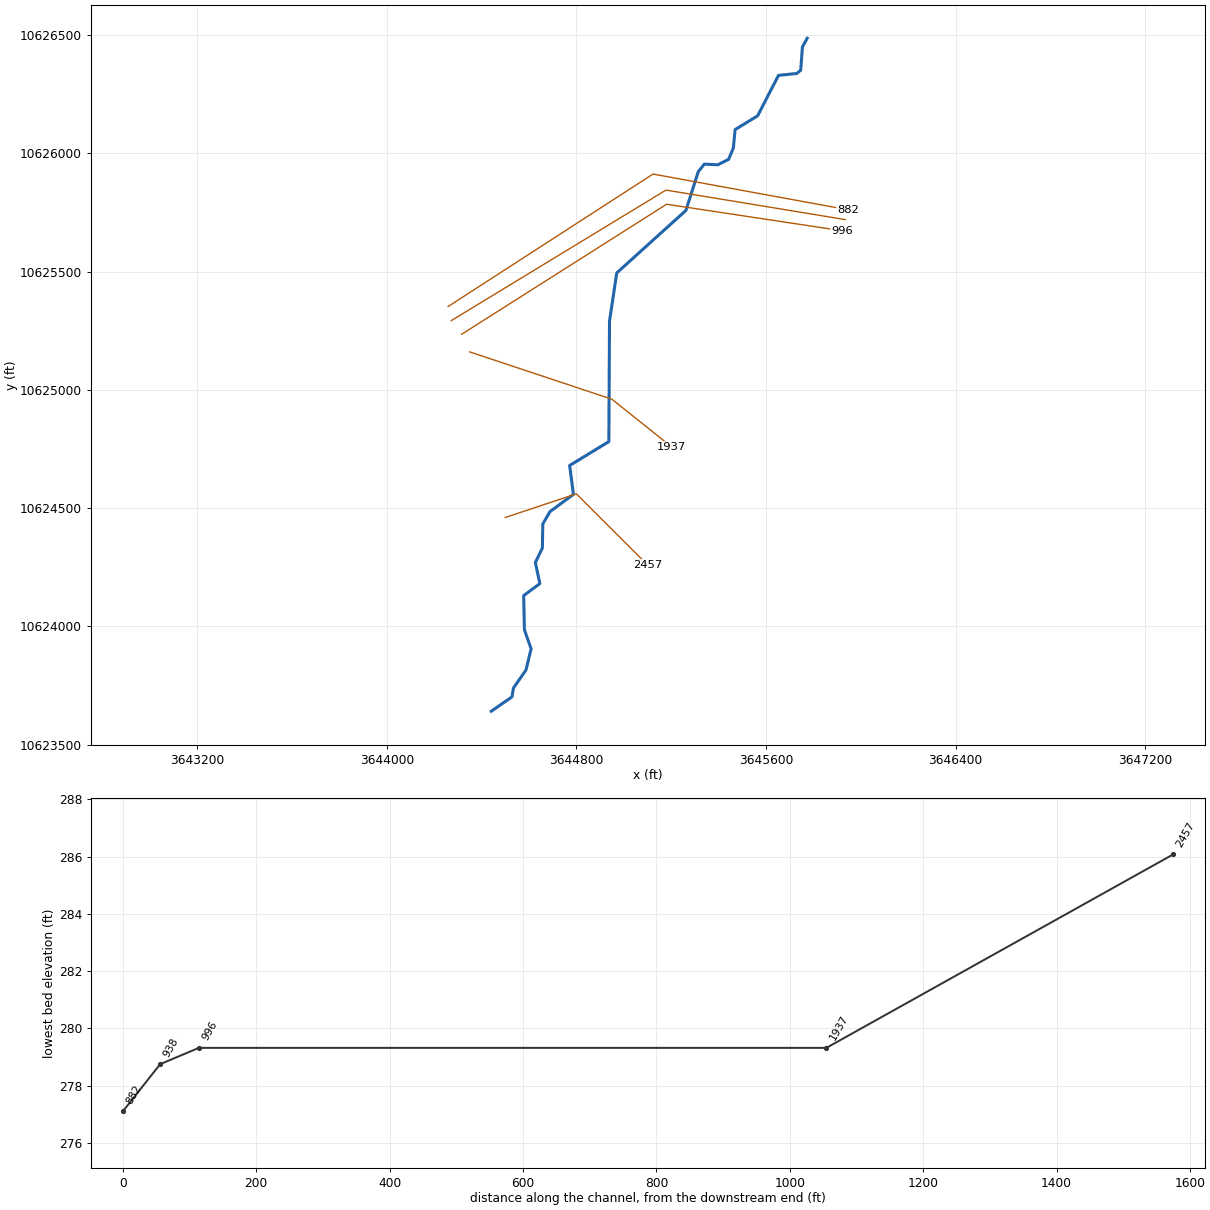
--- UNT 01888 IN LACR.prj (project) ---

Proj Title=UNT 01888 IN LACR Base Level Engineering
Current Plan=p01
Default Exp/Contr=0.3,0.1
English Units
Geom File=g01
Flow File=f01
Plan File=p01
BEGIN DESCRIPTION:
UNT 01888 IN LACR
END DESCRIPTION:

--- UNT 01888 IN LACR.p01 (plan) ---

Plan Title=Multiple Run
Short Identifier=Multiple
Geom File=g01
Flow File=f01
Subcritical Flow
K Sum by GR= 0
Std Step Tol= 0.01
Critical Tol= 0.01
Num of Std Step Trials= 20
Max Error Tol= 0.3
Flow Tol Ratio= 0.001
Split Flow NTrial= 30
Split Flow Tol= 0.02
Split Flow Ratio= 0.02
Log Output Level= 0
Friction Slope Method= 1
Unsteady Friction Slope Method= 2
Unsteady Bridges Friction Slope Method= 1
Parabolic Critical Depth
Global Vel Dist=  1 , 1 , 1
Global Log Level= 0
CheckData=True
Encroach Param= -1, 0, 0, 0
BEGIN DESCRIPTION:
Multiple Run
END DESCRIPTION:

--- UNT 01888 IN LACR.f01 (steady flow) ---

Flow Title=Multiple
Number of Profiles=7
Profile Names=10-year,25-year,50-year,1pct_min,100-year,1pct_plu,500-year
River Rch & RM= UNT 01888 IN LAC,Reach-1,2457
     437     581     697     615     832    1125    1183
Boundary for River Rch & Prof#=UNT 01888 IN LAC,Reach-1,1
Up Type=0
Dn Type=3
Dn Slope=0.005
Boundary for River Rch & Prof#=UNT 01888 IN LAC,Reach-1,2
Up Type=0
Dn Type=3
Dn Slope=0.005
Boundary for River Rch & Prof#=UNT 01888 IN LAC,Reach-1,3
Up Type=0
Dn Type=3
Dn Slope=0.005
Boundary for River Rch & Prof#=UNT 01888 IN LAC,Reach-1,4
Up Type=0
Dn Type=3
Dn Slope=0.005
Boundary for River Rch & Prof#=UNT 01888 IN LAC,Reach-1,5
Up Type=0
Dn Type=3
Dn Slope=0.005
Boundary for River Rch & Prof#=UNT 01888 IN LAC,Reach-1,6
Up Type=0
Dn Type=3
Dn Slope=0.005
Boundary for River Rch & Prof#=UNT 01888 IN LAC,Reach-1,7
Up Type=0
Dn Type=3
Dn Slope=0.005

--- UNT 01888 IN LACR.g01 (geometry) ---

Geom Title=Existing Conditions

River Reach=UNT 01888 IN LAC,Reach-1
Reach XY= 30
      3644440.60     10623641.46      3644528.00     10623702.00
      3644534.00     10623739.00      3644587.25     10623816.00
      3644608.50     10623905.00      3644580.50     10623986.00
      3644577.25     10624130.00      3644645.75     10624181.00
      3644626.50     10624270.00      3644656.25     10624331.00
      3644658.00     10624433.00      3644688.25     10624485.00
      3644787.25     10624558.00      3644771.25     10624680.00
      3644936.75     10624781.00      3644939.50     10625290.00
      3644970.00     10625494.00      3645261.75     10625758.00
      3645314.00     10625922.00      3645339.75     10625954.00
      3645396.25     10625951.00      3645442.00     10625974.00
      3645462.00     10626022.00      3645469.50     10626100.00
      3645564.50     10626158.00      3645652.50     10626329.00
      3645729.50     10626337.00      3645746.25     10626351.00
      3645753.50     10626449.00      3645773.75     10626486.00

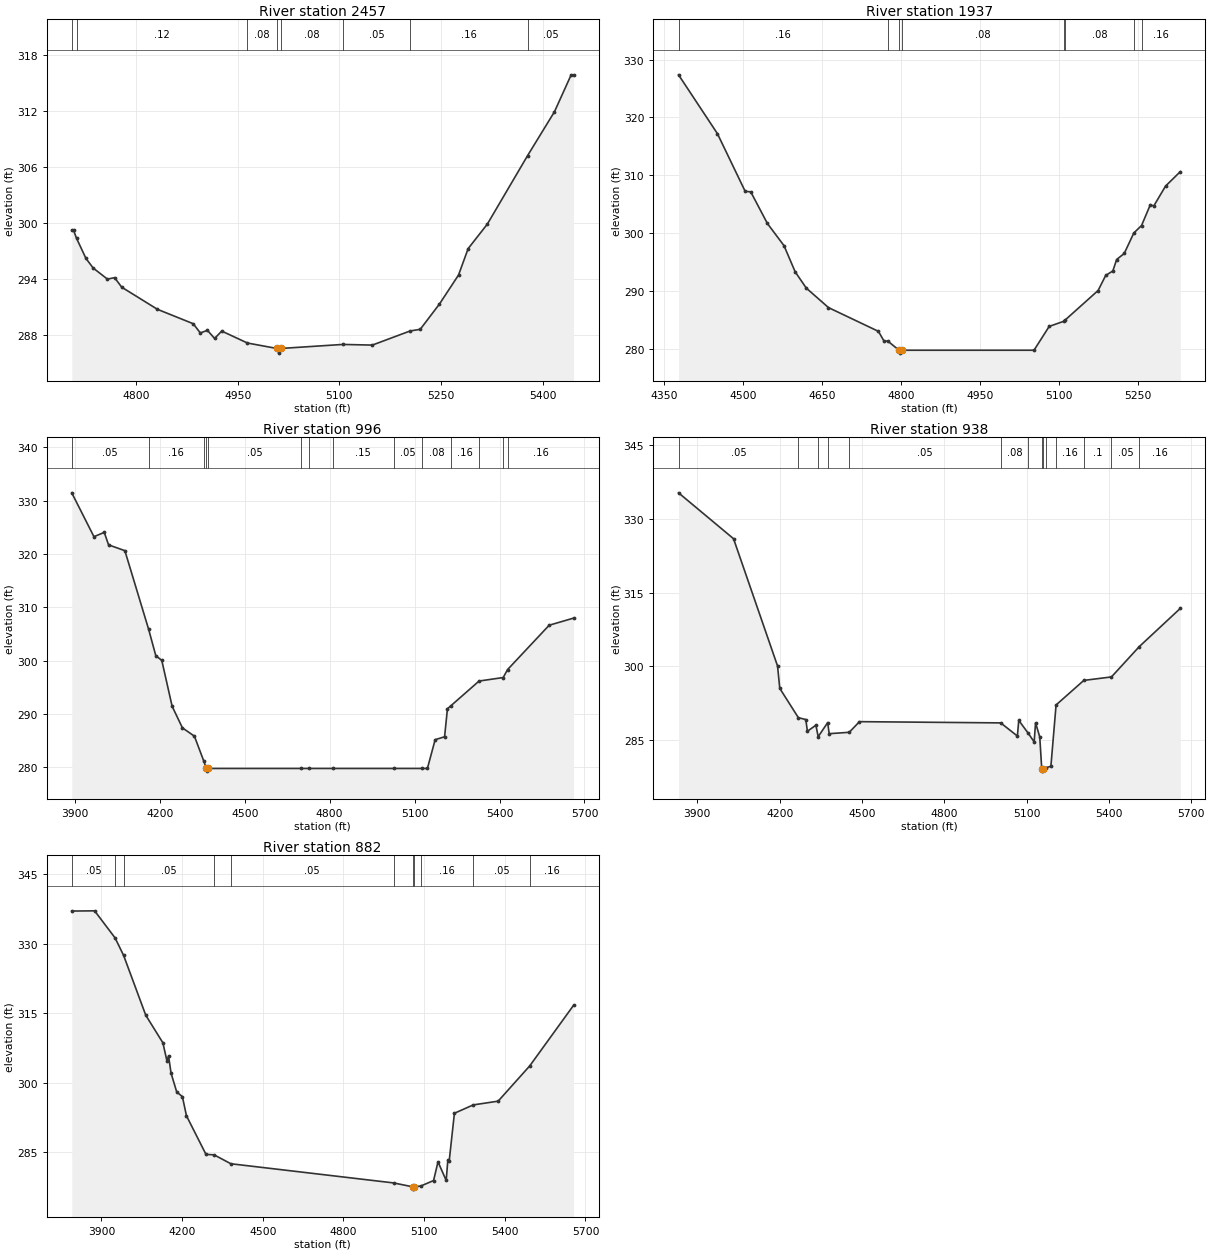
Type RM Length L Ch R = 1,2457,520,520,520
BEGIN DESCRIPTION:
UNT 01888 IN LACR 3.0
END DESCRIPTION:
XS GIS Cut Line= 3
      3644499.65     10624460.20      3644799.61     10624560.19
      3645099.57     10624260.22
#Sta/Elev= 30
  4705.2  299.24  4707.8  299.24  4712.2  298.38  4726.2  296.21  4736.8  295.19
  4757.9  294.00  4768.4  294.16  4778.9  293.14  4831.6  290.77  4884.4  289.23
  4894.9  288.24  4905.4  288.52  4916.0  287.65  4926.5  288.44  4964.5  287.16
  5007.8  286.58  5010.6  286.08  5013.8  286.58  5105.2  287.01  5148.7  286.94
  5204.4  288.45  5219.4  288.63  5247.7  291.33  5275.9  294.44  5290.1  297.27
  5318.4  299.89  5377.7  307.21  5417.4  311.91  5442.1  315.87  5445.6  315.87
#Mann=8,-1,0
  4705.2    0.16       0  4712.2    0.12       0  4964.5    0.08       0
  5007.8    0.07       0  5013.8    0.08       0  5105.2    0.05       0
  5204.4    0.16       0  5377.7    0.05       0
Bank Sta=5007.8,5013.8
Exp/Cntr=0.3,0.1

Type RM Length L Ch R = 1,1937,941,941,941
BEGIN DESCRIPTION:
UNT 01888 IN LACR 2.0
END DESCRIPTION:
XS GIS Cut Line= 3
      3644349.57     10625160.20      3644949.61     10624960.19
      3645199.64     10624760.16
#Sta/Elev= 30
  4377.8  327.36  4451.6  317.21  4504.3  307.25  4514.9  307.16  4546.5  301.70
  4578.1  297.86  4599.2  293.36  4620.3  290.55  4662.5  287.18  4757.3  283.08
  4767.9  281.41  4775.1  281.40  4796.5  279.82  4799.2  279.32  4802.5  279.82
  5052.7  279.82  5081.5  283.93  5109.0  284.81  5111.5  285.01  5174.4  290.13
  5188.8  292.73  5202.4  293.51  5209.6  295.48  5224.0  296.52  5242.2  300.06
  5256.9  301.35  5273.6  304.95  5280.0  304.71  5302.4  308.15  5330.5  310.65
#Mann=8,-1,0
  4377.8    0.16       0  4775.1    0.08       0  4796.5    0.07       0
  4802.5    0.08       0  5109.0     0.1       0  5111.5    0.08       0
  5242.2    0.05       0  5256.9    0.16       0
Bank Sta=4796.5,4802.5
Exp/Cntr=0.3,0.1

Type RM Length L Ch R = 1,996,58,58,58
BEGIN DESCRIPTION:
Mapping XS 6e287c50
END DESCRIPTION:
XS GIS Cut Line= 3
      3644315.81     10625234.84      3645180.38     10625784.31
      3645919.95     10625672.33
#Sta/Elev= 30
  3889.0  331.47  3967.4  323.25  4003.8  324.06  4019.0  321.72  4076.6  320.63
  4160.3  305.94  4185.9  300.95  4207.0  300.07  4243.5  291.48  4279.9  287.43
  4322.2  285.87  4354.8  281.28  4364.5  279.82  4367.2  279.32  4370.5  279.82
  4697.9  279.82  4726.6  279.82  4812.3  279.82  5025.8  279.82  5126.4  279.82
  5145.2  279.82  5172.6  285.21  5205.9  285.76  5216.0  291.01  5227.1  291.52
  5327.7  296.20  5413.0  296.86  5428.4  298.35  5575.3  306.66  5661.4  307.99
#Mann=14,-1,0
  3889.0    0.05       0  4160.3    0.16       0  4354.8    0.05       0
  4364.5    0.07       0  4370.5    0.05       0  4697.9    0.15       0
  4726.6    0.05       0  4812.3    0.15       0  5025.8    0.05       0
  5126.4    0.08       0  5227.1    0.16       0  5327.7     0.1       0
  5413.0    0.05       0  5428.4    0.16       0
Bank Sta=4364.5,4370.5
Exp/Cntr=0.3,0.1

Type RM Length L Ch R = 1,938,56,56,56
BEGIN DESCRIPTION:
Mapping XS 96cecae6
END DESCRIPTION:
XS GIS Cut Line= 3
      3644271.50     10625292.11      3645177.77     10625844.20
      3645935.05     10625719.29
#Sta/Elev= 30
  3831.5  335.23  4031.9  325.92  4192.3  300.09  4200.4  295.55  4268.3  289.59
  4295.3  289.22  4301.1  286.84  4332.1  288.07  4340.4  285.73  4375.0  288.60
  4380.5  286.35  4453.6  286.63  4490.9  288.79  5005.6  288.54  5066.4  285.87
  5071.4  289.05  5106.5  286.39  5127.5  284.68  5132.6  288.55  5147.9  285.69
  5155.1  279.25  5157.8  278.75  5161.1  279.25  5170.9  279.45  5188.5  279.73
  5207.4  292.18  5308.4  297.16  5409.3  297.87  5510.2  304.00  5660.2  311.78
#Mann=14,-1,0
  3831.5    0.05       0  4268.3    0.16       0  4340.4    0.05       0
  4375.0    0.16       0  4453.6    0.05       0  5005.6    0.08       0
  5106.5    0.16       0  5155.1    0.03       0  5161.1    0.16       0
  5170.9    0.08       0  5207.4    0.16       0  5308.4     0.1       0
  5409.3    0.05       0  5510.2    0.16       0
Bank Sta=5155.1,5161.1
Exp/Cntr=0.3,0.1

Type RM Length L Ch R = 1,882,0,0,0
BEGIN DESCRIPTION:
UNT 01888 IN LACR 1.0
END DESCRIPTION:
XS GIS Cut Line= 3
      3644258.53     10625352.03      3645123.08     10625911.91
      3645945.34     10625760.99
#Sta/Elev= 30
  3789.7  337.06  3874.7  337.11  3950.8  331.27  3982.5  327.50  4065.0  314.59
  4128.6  308.65  4143.7  304.74  4149.7  305.83  4158.9  302.12  4180.0  298.06
  4201.1  297.04  4216.3  292.91  4288.8  284.60  4319.1  284.49  4381.5  282.57
  4986.4  278.44  5057.2  277.60  5059.9  277.10  5063.2  277.60  5087.7  277.77
  5135.2  278.95  5151.7  282.98  5182.2  278.97  5188.3  283.41  5193.4  283.22
  5212.7  293.46  5282.7  295.26  5375.4  296.07  5492.9  303.68  5655.7  316.73
#Mann=11,-1,0
  3789.7    0.05       0  3950.8    0.16       0  3982.5    0.05       0
  4319.1    0.16       0  4381.5    0.05       0  4986.4    0.08       0
  5057.2    0.07       0  5063.2    0.08       0  5087.7    0.16       0
  5282.7    0.05       0  5492.9    0.16       0
Bank Sta=5057.2,5063.2
Exp/Cntr=0.3,0.1

Chan Stop Cuts=-1