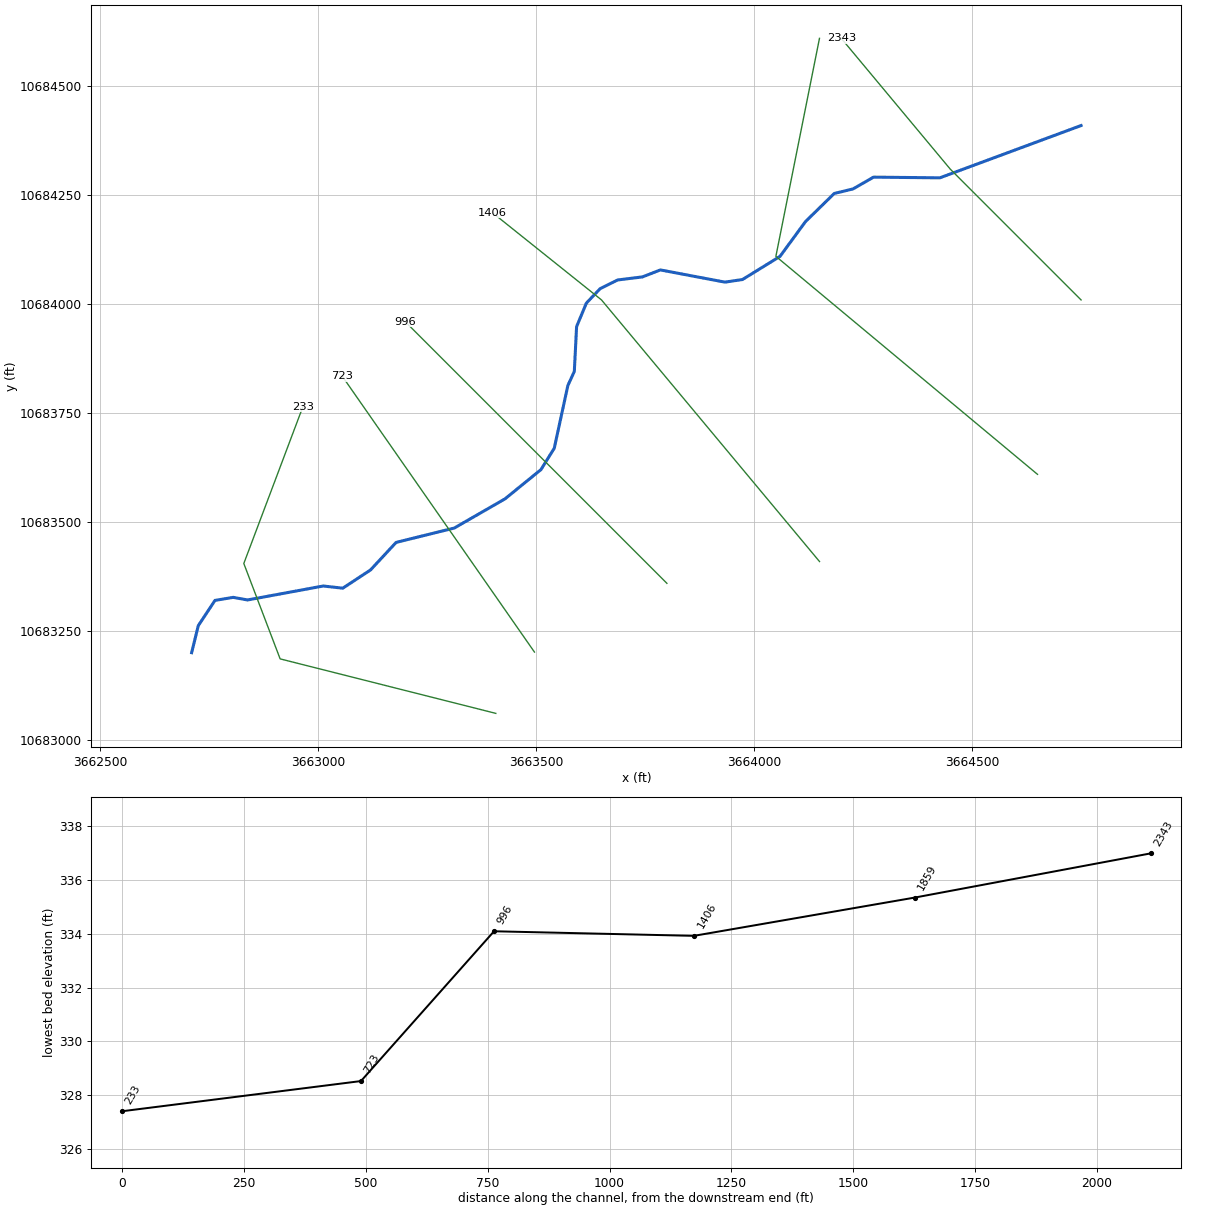
--- UNT 02730 IN LACR.prj (project) ---

Proj Title=UNT 02730 IN LACR Base Level Engineering
Current Plan=p01
Default Exp/Contr=0.3,0.1
English Units
Geom File=g01
Flow File=f01
Plan File=p01
BEGIN DESCRIPTION:
UNT 02730 IN LACR
END DESCRIPTION:

--- UNT 02730 IN LACR.p01 (plan) ---

Plan Title=Multiple Run
Short Identifier=Multiple
Geom File=g01
Flow File=f01
Subcritical Flow
K Sum by GR= 0
Std Step Tol= 0.01
Critical Tol= 0.01
Num of Std Step Trials= 20
Max Error Tol= 0.3
Flow Tol Ratio= 0.001
Split Flow NTrial= 30
Split Flow Tol= 0.02
Split Flow Ratio= 0.02
Log Output Level= 0
Friction Slope Method= 1
Unsteady Friction Slope Method= 2
Unsteady Bridges Friction Slope Method= 1
Parabolic Critical Depth
Global Vel Dist=  1 , 1 , 1
Global Log Level= 0
CheckData=True
Encroach Param= -1, 0, 0, 0
BEGIN DESCRIPTION:
Multiple Run
END DESCRIPTION:

--- UNT 02730 IN LACR.f01 (steady flow) ---

Flow Title=Multiple
Number of Profiles=7
Profile Names=10-year,25-year,50-year,1pct_min,100-year,1pct_plu,500-year
River Rch & RM= UNT 02730 IN LAC,Reach-1,2343
     318     413     489     425     575     778     799
Boundary for River Rch & Prof#=UNT 02730 IN LAC,Reach-1,1
Up Type=0
Dn Type=3
Dn Slope=0.005
Boundary for River Rch & Prof#=UNT 02730 IN LAC,Reach-1,2
Up Type=0
Dn Type=3
Dn Slope=0.005
Boundary for River Rch & Prof#=UNT 02730 IN LAC,Reach-1,3
Up Type=0
Dn Type=3
Dn Slope=0.005
Boundary for River Rch & Prof#=UNT 02730 IN LAC,Reach-1,4
Up Type=0
Dn Type=3
Dn Slope=0.005
Boundary for River Rch & Prof#=UNT 02730 IN LAC,Reach-1,5
Up Type=0
Dn Type=3
Dn Slope=0.005
Boundary for River Rch & Prof#=UNT 02730 IN LAC,Reach-1,6
Up Type=0
Dn Type=3
Dn Slope=0.005
Boundary for River Rch & Prof#=UNT 02730 IN LAC,Reach-1,7
Up Type=0
Dn Type=3
Dn Slope=0.005

--- UNT 02730 IN LACR.g01 (geometry) ---

Geom Title=Existing Conditions

River Reach=UNT 02730 IN LAC,Reach-1
Reach XY= 30
      3664749.61     10684410.19      3664425.63     10684290.23
      3664273.70     10684291.85      3664226.48     10684264.77
      3664183.42     10684254.35      3664117.45     10684189.77
      3664059.00     10684110.00      3663973.00     10684057.00
      3663932.75     10684051.00      3663784.75     10684079.00
      3663743.50     10684063.00      3663686.75     10684056.00
      3663646.50     10684036.00      3663615.00     10684003.00
      3663592.50     10683949.00      3663587.25     10683846.00
      3663572.50     10683814.00      3663541.25     10683670.00
      3663510.75     10683621.00      3663428.50     10683554.00
      3663312.00     10683487.00      3663178.50     10683454.00
      3663120.00     10683391.00      3663056.25     10683349.00
      3663011.25     10683354.00      3662837.75     10683322.00
      3662804.75     10683328.00      3662763.00     10683321.00
      3662724.75     10683263.00      3662709.50     10683201.00

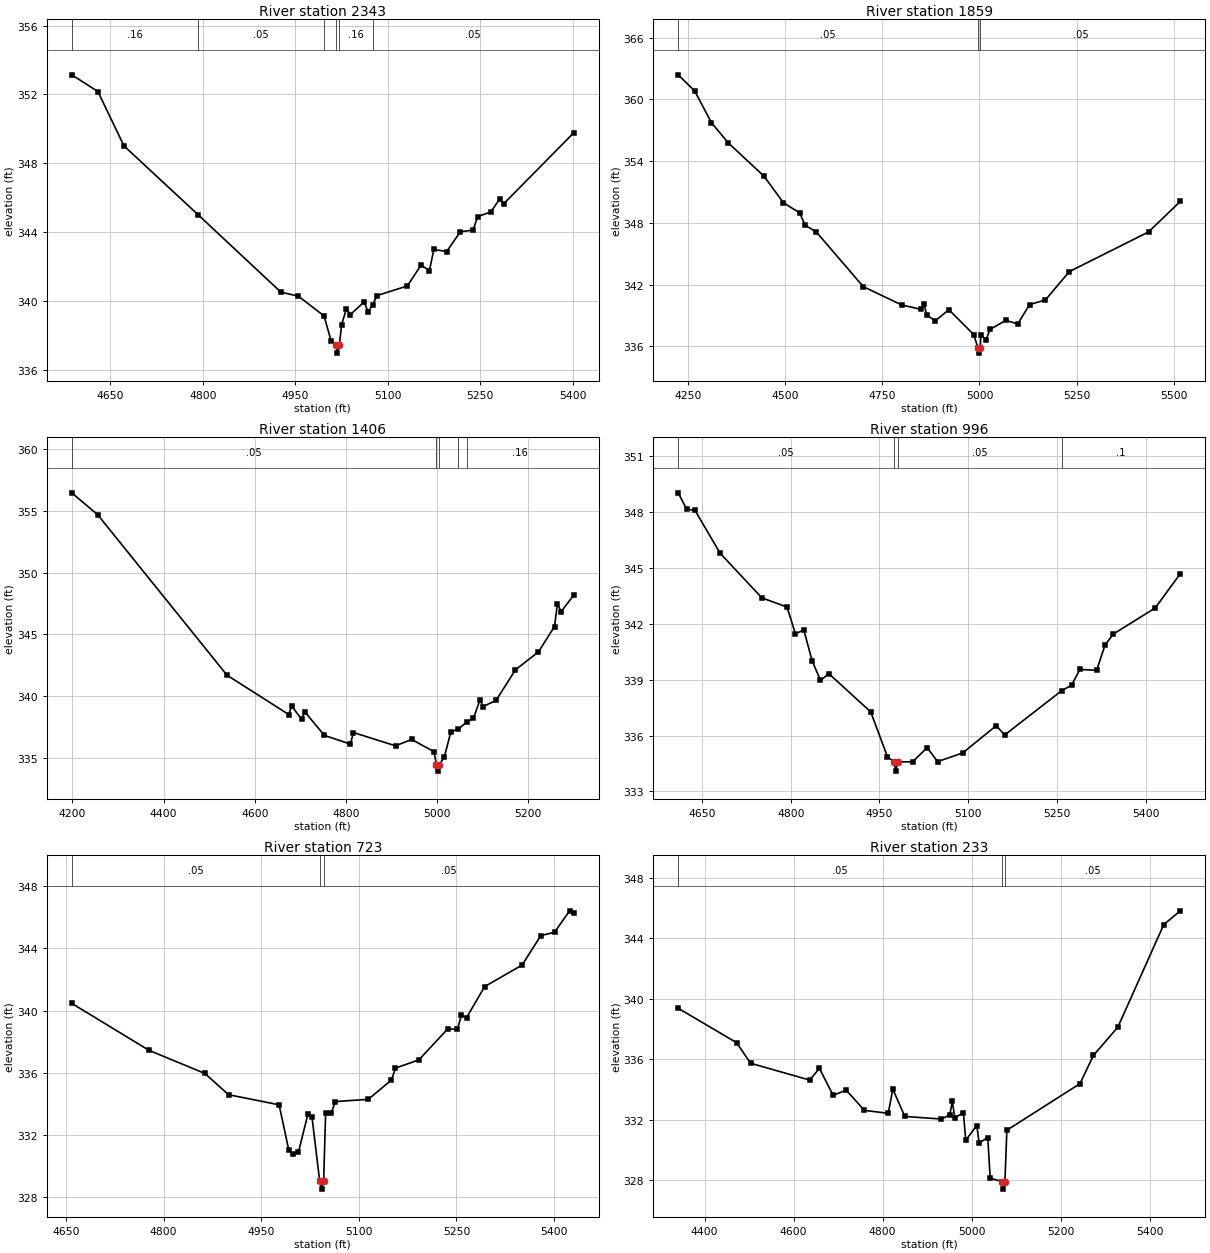
Type RM Length L Ch R = 1,2343,484,484,484
BEGIN DESCRIPTION:
UNT 02730 IN LACR 5.0
END DESCRIPTION:
XS GIS Cut Line= 3
      3664749.59     10684010.21      3664449.61     10684310.19
      3664199.58     10684610.22
#Sta/Elev= 30
  4587.2  353.14  4629.6  352.17  4672.0  349.01  4792.1  345.02  4926.6  340.52
  4954.9  340.29  4996.6  339.14  5007.9  337.71  5015.6  337.48  5018.4  336.98
  5021.6  337.48  5025.1  338.63  5032.9  339.56  5039.4  339.22  5061.6  339.95
  5068.1  339.37  5075.6  339.79  5082.4  340.32  5131.8  340.88  5154.0  342.09
  5167.6  341.77  5174.8  343.00  5195.6  342.88  5217.8  344.03  5238.6  344.12
  5245.7  344.90  5267.2  345.18  5281.5  345.92  5288.1  345.65  5402.0  349.78
#Mann=6,-1,0
  4587.2    0.16       0  4792.1    0.05       0  4996.6    0.16       0
  5015.6    0.07       0  5021.6    0.16       0  5075.6    0.05       0
Bank Sta=5015.6,5021.6
Exp/Cntr=0.3,0.1

Type RM Length L Ch R = 1,1859,453,453,453
BEGIN DESCRIPTION:
UNT 02730 IN LACR 4.0
END DESCRIPTION:
XS GIS Cut Line= 3
      3664649.65     10683610.16      3664049.61     10684110.19
      3664149.61     10684610.21
#Sta/Elev= 30
  4225.4  362.39  4267.8  360.82  4310.7  357.74  4353.7  355.79  4446.1  352.53
  4495.6  349.97  4537.9  348.96  4551.5  347.77  4580.2  347.13  4701.2  341.80
  4800.2  340.02  4850.3  339.59  4857.4  340.15  4863.9  339.07  4886.1  338.47
  4921.2  339.56  4985.0  337.15  4996.3  335.84  4999.1  335.34  5002.3  335.84
  5003.2  337.15  5016.7  336.60  5026.9  337.64  5067.7  338.52  5098.3  338.18
  5128.9  340.06  5169.6  340.51  5230.8  343.26  5434.8  347.12  5516.4  350.09
#Mann=3,-1,0
  4225.4    0.05       0  4996.3    0.03       0  5002.3    0.05       0
Bank Sta=4996.3,5002.3
Exp/Cntr=0.3,0.1

Type RM Length L Ch R = 1,1406,410,410,410
BEGIN DESCRIPTION:
UNT 02730 IN LACR 3.0
END DESCRIPTION:
XS GIS Cut Line= 3
      3664149.63     10683410.17      3663649.61     10684010.19
      3663399.62     10684210.18
#Sta/Elev= 30
  4198.8  356.48  4255.5  354.71  4539.2  341.70  4674.6  338.51  4681.1  339.20
  4703.2  338.11  4709.7  338.74  4752.7  336.82  4810.0  336.11  4816.5  337.05
  4908.9  335.97  4944.1  336.49  4993.5  335.49  4998.5  334.42  5001.2  333.92
  5004.5  334.42  5015.9  335.06  5030.3  337.11  5046.8  337.33  5065.1  337.90
  5079.9  338.21  5094.3  339.72  5100.7  339.15  5129.5  339.66  5171.9  342.13
  5222.4  343.59  5257.6  345.64  5264.0  347.50  5272.0  346.85  5300.0  348.19
#Mann=5,-1,0
  4198.8    0.05       0  4998.5    0.03       0  5004.5    0.05       0
  5046.8     0.1       0  5065.1    0.16       0
Bank Sta=4998.5,5004.5
Exp/Cntr=0.3,0.1

Type RM Length L Ch R = 1,996,273,273,273
BEGIN DESCRIPTION:
UNT 02730 IN LACR 2.0
END DESCRIPTION:
XS GIS Cut Line= 3
      3663799.62     10683360.18      3663499.61     10683660.19
      3663199.64     10683960.16
#Sta/Elev= 30
  4609.9  349.03  4624.1  348.15  4638.2  348.09  4680.6  345.79  4751.3  343.39
  4793.8  342.90  4807.9  341.46  4822.1  341.67  4836.2  340.01  4850.3  338.96
  4864.5  339.32  4935.2  337.27  4963.5  334.86  4974.6  334.59  4977.4  334.09
  4980.6  334.59  5005.9  334.59  5030.6  335.35  5048.3  334.60  5090.8  335.07
  5147.3  336.53  5161.5  336.03  5258.0  338.41  5274.6  338.70  5288.7  339.55
  5317.0  339.50  5331.2  340.86  5345.3  341.45  5416.0  342.85  5458.4  344.69
#Mann=4,-1,0
  4609.9    0.05       0  4974.6    0.03       0  4980.6    0.05       0
  5258.0     0.1       0
Bank Sta=4974.6,4980.6
Exp/Cntr=0.3,0.1

Type RM Length L Ch R = 1,723,490,490,490
BEGIN DESCRIPTION:
Mapping XS 4c5d19c7
END DESCRIPTION:
XS GIS Cut Line= 2
      3663495.82     10683202.51      3663054.78     10683835.52
#Sta/Elev= 30
  4658.9  340.47  4777.7  337.45  4863.3  335.97  4899.8  334.60  4977.5  333.95
  4992.3  331.05  4998.4  330.82  5007.2  330.91  5021.7  333.34  5028.1  333.14
  5039.9  329.03  5042.7  328.53  5045.9  329.03  5049.0  333.41  5057.8  333.44
  5063.9  334.16  5114.5  334.30  5150.2  335.55  5156.3  336.31  5192.3  336.84
  5236.6  338.83  5251.5  338.80  5257.6  339.71  5265.5  339.55  5293.3  341.55
  5350.8  342.93  5379.7  344.83  5400.7  345.04  5423.9  346.42  5430.4  346.28
#Mann=3,-1,0
  4658.9    0.05       0  5039.9    0.03       0  5045.9    0.05       0
Bank Sta=5039.9,5045.9
Exp/Cntr=0.3,0.1

Type RM Length L Ch R = 1,233,0,0,0
BEGIN DESCRIPTION:
UNT 02730 IN LACR 1.0
END DESCRIPTION:
XS GIS Cut Line= 4
      3663407.25     10683061.87      3662912.49     10683186.87
      3662829.16     10683405.62      3662964.57     10683764.96
#Sta/Elev= 30
  4340.8  339.38  4472.1  337.10  4503.4  335.74  4636.2  334.63  4658.1  335.40
  4689.0  333.62  4718.3  333.96  4759.3  332.62  4812.8  332.43  4823.1  334.03
  4850.0  332.22  4932.2  332.05  4951.0  332.32  4956.9  333.21  4962.3  332.15
  4981.7  332.45  4987.0  330.65  5011.8  331.62  5017.1  330.47  5036.5  330.82
  5041.9  328.13  5069.0  327.91  5071.7  327.41  5075.0  327.91  5079.4  331.31
  5243.7  334.39  5273.9  336.26  5329.0  338.14  5432.0  344.92  5469.2  345.83
#Mann=3,-1,0
  4340.8    0.05       0  5069.0    0.03       0  5075.0    0.05       0
Bank Sta=5069,5075
Exp/Cntr=0.3,0.1

Chan Stop Cuts=-1