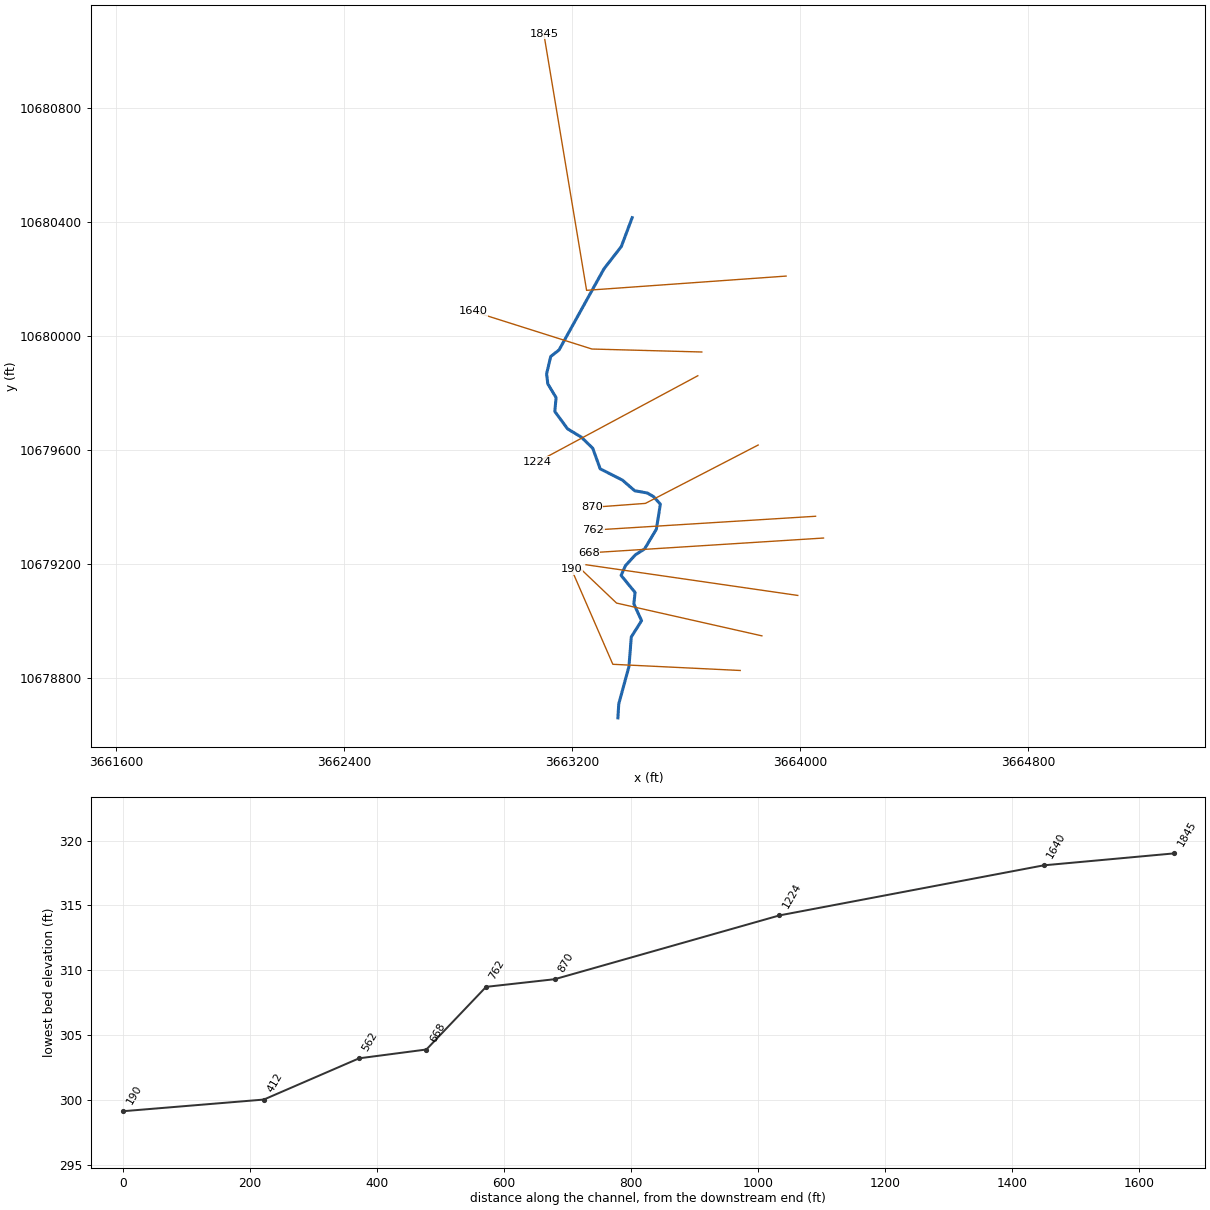
--- UNT 02733 IN LACR.prj (project) ---

Proj Title=UNT 02733 IN LACR Base Level Engineering
Current Plan=p01
Default Exp/Contr=0.3,0.1
English Units
Geom File=g01
Flow File=f01
Plan File=p01
BEGIN DESCRIPTION:
UNT 02733 IN LACR
END DESCRIPTION:

--- UNT 02733 IN LACR.p01 (plan) ---

Plan Title=Multiple Run
Short Identifier=Multiple
Geom File=g01
Flow File=f01
Subcritical Flow
K Sum by GR= 0
Std Step Tol= 0.01
Critical Tol= 0.01
Num of Std Step Trials= 20
Max Error Tol= 0.3
Flow Tol Ratio= 0.001
Split Flow NTrial= 30
Split Flow Tol= 0.02
Split Flow Ratio= 0.02
Log Output Level= 0
Friction Slope Method= 1
Unsteady Friction Slope Method= 2
Unsteady Bridges Friction Slope Method= 1
Parabolic Critical Depth
Global Vel Dist=  1 , 1 , 1
Global Log Level= 0
CheckData=True
Encroach Param= -1, 0, 0, 0
BEGIN DESCRIPTION:
Multiple Run
END DESCRIPTION:

--- UNT 02733 IN LACR.f01 (steady flow) ---

Flow Title=Multiple
Number of Profiles=7
Profile Names=10-year,25-year,50-year,1pct_min,100-year,1pct_plu,500-year
River Rch & RM= UNT 02733 IN LAC,Reach-1,1845
     187     237     275     236     319     432     431
Boundary for River Rch & Prof#=UNT 02733 IN LAC,Reach-1,1
Up Type=0
Dn Type=3
Dn Slope=0.005
Boundary for River Rch & Prof#=UNT 02733 IN LAC,Reach-1,2
Up Type=0
Dn Type=3
Dn Slope=0.005
Boundary for River Rch & Prof#=UNT 02733 IN LAC,Reach-1,3
Up Type=0
Dn Type=3
Dn Slope=0.005
Boundary for River Rch & Prof#=UNT 02733 IN LAC,Reach-1,4
Up Type=0
Dn Type=3
Dn Slope=0.005
Boundary for River Rch & Prof#=UNT 02733 IN LAC,Reach-1,5
Up Type=0
Dn Type=3
Dn Slope=0.005
Boundary for River Rch & Prof#=UNT 02733 IN LAC,Reach-1,6
Up Type=0
Dn Type=3
Dn Slope=0.005
Boundary for River Rch & Prof#=UNT 02733 IN LAC,Reach-1,7
Up Type=0
Dn Type=3
Dn Slope=0.005

--- UNT 02733 IN LACR.g01 (geometry) ---

Geom Title=Existing Conditions

River Reach=UNT 02733 IN LAC,Reach-1
Reach XY= 30
      3663409.50     10680415.00      3663371.50     10680314.00
      3663310.25     10680235.00      3663153.00     10679951.00
      3663123.75     10679928.00      3663109.25     10679867.00
      3663113.50     10679832.00      3663142.50     10679784.00
      3663138.25     10679735.00      3663183.00     10679674.00
      3663231.25     10679645.00      3663271.25     10679606.00
      3663297.25     10679534.00      3663375.75     10679494.00
      3663418.25     10679457.00      3663462.75     10679449.00
      3663483.75     10679437.00      3663508.50     10679410.00
      3663494.50     10679322.00      3663453.25     10679253.00
      3663420.75     10679232.00      3663386.00     10679194.00
      3663370.75     10679160.00      3663419.75     10679100.00
      3663415.50     10679060.00      3663442.50     10679001.00
      3663406.50     10678944.00      3663398.25     10678840.00
      3663362.50     10678709.00      3663359.50     10678660.00

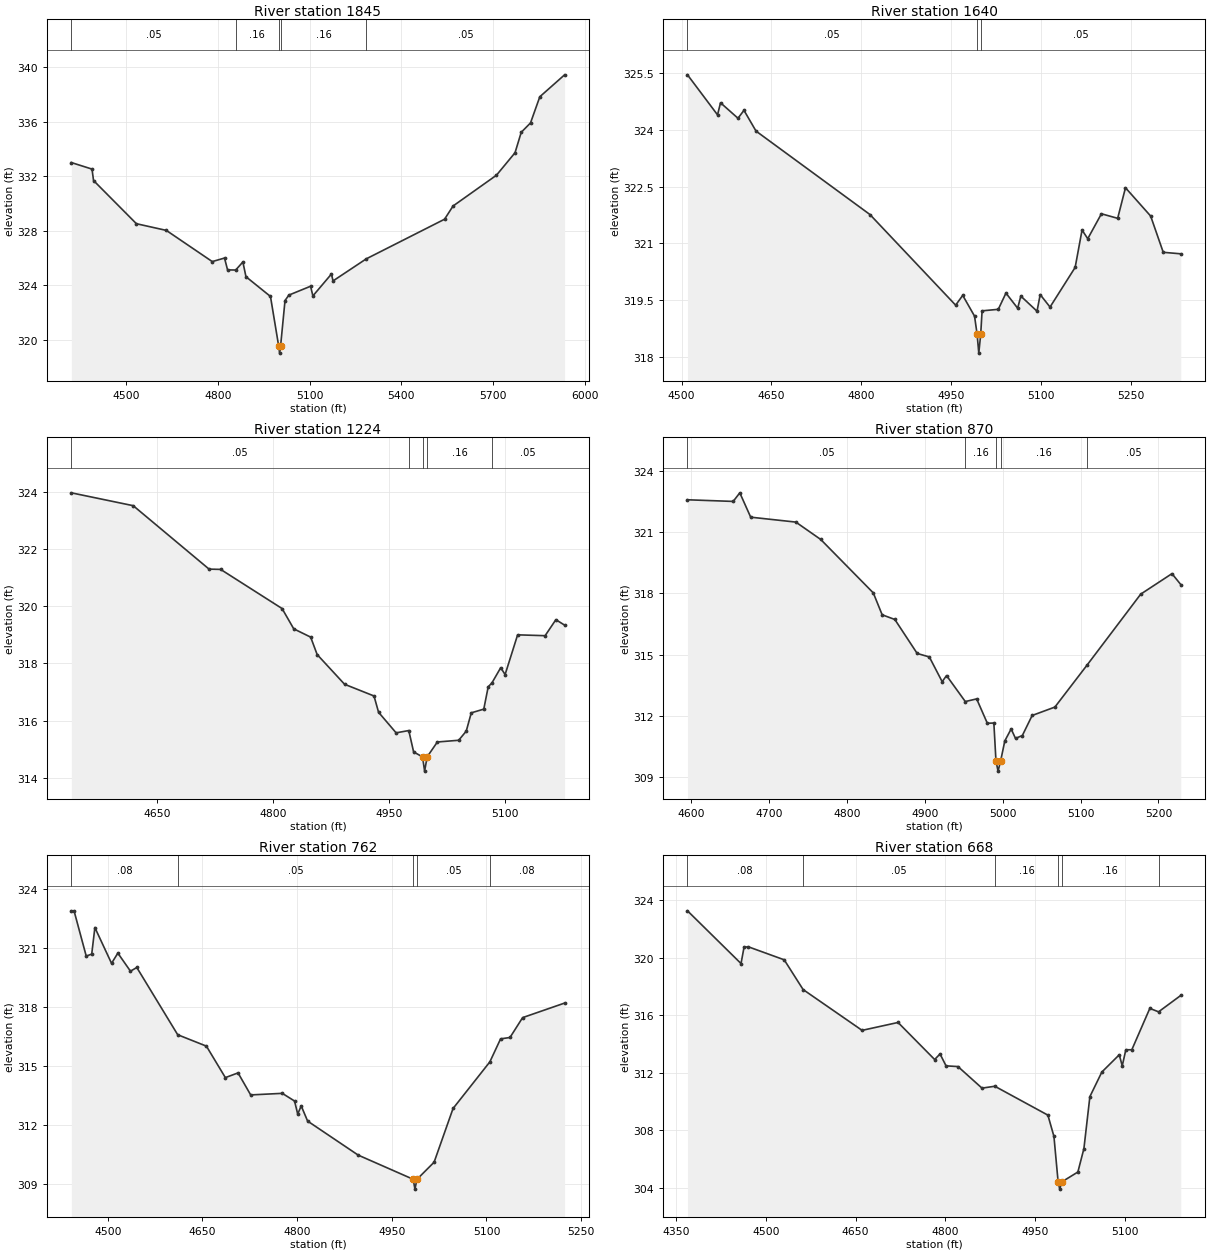
Type RM Length L Ch R = 1,1845,205,205,205
BEGIN DESCRIPTION:
UNT 02733 IN LACR 2.0
END DESCRIPTION:
XS GIS Cut Line= 3
      3663949.62     10680210.19      3663249.61     10680160.19
      3663099.61     10681060.18
#Sta/Elev= 30
  4319.8  333.00  4387.5  332.52  4392.5  331.68  4532.8  328.51  4630.6  328.02
  4781.0  325.73  4821.1  325.99  4831.1  325.12  4857.6  325.11  4881.2  325.70
  4891.3  324.62  4971.5  323.17  4998.5  319.51  5001.3  319.01  5004.5  319.51
  5019.1  322.87  5031.7  323.27  5102.7  323.92  5110.3  323.21  5171.1  324.82
  5176.2  324.31  5284.9  325.93  5541.2  328.84  5569.0  329.81  5711.0  332.07
  5771.8  333.72  5792.1  335.22  5822.5  335.91  5852.9  337.83  5934.0  339.44
#Mann=5,-1,0
  4319.8    0.05       0  4857.6    0.16       0  4998.5    0.07       0
  5004.5    0.16       0  5284.9    0.05       0
Bank Sta=4998.5,5004.5
Exp/Cntr=0.3,0.1

Type RM Length L Ch R = 1,1640,416,416,416
BEGIN DESCRIPTION:
Mapping XS cbf6909a
END DESCRIPTION:
XS GIS Cut Line= 3
      3663653.82     10679943.81      3663268.40     10679954.23
      3662851.75     10680086.16
#Sta/Elev= 30
  4509.9  325.46  4560.0  324.40  4565.0  324.72  4594.1  324.31  4604.1  324.52
  4624.2  323.97  4814.2  321.76  4957.1  319.36  4968.9  319.62  4988.6  319.07
  4992.9  318.59  4995.7  318.09  4998.9  318.59  5001.2  319.21  5028.2  319.25
  5041.0  319.68  5060.5  319.28  5065.8  319.60  5092.8  319.20  5098.1  319.64
  5114.5  319.31  5156.4  320.36  5167.9  321.35  5177.4  321.12  5200.2  321.78
  5227.3  321.66  5240.3  322.47  5282.3  321.72  5303.3  320.76  5332.5  320.72
#Mann=3,-1,0
  4509.9    0.05       0  4992.9    0.03       0  4998.9    0.05       0
Bank Sta=4992.9,4998.9
Exp/Cntr=0.3,0.1

Type RM Length L Ch R = 1,1224,354,354,354
BEGIN DESCRIPTION:
Mapping XS ab490310
END DESCRIPTION:
XS GIS Cut Line= 2
      3663639.94     10679860.49      3663077.43     10679558.40
#Sta/Elev= 30
  4539.1  323.97  4619.2  323.52  4717.4  321.30  4732.4  321.29  4811.9  319.92
  4827.0  319.21  4848.9  318.92  4857.3  318.31  4892.8  317.27  4930.9  316.86
  4936.8  316.29  4959.5  315.57  4975.9  315.65  4982.2  314.90  4993.7  314.73
  4996.4  314.23  4999.7  314.73  5012.9  315.25  5040.5  315.31  5050.3  315.63
  5056.8  316.27  5073.0  316.40  5078.7  317.18  5083.6  317.32  5094.9  317.85
  5100.6  317.61  5116.8  319.00  5152.4  318.97  5166.3  319.53  5177.6  319.34
#Mann=5,-1,0
  4539.1    0.05       0  4975.9    0.16       0  4993.7    0.07       0
  4999.7    0.16       0  5083.6    0.05       0
Bank Sta=4993.7,4999.7
Exp/Cntr=0.3,0.1

Type RM Length L Ch R = 1,870,108,108,108
BEGIN DESCRIPTION:
Mapping XS e247256d
END DESCRIPTION:
XS GIS Cut Line= 3
      3663851.70     10679617.40      3663455.90     10679412.56
      3663268.38     10679398.67
#Sta/Elev= 30
  4595.0  322.57  4653.7  322.49  4662.2  322.91  4676.2  321.72  4734.2  321.48
  4766.2  320.63  4833.7  318.02  4845.1  316.95  4861.4  316.72  4890.1  315.06
  4905.7  314.89  4922.2  313.68  4927.8  313.98  4951.9  312.71  4966.5  312.84
  4980.2  311.65  4988.6  311.66  4991.3  309.81  4994.0  309.31  4997.3  309.81
  5002.7  310.79  5010.8  311.37  5016.4  310.91  5025.2  311.05  5037.8  312.03
  5067.0  312.44  5108.5  314.50  5177.3  317.96  5217.4  318.96  5228.7  318.43
#Mann=5,-1,0
  4595.0    0.05       0  4951.9    0.16       0  4991.3    0.07       0
  4997.3    0.16       0  5108.5    0.05       0
Bank Sta=4991.3,4997.3
Exp/Cntr=0.3,0.1

Type RM Length L Ch R = 1,762,94,94,94
BEGIN DESCRIPTION:
Mapping XS 277d37d4
END DESCRIPTION:
XS GIS Cut Line= 2
      3664053.15     10679367.42      3663273.26     10679318.90
#Sta/Elev= 30
  4442.4  322.87  4446.7  322.87  4466.0  320.57  4474.7  320.67  4479.7  322.02
  4506.1  320.20  4516.1  320.72  4536.1  319.80  4546.1  319.99  4610.9  316.57
  4656.4  315.99  4686.4  314.39  4706.5  314.63  4726.5  313.51  4776.6  313.59
  4796.0  313.20  4801.0  312.54  4806.6  312.95  4816.7  312.18  4896.8  310.45
  4984.0  309.22  4986.7  308.72  4990.0  309.22  5017.1  310.09  5047.1  312.82
  5105.4  315.19  5122.4  316.36  5137.3  316.43  5157.3  317.44  5223.8  318.18
#Mann=5,-1,0
  4442.4    0.08       0  4610.9    0.05       0  4984.0    0.04       0
  4990.0    0.05       0  5105.4    0.08       0
Bank Sta=4984,4990
Exp/Cntr=0.3,0.1

Type RM Length L Ch R = 1,668,106,106,106
BEGIN DESCRIPTION:
Mapping XS 9ff6c7cf
END DESCRIPTION:
XS GIS Cut Line= 2
      3664080.94     10679291.03      3663257.98     10679238.95
#Sta/Elev= 30
  4369.1  323.26  4458.6  319.59  4463.6  320.72  4470.6  320.76  4530.8  319.85
  4562.4  317.78  4661.0  314.94  4721.1  315.49  4782.3  312.91  4791.3  313.30
  4801.3  312.47  4821.3  312.42  4861.4  310.92  4882.9  311.05  4971.6  309.04
  4981.7  307.56  4988.7  304.39  4991.4  303.89  4994.7  304.39  5021.7  305.08
  5031.8  306.71  5041.8  310.33  5061.8  312.04  5090.9  313.24  5095.9  312.47
  5101.9  313.59  5111.9  313.59  5142.0  316.47  5156.6  316.23  5193.7  317.37
#Mann=6,-1,0
  4369.1    0.08       0  4562.4    0.05       0  4882.9    0.16       0
  4988.7    0.07       0  4994.7    0.16       0  5156.6    0.05       0
Bank Sta=4988.7,4994.7
Exp/Cntr=0.3,0.1

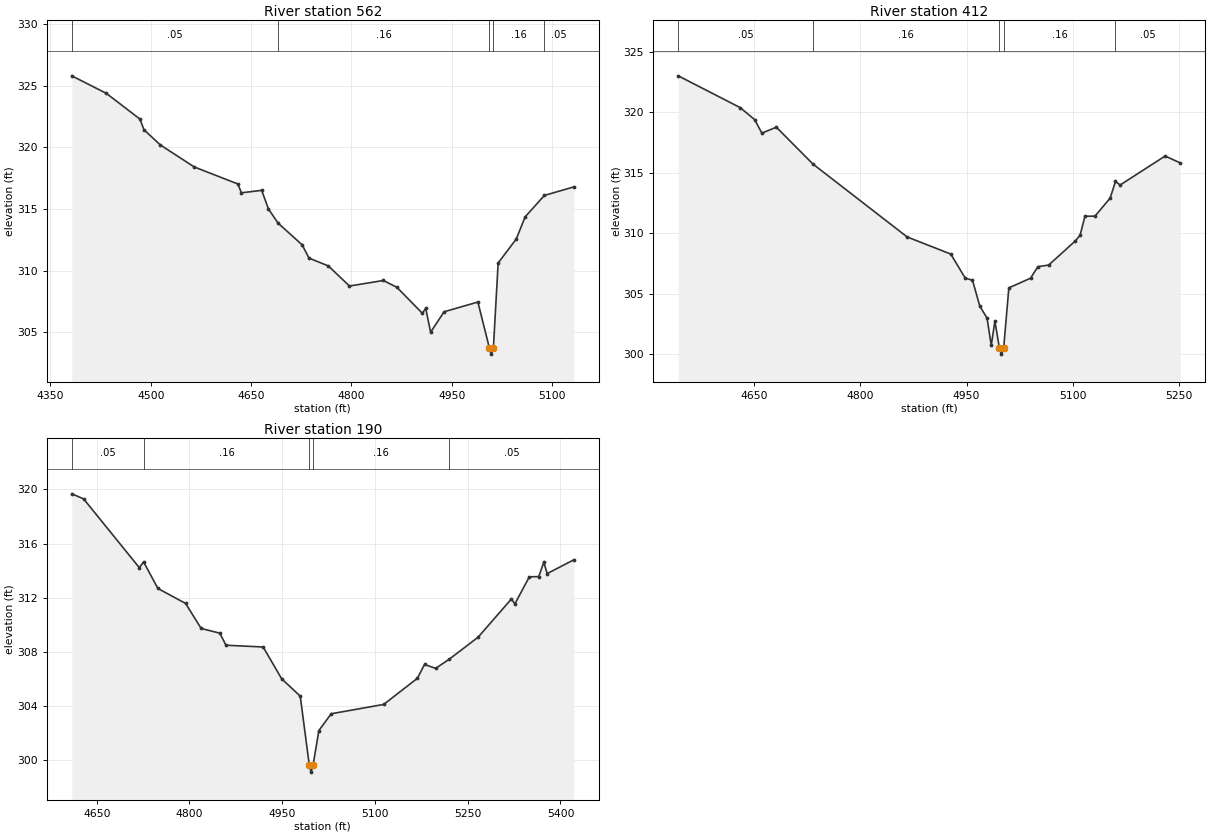
Type RM Length L Ch R = 1,562,150,150,150
BEGIN DESCRIPTION:
Mapping XS 97346e8d
END DESCRIPTION:
XS GIS Cut Line= 2
      3663990.65     10679089.64      3663247.61     10679197.28
#Sta/Elev= 30
  4381.9  325.81  4433.5  324.39  4484.0  322.29  4489.7  321.44  4514.3  320.20
  4565.0  318.41  4630.2  317.03  4635.6  316.31  4665.9  316.51  4676.0  315.00
  4690.4  313.85  4726.5  312.08  4736.6  311.01  4765.6  310.37  4797.2  308.74
  4847.8  309.19  4868.0  308.64  4906.1  306.53  4911.2  306.93  4918.5  304.99
  4938.7  306.65  4989.2  307.44  5006.4  303.71  5009.2  303.21  5012.4  303.71
  5019.5  310.61  5046.6  312.56  5059.9  314.36  5088.7  316.10  5132.7  316.79
#Mann=5,-1,0
  4381.9    0.05       0  4690.4    0.16       0  5006.4    0.07       0
  5012.4    0.16       0  5088.7    0.05       0
Bank Sta=5006.4,5012.4
Exp/Cntr=0.3,0.1

Type RM Length L Ch R = 1,412,222,222,222
BEGIN DESCRIPTION:
Mapping XS 889c6ee8
END DESCRIPTION:
XS GIS Cut Line= 3
      3663864.75     10678947.80      3663354.73     10679062.83
      3663220.16     10679190.89
#Sta/Elev= 30
  4543.1  323.00  4630.4  320.38  4650.9  319.39  4661.1  318.27  4681.6  318.76
  4733.2  315.72  4866.2  309.70  4927.7  308.29  4948.2  306.30  4958.4  306.13
  4968.7  303.99  4978.9  303.01  4984.9  300.75  4990.0  302.75  4996.4  300.53
  4999.2  300.03  5002.4  300.53  5009.7  305.50  5040.4  306.30  5050.7  307.25
  5065.9  307.38  5102.9  309.34  5110.2  309.83  5117.1  311.41  5131.3  311.42
  5152.7  312.91  5160.2  314.28  5166.8  313.99  5230.3  316.38  5251.7  315.81
#Mann=5,-1,0
  4543.1    0.05       0  4733.2    0.16       0  4996.4    0.07       0
  5002.4    0.16       0  5160.2    0.05       0
Bank Sta=4996.4,5002.4
Exp/Cntr=0.3,0.1

Type RM Length L Ch R = 1,190,0,0,0
BEGIN DESCRIPTION:
UNT 02733 IN LACR 1.0
END DESCRIPTION:
XS GIS Cut Line= 3
      3663788.71     10678826.28      3663341.71     10678847.98
      3663196.30     10679182.19
#Sta/Elev= 30
  4609.6  319.68  4628.7  319.31  4718.8  314.23  4725.8  314.65  4748.9  312.69
  4793.6  311.59  4818.9  309.74  4849.0  309.39  4859.0  308.50  4919.1  308.37
  4949.1  306.02  4979.1  304.74  4993.8  299.63  4996.6  299.13  4999.8  299.63
  5009.2  302.20  5029.2  303.44  5114.1  304.13  5168.6  306.06  5180.1  307.08
  5198.1  306.79  5220.4  307.48  5266.7  309.09  5320.7  311.92  5326.2  311.55
  5349.6  313.55  5364.9  313.57  5373.0  314.63  5378.5  313.79  5421.6  314.81
#Mann=5,-1,0
  4609.6    0.05       0  4725.8    0.16       0  4993.8    0.07       0
  4999.8    0.16       0  5220.4    0.05       0
Bank Sta=4993.8,4999.8
Exp/Cntr=0.3,0.1

Chan Stop Cuts=-1