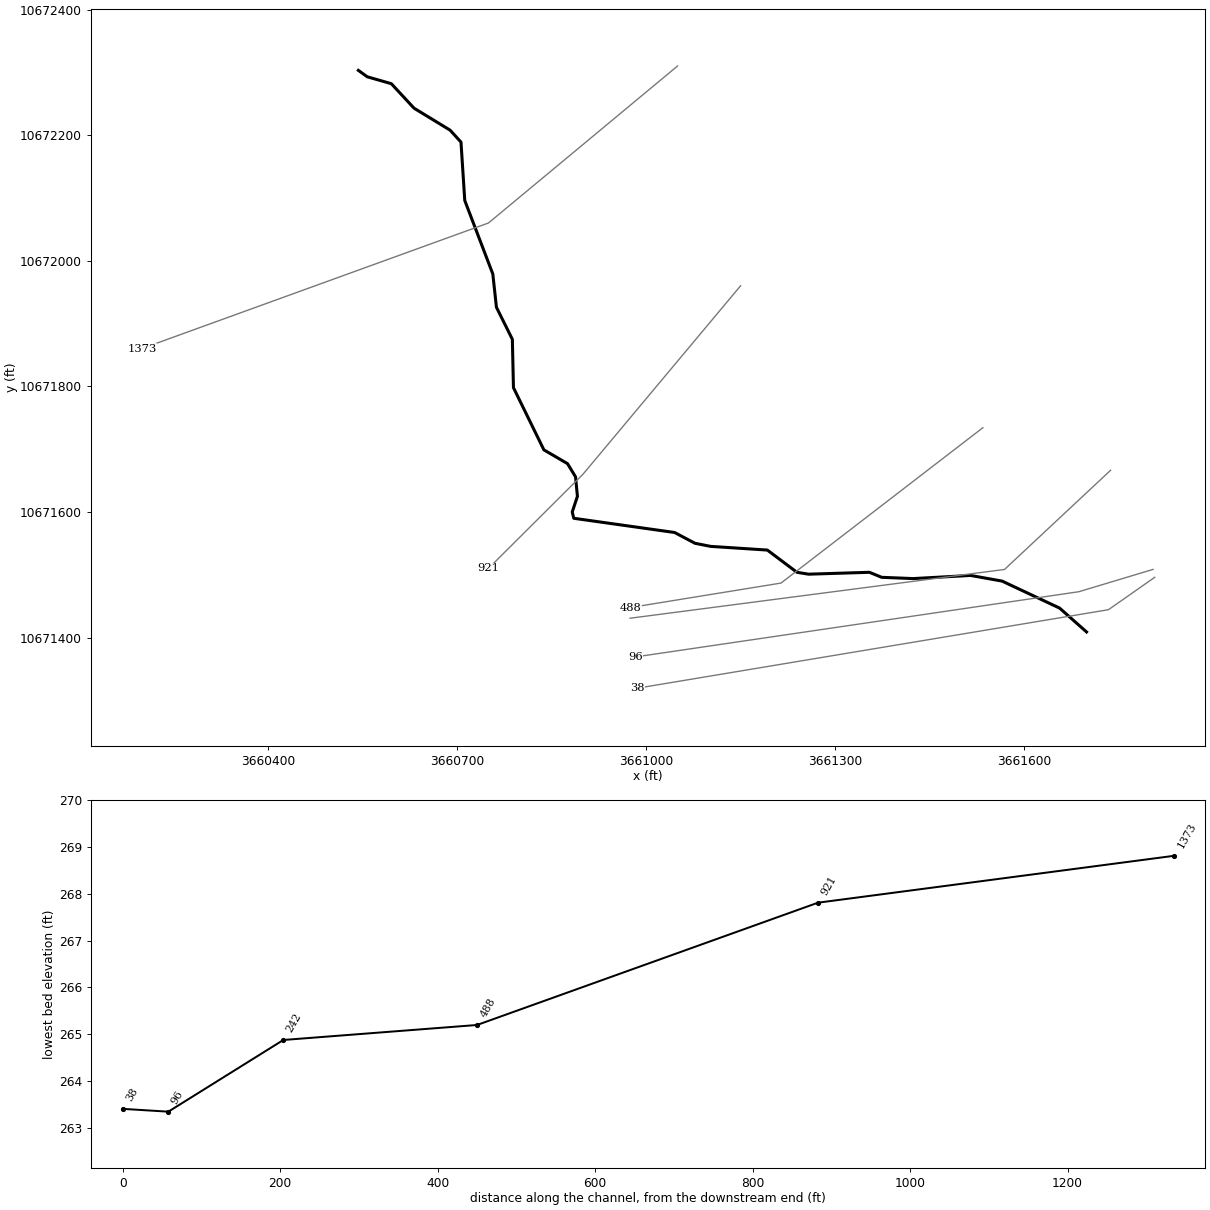
--- UNT 02734 IN LACR.prj (project) ---

Proj Title=UNT 02734 IN LACR Base Level Engineering
Current Plan=p01
Default Exp/Contr=0.3,0.1
English Units
Geom File=g01
Flow File=f01
Plan File=p01
BEGIN DESCRIPTION:
UNT 02734 IN LACR
END DESCRIPTION:

--- UNT 02734 IN LACR.p01 (plan) ---

Plan Title=Multiple Run
Short Identifier=Multiple
Geom File=g01
Flow File=f01
Subcritical Flow
K Sum by GR= 0
Std Step Tol= 0.01
Critical Tol= 0.01
Num of Std Step Trials= 20
Max Error Tol= 0.3
Flow Tol Ratio= 0.001
Split Flow NTrial= 30
Split Flow Tol= 0.02
Split Flow Ratio= 0.02
Log Output Level= 0
Friction Slope Method= 1
Unsteady Friction Slope Method= 2
Unsteady Bridges Friction Slope Method= 1
Parabolic Critical Depth
Global Vel Dist=  1 , 1 , 1
Global Log Level= 0
CheckData=True
Encroach Param= -1, 0, 0, 0
BEGIN DESCRIPTION:
Multiple Run
END DESCRIPTION:

--- UNT 02734 IN LACR.f01 (steady flow) ---

Flow Title=Multiple
Number of Profiles=7
Profile Names=10-year,25-year,50-year,1pct_min,100-year,1pct_plu,500-year
River Rch & RM= UNT 02734 IN LAC,Reach-1,1373
     175     217     249     210     284     384     370
Boundary for River Rch & Prof#=UNT 02734 IN LAC,Reach-1,1
Up Type=0
Dn Type=3
Dn Slope=0.005
Boundary for River Rch & Prof#=UNT 02734 IN LAC,Reach-1,2
Up Type=0
Dn Type=3
Dn Slope=0.005
Boundary for River Rch & Prof#=UNT 02734 IN LAC,Reach-1,3
Up Type=0
Dn Type=3
Dn Slope=0.005
Boundary for River Rch & Prof#=UNT 02734 IN LAC,Reach-1,4
Up Type=0
Dn Type=3
Dn Slope=0.005
Boundary for River Rch & Prof#=UNT 02734 IN LAC,Reach-1,5
Up Type=0
Dn Type=3
Dn Slope=0.005
Boundary for River Rch & Prof#=UNT 02734 IN LAC,Reach-1,6
Up Type=0
Dn Type=3
Dn Slope=0.005
Boundary for River Rch & Prof#=UNT 02734 IN LAC,Reach-1,7
Up Type=0
Dn Type=3
Dn Slope=0.005

--- UNT 02734 IN LACR.g01 (geometry) ---

Geom Title=Existing Conditions

River Reach=UNT 02734 IN LAC,Reach-1
Reach XY= 30
      3660543.18     10672303.22      3660557.25     10672293.00
      3660595.50     10672282.00      3660631.50     10672243.00
      3660688.75     10672208.00      3660706.00     10672189.00
      3660712.00     10672096.00      3660756.50     10671979.00
      3660762.25     10671926.00      3660787.50     10671875.00
      3660789.25     10671798.00      3660837.50     10671699.00
      3660875.00     10671677.00      3660887.75     10671656.00
      3660890.75     10671625.00      3660882.50     10671600.00
      3660885.00     10671590.00      3661044.96     10671567.37
      3661077.17     10671550.23      3661101.91     10671545.29
      3661192.06     10671539.39      3661239.00     10671504.00
      3661257.50     10671501.00      3661354.00     10671504.00
      3661373.50     10671496.00      3661423.50     10671494.00
      3661514.50     10671499.00      3661564.50     10671490.00
      3661655.75     10671447.00      3661698.50     10671409.00

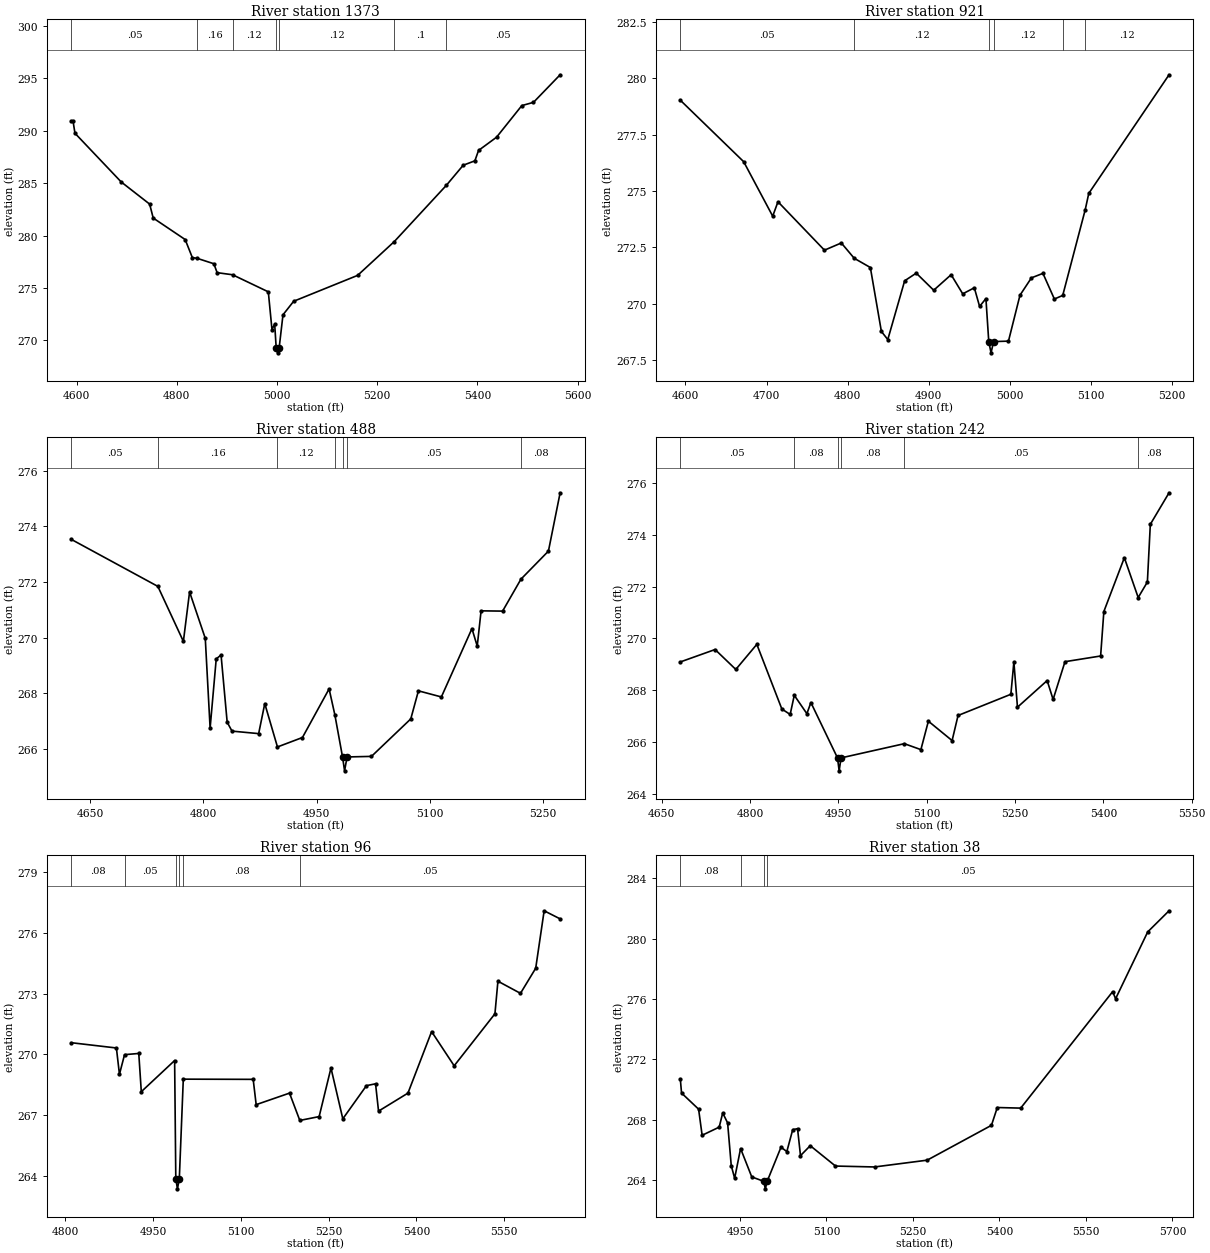
Type RM Length L Ch R = 1,1373,452,452,452
BEGIN DESCRIPTION:
UNT 02734 IN LACR 3.0
END DESCRIPTION:
XS GIS Cut Line= 3
      3661049.58     10672310.16      3660749.61     10672060.19
      3660199.62     10671860.19
#Sta/Elev= 30
  4589.6  290.93  4592.8  290.93  4596.7  289.76  4689.1  285.11  4745.8  283.00
  4752.9  281.67  4816.7  279.62  4831.0  277.90  4841.1  277.82  4874.0  277.31
  4880.5  276.46  4911.3  276.26  4982.7  274.63  4990.0  271.03  4995.4  271.56
  4998.4  269.31  5001.1  268.81  5004.4  269.31  5012.0  272.44  5033.3  273.73
  5161.0  276.20  5234.3  279.43  5338.1  284.79  5371.8  286.71  5395.1  287.13
  5402.4  288.12  5438.3  289.38  5488.8  292.40  5512.1  292.71  5565.3  295.34
#Mann=7,-1,0
  4589.6    0.05       0  4841.1    0.16       0  4911.3    0.12       0
  4998.4    0.07       0  5004.4    0.12       0  5234.3     0.1       0
  5338.1    0.05       0
Bank Sta=4998.4,5004.4
Exp/Cntr=0.3,0.1

Type RM Length L Ch R = 1,921,433,433,433
BEGIN DESCRIPTION:
UNT 02734 IN LACR 2.0
END DESCRIPTION:
XS GIS Cut Line= 3
      3661149.59     10671960.17      3660899.61     10671660.19
      3660749.62     10671510.20
#Sta/Elev= 30
  4593.7  279.03  4671.8  276.30  4707.6  273.88  4714.1  274.52  4771.4  272.37
  4792.2  272.69  4808.1  272.01  4828.0  271.60  4841.6  268.76  4849.5  268.40
  4870.3  271.01  4884.6  271.35  4906.1  270.59  4927.6  271.28  4941.9  270.43
  4956.2  270.70  4962.7  269.87  4970.5  270.22  4974.0  268.31  4976.8  267.81
  4980.0  268.31  4998.3  268.33  5012.5  270.37  5026.6  271.14  5040.8  271.34
  5054.9  270.20  5065.2  270.36  5092.9  274.16  5097.3  274.89  5196.3  280.16
#Mann=6,-1,0
  4593.7    0.05       0  4808.1    0.12       0  4974.0    0.07       0
  4980.0    0.12       0  5065.2    0.16       0  5092.9    0.12       0
Bank Sta=4974,4980
Exp/Cntr=0.3,0.1

Type RM Length L Ch R = 1,488,246,246,246
BEGIN DESCRIPTION:
Mapping XS d470a763
END DESCRIPTION:
XS GIS Cut Line= 3
      3661534.07     10671734.27      3661213.74     10671486.86
      3660974.35     10671447.83
#Sta/Elev= 30
  4625.2  273.53  4739.7  271.84  4773.5  269.86  4781.7  271.64  4802.5  269.97
  4808.9  266.74  4817.0  269.23  4823.4  269.37  4831.5  266.95  4837.9  266.63
  4873.2  266.54  4881.3  267.62  4898.1  266.06  4931.2  266.40  4966.5  268.15
  4974.1  267.22  4984.3  265.70  4987.0  265.20  4990.3  265.70  5022.6  265.72
  5074.7  267.07  5084.8  268.08  5115.2  267.86  5155.7  270.32  5162.7  269.69
  5167.8  270.96  5196.3  270.95  5220.6  272.10  5257.0  273.11  5272.5  275.21
#Mann=7,-1,0
  4625.2    0.05       0  4739.7    0.16       0  4898.1    0.12       0
  4974.1    0.05       0  4984.3    0.04       0  4990.3    0.05       0
  5220.6    0.08       0
Bank Sta=4984.3,4990.3
Exp/Cntr=0.3,0.1

Type RM Length L Ch R = 1,242,146,146,146
BEGIN DESCRIPTION:
Mapping XS f4956bff
END DESCRIPTION:
XS GIS Cut Line= 3
      3661736.71     10671666.49      3661568.33     10671508.52
      3660974.36     10671430.90
#Sta/Elev= 30
  4681.7  269.09  4740.7  269.57  4775.9  268.80  4811.6  269.77  4854.1  267.27
  4868.2  267.06  4875.2  267.80  4896.6  267.09  4903.4  267.52  4948.6  265.38
  4951.4  264.88  4954.6  265.38  5062.1  265.93  5090.2  265.70  5102.9  266.80
  5143.2  266.05  5153.3  267.02  5243.0  267.84  5248.1  269.09  5254.2  267.34
  5304.6  268.37  5314.7  267.64  5334.9  269.10  5395.4  269.32  5400.9  271.04
  5435.7  273.12  5459.2  271.58  5474.8  272.18  5479.8  274.41  5511.6  275.63
#Mann=6,-1,0
  4681.7    0.05       0  4875.2    0.08       0  4948.6    0.07       0
  4954.6    0.08       0  5062.1    0.05       0  5459.2    0.08       0
Bank Sta=4948.6,4954.6
Exp/Cntr=0.3,0.1

Type RM Length L Ch R = 1,96,58,58,58
BEGIN DESCRIPTION:
Mapping XS cec0337c
END DESCRIPTION:
XS GIS Cut Line= 3
      3661804.02     10671508.62      3661686.38     10671473.11
      3660982.59     10671369.22
#Sta/Elev= 30
  4810.9  270.57  4887.7  270.31  4892.9  269.01  4901.6  269.98  4925.9  270.04
  4930.2  268.15  4987.1  269.69  4989.1  263.85  4991.9  263.35  4995.1  263.85
  5001.9  268.77  5121.2  268.76  5126.3  267.51  5183.2  268.08  5200.8  266.73
  5233.8  266.92  5254.0  269.32  5274.2  266.81  5314.6  268.45  5330.1  268.54
  5335.2  267.19  5385.4  268.08  5425.8  271.12  5464.3  269.43  5533.9  272.00
  5539.0  273.61  5577.5  273.01  5603.5  274.25  5617.9  277.09  5645.2  276.69
#Mann=6,-1,0
  4810.9    0.08       0  4901.6    0.05       0  4989.1    0.04       0
  4995.1    0.05       0  5001.9    0.08       0  5200.8    0.05       0
Bank Sta=4989.1,4995.1
Exp/Cntr=0.3,0.1

Type RM Length L Ch R = 1,38,0,0,0
BEGIN DESCRIPTION:
UNT 02734 IN LACR 1.0
END DESCRIPTION:
XS GIS Cut Line= 3
      3661806.73     10671496.08      3661733.26     10671444.46
      3660985.84     10671319.46
#Sta/Elev= 30
  4846.5  270.68  4848.6  269.76  4878.2  268.69  4884.3  266.96  4913.9  267.50
  4920.0  268.44  4928.5  267.78  4934.8  264.95  4940.7  264.11  4951.0  266.08
  4970.4  264.20  4991.1  263.91  4993.9  263.41  4997.1  263.91  5021.1  266.17
  5031.2  265.88  5041.4  267.33  5049.8  267.40  5054.9  265.61  5071.8  266.27
  5115.6  264.92  5183.3  264.86  5274.6  265.31  5386.1  267.62  5396.2  268.80
  5436.8  268.76  5596.3  276.48  5601.4  276.01  5657.1  280.44  5694.1  281.84
#Mann=4,-1,0
  4846.5    0.08       0  4951.0    0.05       0  4991.1    0.03       0
  4997.1    0.05       0
Bank Sta=4991.1,4997.1
Exp/Cntr=0.3,0.1

Chan Stop Cuts=-1