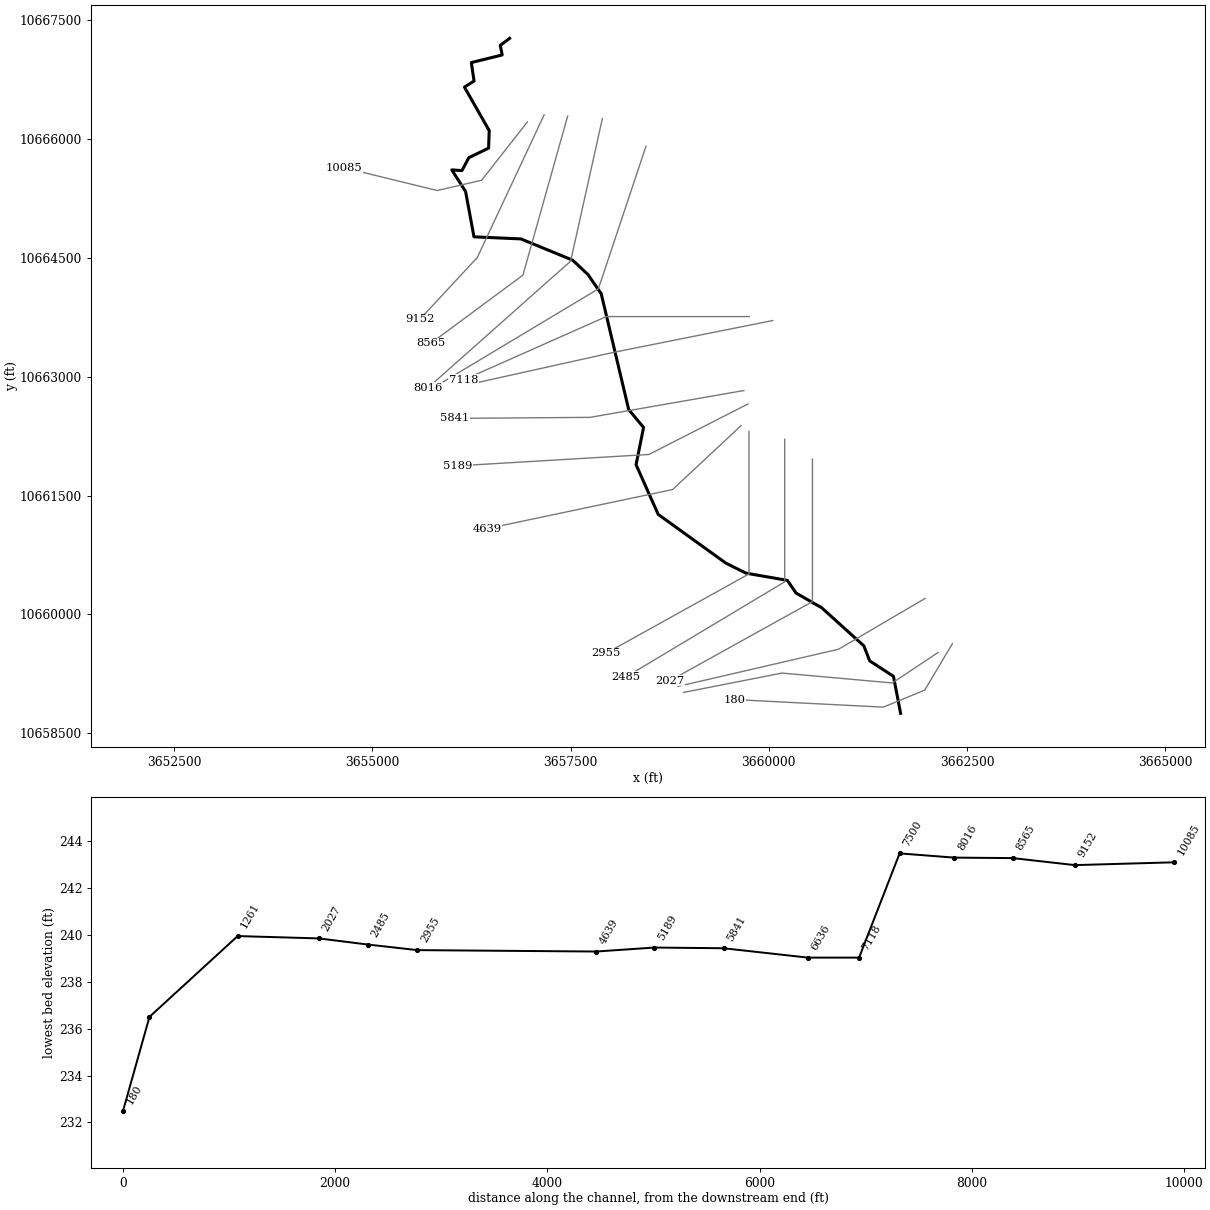
--- UNT 02754 IN LACR.prj (project) ---

Proj Title=UNT 02754 IN LACR Base Level Engineering
Current Plan=p01
Default Exp/Contr=0.3,0.1
English Units
Geom File=g01
Flow File=f01
Plan File=p01
Y Axis Title=Elevation
X Axis Title(PF)=Main Channel Distance
X Axis Title(XS)=Station
BEGIN DESCRIPTION:
UNT 02754 IN LACR
END DESCRIPTION:
DSS Export Rating Curves= 0
DSS Export Rating Curve Sorted= 0
DSS Export Volume Flow Curves= 0
DXF OffsetX= 0
DXF OffsetY= 0
DXF ScaleX= 1
DXF ScaleY= 10

--- UNT 02754 IN LACR.p01 (plan) ---

Plan Title=Multiple Run
Short Identifier=Multiple
Geom File=g01
Flow File=f01
Subcritical Flow
K Sum by GR= 0
Std Step Tol= 0.01
Critical Tol= 0.01
Num of Std Step Trials= 20
Max Error Tol= 0.3
Flow Tol Ratio= 0.001
Split Flow NTrial= 30
Split Flow Tol= 0.02
Split Flow Ratio= 0.02
Log Output Level= 0
Friction Slope Method= 1
Unsteady Friction Slope Method= 2
Unsteady Bridges Friction Slope Method= 1
Parabolic Critical Depth
Global Vel Dist=  1 , 1 , 1
Global Log Level= 0
CheckData=True
Encroach Param= -1, 0, 0, 0
BEGIN DESCRIPTION:
Multiple Run
END DESCRIPTION:

--- UNT 02754 IN LACR.f01 (steady flow) ---

Flow Title=Multiple
Program Version=4.10
Number of Profiles= 7
Profile Names=10-year,25-year,50-year,1pct_min,100-year,1pct_plu,500-year
River Rch & RM=UNT 02754 IN LAC,Reach-1         ,10085
     336     434     510     441     597     807     818
River Rch & RM=UNT 02754 IN LAC,Reach-1         ,9152
     506     664     790     689     932    1260    1302
Boundary for River Rch & Prof#=UNT 02754 IN LAC,Reach-1         , 1
Up Type= 0
Dn Type= 3
Dn Slope=0.001
Boundary for River Rch & Prof#=UNT 02754 IN LAC,Reach-1         , 2
Up Type= 0
Dn Type= 3
Dn Slope=0.001
Boundary for River Rch & Prof#=UNT 02754 IN LAC,Reach-1         , 3
Up Type= 0
Dn Type= 3
Dn Slope=0.001
Boundary for River Rch & Prof#=UNT 02754 IN LAC,Reach-1         , 4
Up Type= 0
Dn Type= 3
Dn Slope=0.001
Boundary for River Rch & Prof#=UNT 02754 IN LAC,Reach-1         , 5
Up Type= 0
Dn Type= 3
Dn Slope=0.001
Boundary for River Rch & Prof#=UNT 02754 IN LAC,Reach-1         , 6
Up Type= 0
Dn Type= 3
Dn Slope=0.001
Boundary for River Rch & Prof#=UNT 02754 IN LAC,Reach-1         , 7
Up Type= 0
Dn Type= 3
Dn Slope=0.001
DSS Import GetInterval= 0
DSS Import GetPeak= 0
DSS Import FillOption= 0

--- UNT 02754 IN LACR.g01 (geometry) ---

Geom Title=Existing Conditions
Program Version=4.10

River Reach=UNT 02754 IN LAC,Reach-1
Reach XY= 30
        3656730.       10667274.        3656612.       10667185.
      3656636.25       10667064.      3656246.75       10666968.
       3656281.5       10666735.        3656160.       10666658.
       3656472.5       10666109.      3656464.75       10665888.
      3656214.75       10665766.      3656128.75       10665604.
      3656000.25       10665613.      3656174.75       10665339.
      3656280.25       10664767.      3656872.25       10664741.
        3657526.       10664472.      3657718.75       10664290.
       3657885.5       10664048.      3658231.75       10662586.
       3658419.5       10662360.        3658325.       10661889.
        3658604.       10661262.      3659456.75       10660647.
      3659710.75       10660520.      3660232.75       10660429.
       3660343.5       10660268.        3660666.       10660083.
        3661198.       10659602.      3661271.75       10659412.
       3661571.5       10659217.      3661661.75       10658749.

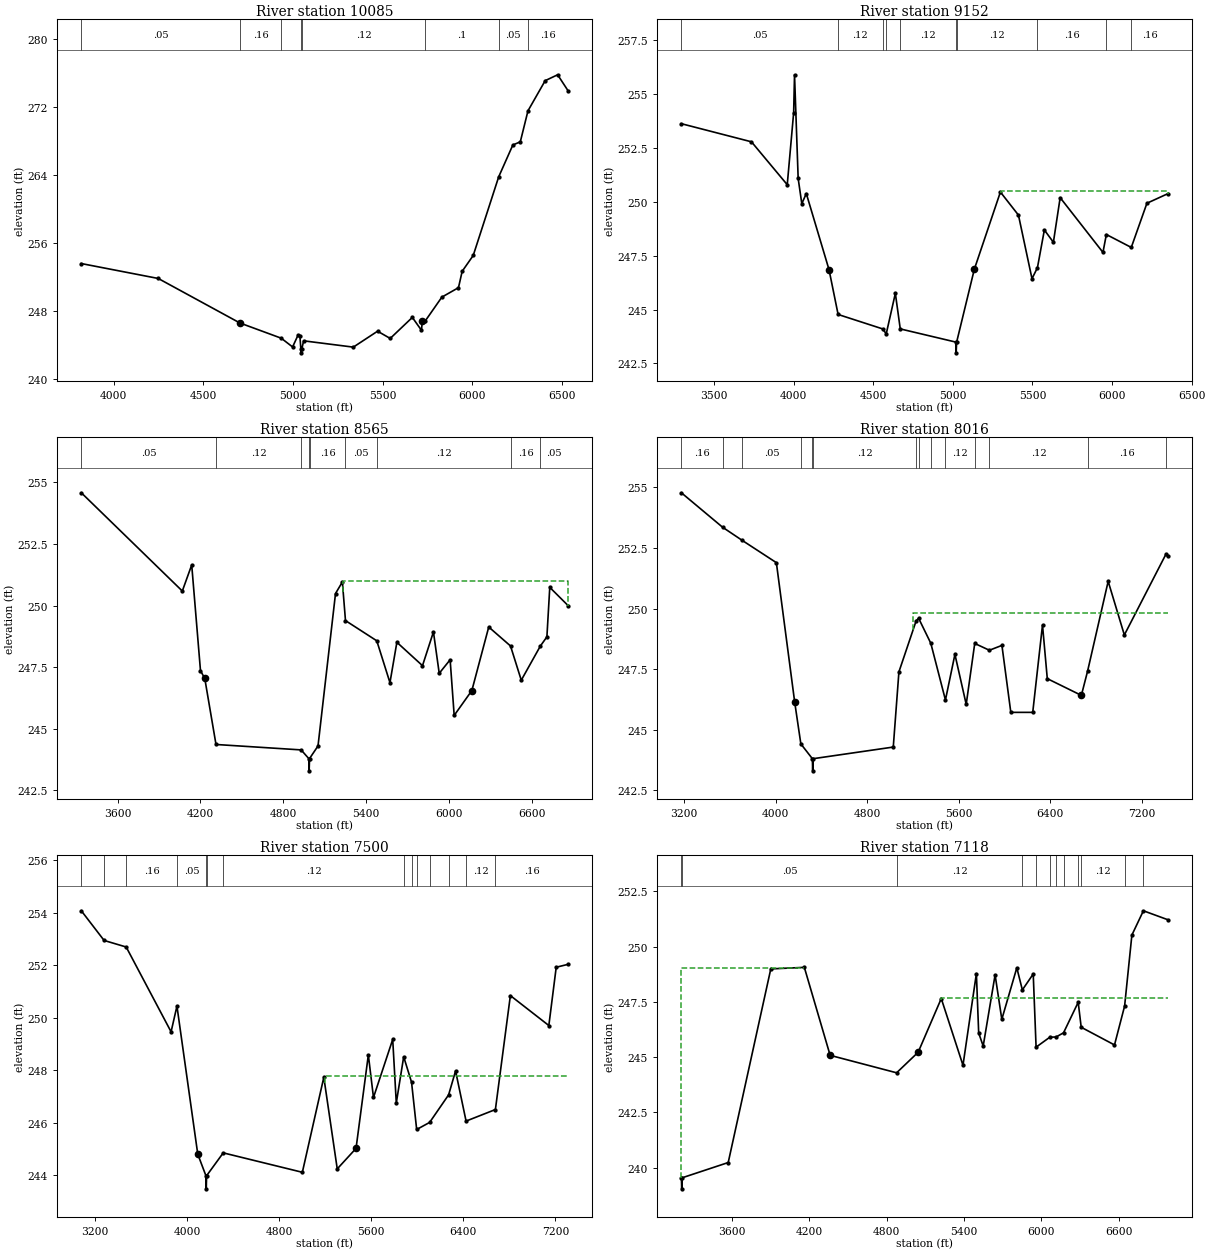
Type RM Length L Ch R = 1 ,10085   ,933,933,933
BEGIN DESCRIPTION:
UNT 02754 IN LACR 14.0
END DESCRIPTION:
XS GIS Cut Line= 4
      3656953.94     10666217.98       3656377.3     10665482.18
      3655817.41     10665351.97      3654645.48     10665638.44
#Sta/Elev= 30
  3819.1  253.59  4248.3  251.84  4704.4  246.61  4704.5  246.61  4934.5  244.83
    4998   243.8  5028.8  245.21    5039  245.03  5043.9  243.61  5046.7  243.11
  5049.9  243.61  5059.6  244.52  5336.8  243.78  5472.2  245.65  5542.7   244.8
  5666.2  247.27  5716.9  245.76  5722.1  246.83  5736.7  246.81  5830.9  249.65
  5923.6  250.76  5944.2  252.68  6005.9  254.54    6148  263.77    6227  267.51
  6268.6  267.88  6311.4  271.52  6407.4  275.06  6476.9  275.75  6535.2  273.87
#Mann= 8 ,-1 , 0
  3819.1     .05       0  4704.4     .16       0  4934.5     .12       0
  5043.9     .07       0  5049.9     .12       0  5736.7      .1       0
    6148     .05       0  6311.4     .16       0
Bank Sta=4704.5,5722.1
XS Rating Curve= 0 ,0
Exp/Cntr=0.3,0.1

Type RM Length L Ch R = 1 ,9152    ,587,587,587
BEGIN DESCRIPTION:
UNT 02754 IN LACR 13.0
END DESCRIPTION:
XS GIS Cut Line= 3
       3657165.8     10666308.77      3656321.42     10664504.93
      3655596.43     10663724.77
#Sta/Elev= 30
  3295.6  253.62  3735.7  252.78  3960.4  250.79  4000.6  254.13  4006.1  255.89
    4029  251.08  4051.8  249.91  4080.1  250.38  4222.7  246.85  4279.8  244.77
  4559.8   244.1    4582  243.87  4639.2  245.75  4670.1   244.1  5018.2  243.49
  5020.9  242.99  5024.2  243.49  5135.3  246.87  5298.9  250.45  5412.3  249.38
  5497.3  246.43  5531.5  246.94    5575  248.69  5631.7  248.12  5674.2  250.19
  5942.9  247.65  5964.3  248.48  6120.8  247.88    6219  249.93  6352.3  250.38
#Mann= 10 ,-1 , 0
  3295.6     .05       0  4279.8     .12       0  4559.8     .05       0
    4582      .1       0  4670.1     .12       0  5018.2     .07       0
  5024.2     .12       0  5531.5     .16       0  5964.3     .12       0
  6120.8     .16       0
#XS Ineff= 2 , 0
                         5302.63          250.48
Permanent Ineff=
       F       F
Bank Sta=4222.7,5135.3
XS Rating Curve= 0 ,0
Exp/Cntr=0.3,0.1

Type RM Length L Ch R = 1 ,8565    ,549,549,549
BEGIN DESCRIPTION:
UNT 02754 IN LACR 12.0
END DESCRIPTION:
XS GIS Cut Line= 3
      3657462.12     10666291.49      3656898.14     10664284.26
      3655739.51     10663425.06
#Sta/Elev= 30
  3336.6  254.58  4068.5  250.59  4136.6  251.65  4200.1  247.36  4231.3  247.04
  4312.6  244.36  4929.6  244.14  4984.6  243.79  4987.4  243.29  4990.6  243.79
  5051.8   244.3  5178.7  250.49  5228.4  250.96  5250.9  249.39  5477.7  248.57
  5573.2  246.87  5623.3  248.51    5809  247.56  5888.3  248.93  5930.2  247.25
  6009.3   247.8  6038.6  245.54  6166.7  246.55    6289  249.13  6446.8  248.36
  6524.8  246.97  6663.4  248.36  6710.5  248.73  6731.3  250.74    6864     250
#Mann= 9 ,-1 , 0
  3336.6     .05       0  4312.6     .12       0  4929.6     .16       0
  4984.6     .07       0  4990.6     .16       0  5250.9     .05       0
  5477.7     .12       0  6446.8     .16       0  6663.4     .05       0
#XS Ineff= 2 , 0
                         5234.45             251
Permanent Ineff=
       F       F
Bank Sta=4231.3,6166.7
XS Rating Curve= 0 ,0
Exp/Cntr=0.3,0.1

Type RM Length L Ch R = 1 ,8016    ,516,516,516
BEGIN DESCRIPTION:
UNT 02754 IN LACR 11.0
END DESCRIPTION:
XS GIS Cut Line= 3
      3657899.62     10666260.22      3657499.61     10664460.19
      3655699.58     10662860.16
#Sta/Elev= 30
  3176.3  254.77  3536.3  253.35  3706.9  252.81  4006.1  251.89  4166.2  246.14
    4220  244.42  4320.7  243.81  4323.4  243.31  4326.7  243.81  5027.3  244.29
  5076.7  247.39  5227.1  249.49  5248.5   249.6  5355.1  248.57  5483.1  246.23
  5565.9  248.11  5664.5  246.05    5739  248.56  5866.9  248.28  5976.5  248.48
  6054.2  245.72  6245.7  245.72    6331  249.32  6372.8  247.11  6670.5  246.42
  6724.9  247.42  6904.7  251.12    7046  248.91  7409.4  252.24  7428.6  252.17
#Mann= 14 ,-1 , 0
  3176.3     .16       0  3536.3     .12       0  3706.9     .05       0
    4220     .12       0  4320.7     .07       0  4326.7     .12       0
  5227.1      .1       0  5248.5     .16       0  5355.1     .05       0
  5483.1     .12       0    5739     .05       0  5866.9     .12       0
  6724.9     .16       0  7409.4     .05       0
#XS Ineff= 2 , 0
                         5200.96          249.82
Permanent Ineff=
       F       F
Bank Sta=4166.2,6670.5
XS Rating Curve= 0 ,0
Exp/Cntr=0.3,0.1

Type RM Length L Ch R = 1 ,7500    ,382,382,382
BEGIN DESCRIPTION:
UNT 02754 IN LACR 10.0
END DESCRIPTION:
XS GIS Cut Line= 3
      3658449.61      10665910.2      3657849.61     10664110.19
      3655849.57     10662910.17
#Sta/Elev= 30
  3080.4  254.08  3278.4  252.95  3470.4   252.7  3860.4  249.47  3911.4  250.45
  4092.3  244.81  4163.1  243.99  4165.9  243.49  4169.1  243.99  4313.7  244.86
  5001.1  244.12  5187.7  247.74  5304.3  244.25  5467.6  245.03  5574.5  248.59
  5619.2  246.97  5786.3  249.18  5817.4  246.76  5881.7  248.52    5950  247.55
  5994.5  245.75  6107.2  246.02  6272.1  247.07  6332.5  247.98  6423.8  246.07
  6678.6  246.51  6808.7  250.85    7143  249.71  7207.1  251.93  7310.2  252.04
#Mann= 14 ,-1 , 0
  3080.4     .12       0  3278.4     .05       0  3470.4     .16       0
  3911.4     .05       0  4163.1     .07       0  4169.1     .05       0
  4313.7     .12       0  5881.7     .05       0    5950      .1       0
  5994.5     .05       0  6107.2     .12       0  6272.1     .16       0
  6423.8     .12       0  6678.6     .16       0
#XS Ineff= 2 , 0
                         5194.98          247.78
Permanent Ineff=
       F       F
Bank Sta=4092.3,5467.6
XS Rating Curve= 0 ,0
Exp/Cntr=0.3,0.1

Type RM Length L Ch R = 1 ,7118    ,482,482,482
BEGIN DESCRIPTION:
UNT 02754 IN LACR 9.0
END DESCRIPTION:
XS GIS Cut Line= 3
      3659752.57     10663760.19      3657949.61     10663760.19
      3656149.64      10662960.2
#Sta/Elev= 30
  3208.9  239.54  3211.6  239.04  3214.9  239.54  3571.9  240.23  3901.9  248.99
  4161.9  249.06  4361.9  245.08  4877.1  244.29    5044  245.22  5223.2  247.65
  5391.5  244.63  5495.4  248.78  5513.2  246.09  5548.1   245.5  5640.4  248.72
  5692.4  246.71  5808.7  249.04  5851.6  248.04  5935.9  248.76  5958.1  245.45
  6064.5   245.9    6113  245.91  6170.9   246.1  6284.5  247.48  6307.7  246.35
  6565.8  245.55  6644.2  247.31  6700.5  250.52  6789.8  251.62  6981.6  251.21
#Mann= 12 ,-1 , 0
  3208.9     .07       0  3214.9     .05       0  4877.1     .12       0
  5851.6     .16       0  5958.1      .1       0  6064.5     .05       0
    6113     .08       0  6170.9     .12       0  6284.5     .16       0
  6307.7     .12       0  6644.2     .16       0  6789.8     .12       0
#XS Ineff= 2 , 0
         4157.89  249.04 5217.44          247.67
Permanent Ineff=
       F       F
Bank Sta=4361.9,5044
XS Rating Curve= 0 ,0
Exp/Cntr=0.3,0.1

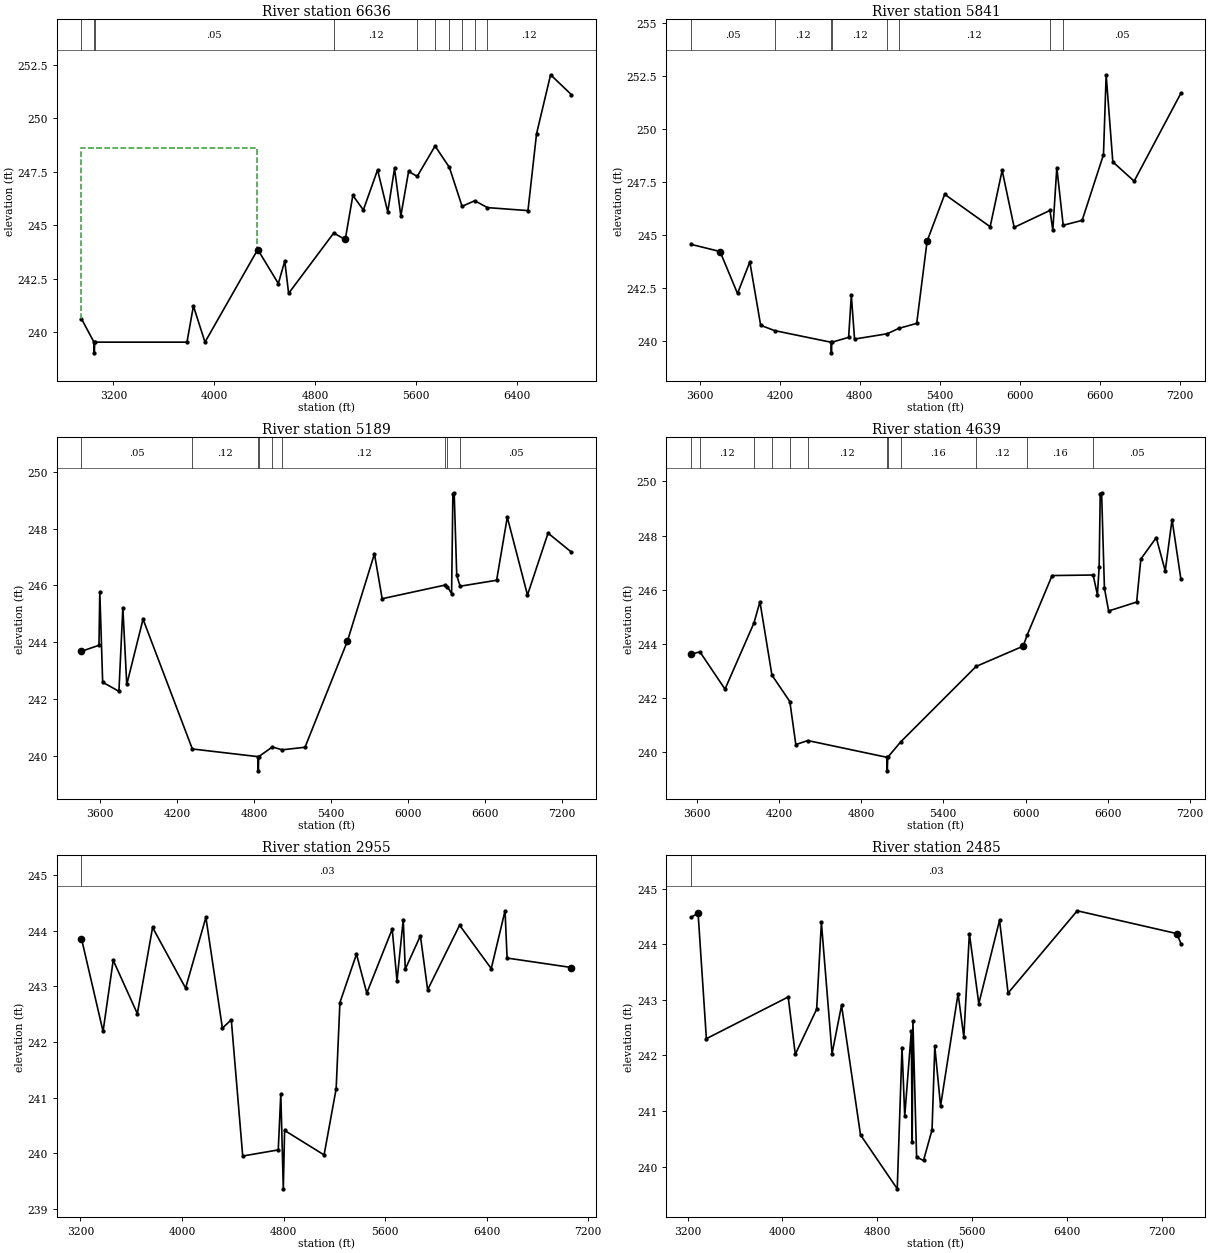
Type RM Length L Ch R = 1 ,6636    ,795,795,795
BEGIN DESCRIPTION:
UNT 02754 IN LACR 8.0
END DESCRIPTION:
XS GIS Cut Line= 3
      3660049.58     10663710.18      3658049.61     10663310.19
       3656249.6     10662910.19
#Sta/Elev= 30
  2946.2  240.63  3045.2  239.54  3047.9  239.04  3051.2  239.54  3782.4  239.54
  3833.4  241.23  3925.2  239.54  4343.3  243.87  4506.5  242.28  4557.5  243.33
  4588.1  241.82  4945.4  244.64    5037  244.34  5097.2   246.4  5180.4  245.72
  5293.1  247.59  5373.8  245.63  5427.6  247.66  5477.5  245.44    5539  247.52
  5607.4  247.29  5748.9  248.71  5862.4  247.71  5962.9  245.89  6063.4  246.15
  6163.9  245.83  6485.2  245.69  6553.1  249.28  6664.5  252.04  6829.7  251.11
#Mann= 10 ,-1 , 0
  2946.2     .05       0  3045.2     .07       0  3051.2     .05       0
  4945.4     .12       0  5607.4     .16       0  5748.9     .12       0
  5862.4     .16       0  5962.9     .12       0  6063.4     .05       0
  6163.9     .12       0
#XS Ineff= 2 , 0
         4335.72  248.61
Permanent Ineff=
       F       F
Bank Sta=4343.3,5037
XS Rating Curve= 0 ,0
Exp/Cntr=0.3,0.1

Type RM Length L Ch R = 1 ,5841    ,652,652,652
BEGIN DESCRIPTION:
UNT 02754 IN LACR 7.0
END DESCRIPTION:
XS GIS Cut Line= 3
      3659684.59     10662825.93      3657744.49     10662487.39
      3656038.75     10662474.37
#Sta/Elev= 30
  3533.1  244.56  3751.3  244.22  3882.3  242.24  3974.6  243.73  4055.9  240.74
  4159.9  240.49  4583.7  239.94  4586.4  239.44  4589.7  239.94  4715.7  240.17
    4736  242.15  4760.2  240.09  5005.2  240.34  5090.4  240.59  5226.4  240.83
  5304.4  244.71  5436.4  246.92  5777.4  245.39  5867.4  248.05  5957.4  245.36
  6226.2  246.16  6247.4  245.22  6277.4  248.18  6325.2  245.46  6467.4  245.69
  6627.4  248.79  6647.4  252.56  6697.4  248.45  6857.4  247.54  7208.3  251.69
#Mann= 8 ,-1 , 0
  3533.1     .05       0  4159.9     .12       0  4583.7     .07       0
  4589.7     .12       0  5005.2     .16       0  5090.4     .12       0
  6226.2     .08       0  6325.2     .05       0
Bank Sta=3751.3,5304.4
XS Rating Curve= 0 ,0
Exp/Cntr=0.3,0.1

Type RM Length L Ch R = 1 ,5189    ,550,550,550
BEGIN DESCRIPTION:
UNT 02754 IN LACR 6.0
END DESCRIPTION:
XS GIS Cut Line= 3
       3659736.7     10662656.67      3658486.68     10662018.64
      3656077.87     10661875.41
#Sta/Elev= 30
  3456.2  243.68  3592.4  243.89  3598.9  245.78  3621.3  242.59  3747.9  242.27
  3778.5  245.21    3809  242.51  3935.7  244.81  4319.8  240.24  4830.9  239.97
  4833.6  239.47  4836.9  239.97  4942.6  240.31  5019.8  240.21  5197.3   240.3
  5527.9  244.04  5738.3  247.11  5798.4  245.53  6287.6  246.01  6306.7  245.95
  6339.3  245.71  6349.3  249.21  6359.4  249.26  6379.4  246.35  6405.6  245.97
  6689.9  246.18  6773.1   248.4  6930.4  245.66  7090.6  247.84  7272.7  247.17
#Mann= 9 ,-1 , 0
  3456.2     .05       0  4319.8     .12       0  4830.9     .07       0
  4836.9     .12       0  4942.6     .07       0  5019.8     .12       0
  6287.6     .16       0  6306.7     .08       0  6405.6     .05       0
Bank Sta=3456.2,5527.9
XS Rating Curve= 0 ,0
Exp/Cntr=0.3,0.1

Type RM Length L Ch R = 1 ,4639    ,1684,1684,1684
BEGIN DESCRIPTION:
UNT 02754 IN LACR 5.0
END DESCRIPTION:
XS GIS Cut Line= 3
      3659648.59     10662382.31      3658786.16     10661575.93
      3656443.49     10661081.37
#Sta/Elev= 30
    3559  243.61  3624.2   243.7  3807.3  242.32  4018.9  244.77  4062.3  245.55
  4149.7  242.84  4280.4  241.86  4324.1  240.27  4411.1  240.42  4988.7   239.8
  4991.4   239.3  4994.7   239.8  5089.3  240.37  5639.5  243.16  5983.1  243.91
  6011.4  244.31  6194.1  246.52  6493.6  246.54  6524.7  245.81  6537.3  246.83
  6545.2  249.53  6555.4  249.58  6575.8  246.06  6606.5  245.21  6810.9  245.54
  6841.6  247.13    6954  247.92  7019.6  246.69  7069.3  248.59    7134  246.38
#Mann= 12 ,-1 , 0
    3559     .07       0  3624.2     .12       0  4018.9     .16       0
  4149.7     .05       0  4280.4     .07       0  4411.1     .12       0
  4988.7     .07       0  4994.7     .12       0  5089.3     .16       0
  5639.5     .12       0  6011.4     .16       0  6493.6     .05       0
Bank Sta=3559,5983.1
XS Rating Curve= 0 ,0
Exp/Cntr=0.3,0.1

Type RM Length L Ch R = 1 ,2955    ,470,470,470
BEGIN DESCRIPTION:
UNT 02754 IN LACR 4.0
END DESCRIPTION:
XS GIS Cut Line= 3
      3659749.61     10662310.24      3659749.61     10660510.19
      3657949.59     10659510.18
#Sta/Elev= 30
  3208.2  243.86  3378.2  242.19  3458.2  243.47  3648.2  242.51  3768.2  244.06
  4028.2  242.97  4188.2  244.24  4318.2  242.25  4388.2   242.4  4478.2  239.95
  4758.2  240.06  4778.2  241.07    4798  239.36  4808.2  240.41  5119.2  239.97
  5214.2  241.16  5243.9  242.71  5374.3  243.58  5455.5  242.88  5655.7  244.03
  5693.5   243.1  5742.7   244.2  5758.7  243.31  5877.7  243.91  5934.9  242.94
  6186.5   244.1  6435.9  243.32  6544.6  244.36  6560.6  243.51  7067.4  243.34
#Mann= 1 ,-1 , 0
  3208.2     .03       0
Bank Sta=3208.2,7067.4
XS Rating Curve= 0 ,0
Exp/Cntr=0.3,0.1

Type RM Length L Ch R = 1 ,2485    ,458,458,458
BEGIN DESCRIPTION:
UNT 02754 IN LACR 3.0
END DESCRIPTION:
XS GIS Cut Line= 3
      3660199.61     10662210.24      3660199.61     10660410.19
      3658199.63      10659210.2
#Sta/Elev= 30
  3228.1  244.48  3288.1  244.56  3358.1   242.3  4048.1  243.05  4108.1  242.02
  4288.1  242.83  4328.1  244.39  4418.1  242.03  4498.1   242.9  4658.1  240.57
  4967.9   239.6  5008.1  242.14  5031.1  240.91  5086.5  242.43  5094.2  240.44
  5100.1  242.62  5131.2  240.17  5189.5  240.11  5261.4  240.66  5284.7  242.16
  5333.3  241.09    5481  243.11  5529.6  242.33  5576.3  244.19  5655.9  242.93
  5830.9  244.43  5902.8  243.12  6485.9   244.6  7325.5  244.19  7360.5  244.01
#Mann= 1 ,-1 , 0
  3228.1     .03       0
Bank Sta=3288.1,7325.5
XS Rating Curve= 0 ,0
Exp/Cntr=0.3,0.1

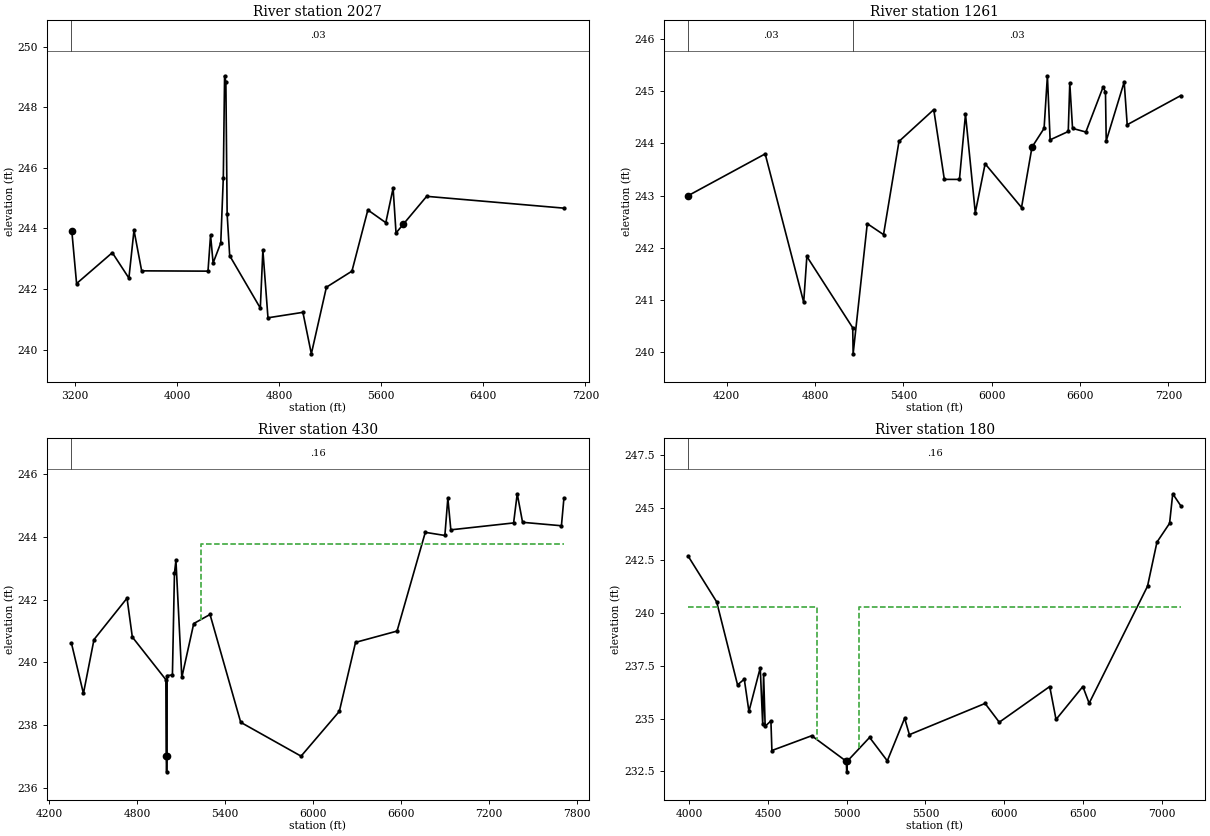
Type RM Length L Ch R = 1 ,2027    ,766,766,766
BEGIN DESCRIPTION:
UNT 02754 IN LACR 2.0
END DESCRIPTION:
XS GIS Cut Line= 3
      3660549.61     10661960.23      3660549.61     10660160.19
      3658749.58     10659160.17
#Sta/Elev= 30
  3171.9  243.92  3174.4  243.92  3211.9  242.18  3491.9   243.2  3621.9  242.36
  3661.9  243.94  3721.9   242.6  4241.9  242.59  4261.9  243.78  4281.9  242.86
  4341.9  243.52  4361.9  245.68  4371.9  249.04  4381.9  248.84  4391.9  244.47
  4411.9   243.1  4651.9  241.37  4671.9  243.28  4711.9  241.05  4985.7  241.23
  5051.8  239.86  5169.8  242.06    5370  242.59  5494.7  244.61  5635.4  244.19
  5692.6  245.33  5715.5  243.85  5772.7  244.14  5955.7  245.06  7031.1  244.67
#Mann= 1 ,-1 , 0
  3171.9     .03       0
Bank Sta=3174.4,5772.7
XS Rating Curve= 0 ,0
Exp/Cntr=0.3,0.1

Type RM Length L Ch R = 1 ,1261    ,831,831,831
BEGIN DESCRIPTION:
UNT 02754 IN LACR 1.0
END DESCRIPTION:
XS GIS Cut Line= 3
      3661971.37     10660201.11      3660877.58     10659558.72
      3658854.97     10659089.96
#Sta/Elev= 30
  3939.5     243  4461.1   243.8  4722.8  240.95  4744.3  241.83  5055.8  240.46
  5058.6  239.96  5154.6  242.46  5265.1  242.25  5370.1  244.04  5606.2  244.65
  5678.1  243.31  5780.7  243.31  5821.8  244.56  5888.3  242.67  5955.2  243.61
  6202.4  242.77  6273.5  243.93  6355.6  244.29  6378.2   245.3  6396.6  244.07
  6519.8  244.23  6530.1  245.16  6548.9  244.29  6639.4  244.22  6755.9  245.08
  6772.6  244.99  6777.7  244.05  6899.6  245.18  6920.2  244.36  7284.2  244.92
#Mann= 2 ,-1 , 0
  3939.5     .03       0  5055.8     .03       0
Bank Sta=3939.5,6273.5
XS Rating Curve= 0 ,0
Exp/Cntr=0.3,0.1

Type RM Length L Ch R = 1 ,430     ,250,250,250
BEGIN DESCRIPTION:
Mapping XS bb01dde5
END DESCRIPTION:
XS GIS Cut Line= 4
       3662135.2     10659518.51      3661557.09     10659133.11
      3660166.47     10659258.11      3658923.12      10659013.6
#Sta/Elev= 30
    4351  240.61  4432.5  239.01  4504.6  240.73  4729.9  242.05    4766  240.81
  4994.7  239.45    4997  237.01  4999.8  236.51    5003  237.01  5003.4  239.58
  5039.4   239.6  5053.3  242.84  5063.4  243.26  5103.5  239.52  5184.8  241.24
  5295.9  241.53  5505.1  238.09  5916.8  237.01  6177.8  238.44  6288.3  240.64
  6571.3     241    6764  244.15  6897.5  244.05  6917.8  245.24  6938.2  244.23
  7366.3  244.45  7390.9  245.38  7427.4  244.47  7692.4  244.36  7709.2  245.23
#Mann= 1 ,-1 , 0
    4351     .16       0
#XS Ineff= 2 , 0
                         5234.09          243.77
Permanent Ineff=
       F       F
Bank Sta=4997,5003
XS Rating Curve= 0 ,0
Exp/Cntr=0.3,0.1

Type RM Length L Ch R = 1 ,180     ,0,0,0
BEGIN DESCRIPTION:
UNT 02754 IN LACR 1.0
END DESCRIPTION:
XS GIS Cut Line= 4
      3662315.87     10659630.63      3661966.48     10659043.08
      3661443.48      10658827.7      3659568.51     10658923.18
#Sta/Elev= 30
  3994.4  242.68  4174.1  240.53  4306.6   236.6  4349.4  236.87  4378.9  235.34
  4450.7  237.41  4466.3  234.73  4472.1  237.11  4481.9  234.64  4518.5  234.89
  4524.7  233.49  4777.4  234.19    4997  232.98  4999.8  232.48    5003  232.98
  5145.1  234.11  5257.5     233  5367.6  235.02  5397.7  234.24  5878.3  235.72
  5968.4  234.83  6288.8  236.52  6328.9  234.96  6499.1  236.52  6539.1  235.73
  6909.6  241.27  6969.7  243.36  7049.8  244.25  7069.8  245.65    7121  245.08
#Mann= 1 ,-1 , 0
  3994.4     .16       0
#XS Ineff= 2 , 0
         4811.36  240.31 5079.55          240.27
Permanent Ineff=
       F       F
Bank Sta=4997,5003
XS Rating Curve= 0 ,0
Exp/Cntr=0.3,0.1

Chan Stop Cuts=-1
Use User Specified Reach Order=0
Composite Channel Slope=5