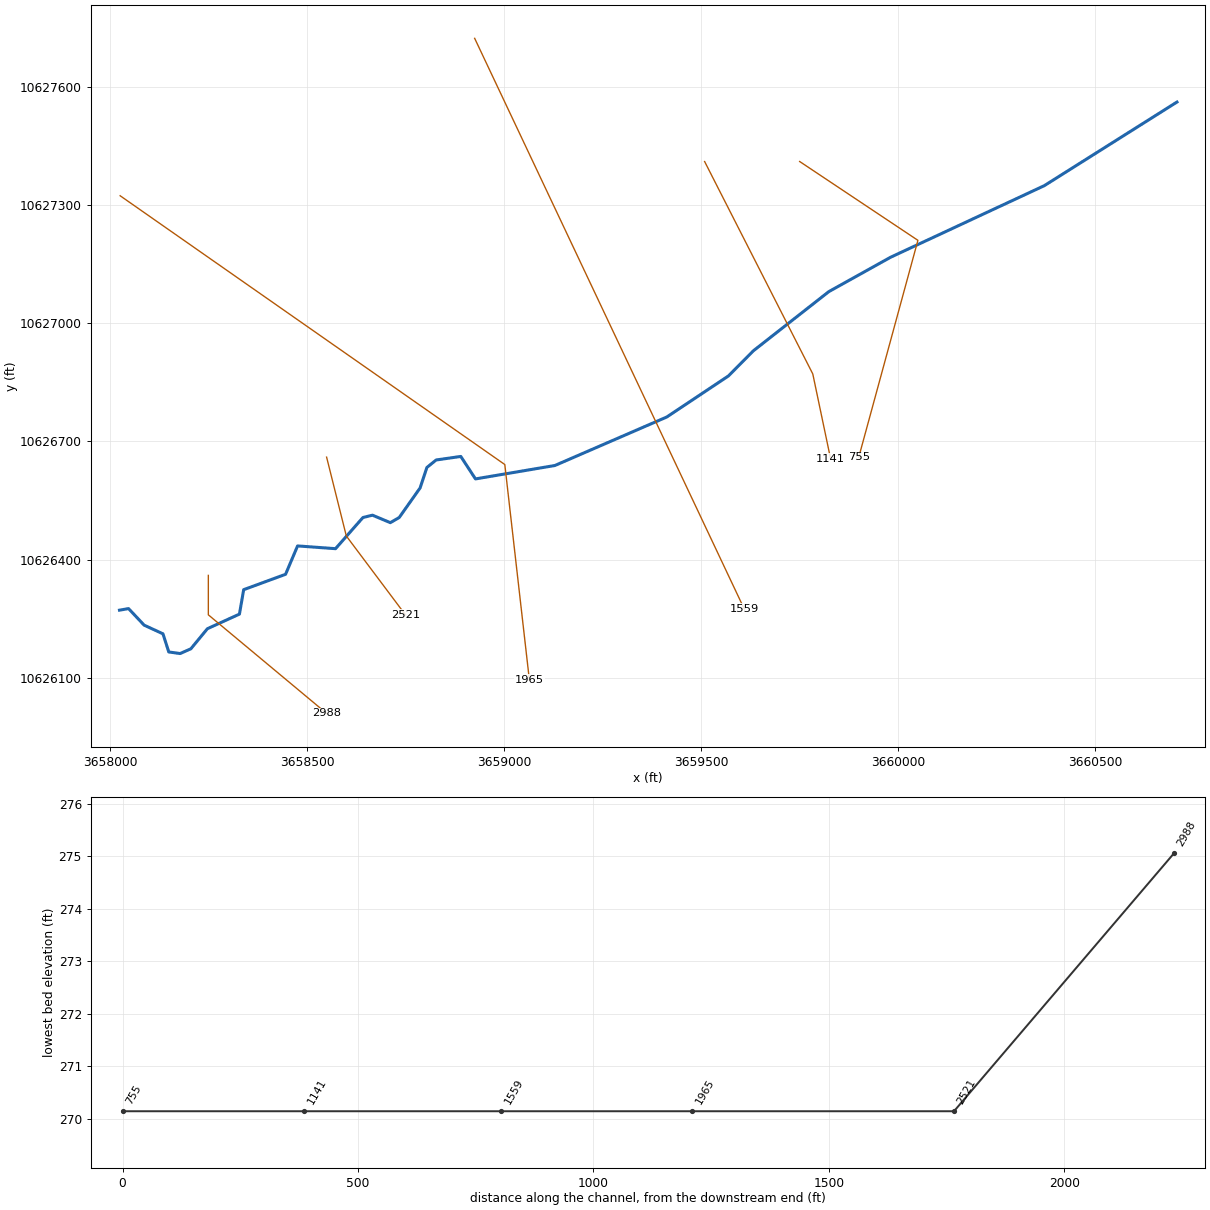
--- UNT 02819 IN LACR.prj (project) ---

Proj Title=UNT 02819 IN LACR Base Level Engineering
Current Plan=p01
Default Exp/Contr=0.3,0.1
English Units
Geom File=g01
Flow File=f01
Plan File=p01
BEGIN DESCRIPTION:
UNT 02819 IN LACR
END DESCRIPTION:

--- UNT 02819 IN LACR.p01 (plan) ---

Plan Title=Multiple Run
Short Identifier=Multiple
Geom File=g01
Flow File=f01
Subcritical Flow
K Sum by GR= 0
Std Step Tol= 0.01
Critical Tol= 0.01
Num of Std Step Trials= 20
Max Error Tol= 0.3
Flow Tol Ratio= 0.001
Split Flow NTrial= 30
Split Flow Tol= 0.02
Split Flow Ratio= 0.02
Log Output Level= 0
Friction Slope Method= 1
Unsteady Friction Slope Method= 2
Unsteady Bridges Friction Slope Method= 1
Parabolic Critical Depth
Global Vel Dist=  1 , 1 , 1
Global Log Level= 0
CheckData=True
Encroach Param= -1, 0, 0, 0
BEGIN DESCRIPTION:
Multiple Run
END DESCRIPTION:

--- UNT 02819 IN LACR.f01 (steady flow) ---

Flow Title=Multiple
Number of Profiles=7
Profile Names=10-year,25-year,50-year,1pct_min,100-year,1pct_plu,500-year
River Rch & RM= UNT 02819 IN LAC,Reach-1,2988
     360     475     568     499     675     913     959
Boundary for River Rch & Prof#=UNT 02819 IN LAC,Reach-1,1
Up Type=0
Dn Type=3
Dn Slope=0.005
Boundary for River Rch & Prof#=UNT 02819 IN LAC,Reach-1,2
Up Type=0
Dn Type=3
Dn Slope=0.005
Boundary for River Rch & Prof#=UNT 02819 IN LAC,Reach-1,3
Up Type=0
Dn Type=3
Dn Slope=0.005
Boundary for River Rch & Prof#=UNT 02819 IN LAC,Reach-1,4
Up Type=0
Dn Type=3
Dn Slope=0.005
Boundary for River Rch & Prof#=UNT 02819 IN LAC,Reach-1,5
Up Type=0
Dn Type=3
Dn Slope=0.005
Boundary for River Rch & Prof#=UNT 02819 IN LAC,Reach-1,6
Up Type=0
Dn Type=3
Dn Slope=0.005
Boundary for River Rch & Prof#=UNT 02819 IN LAC,Reach-1,7
Up Type=0
Dn Type=3
Dn Slope=0.005

--- UNT 02819 IN LACR.g01 (geometry) ---

Geom Title=Existing Conditions

River Reach=UNT 02819 IN LAC,Reach-1
Reach XY= 30
      3658024.25     10626272.00      3658047.25     10626276.00
      3658086.75     10626234.00      3658134.50     10626212.00
      3658149.25     10626166.00      3658178.00     10626162.00
      3658205.25     10626174.00      3658247.25     10626225.00
      3658328.50     10626262.00      3658339.25     10626324.00
      3658445.50     10626363.00      3658476.00     10626435.00
      3658572.25     10626428.00      3658641.75     10626507.00
      3658666.00     10626513.00      3658711.25     10626494.00
      3658733.75     10626507.00      3658786.75     10626582.00
      3658804.00     10626634.00      3658827.50     10626653.00
      3658890.00     10626662.00      3658927.25     10626605.00
      3659128.75     10626639.00      3659412.50     10626762.00
      3659568.75     10626866.00      3659632.25     10626930.00
      3659823.50     10627080.00      3659979.75     10627167.00
      3660370.50     10627349.00      3660706.75     10627561.00

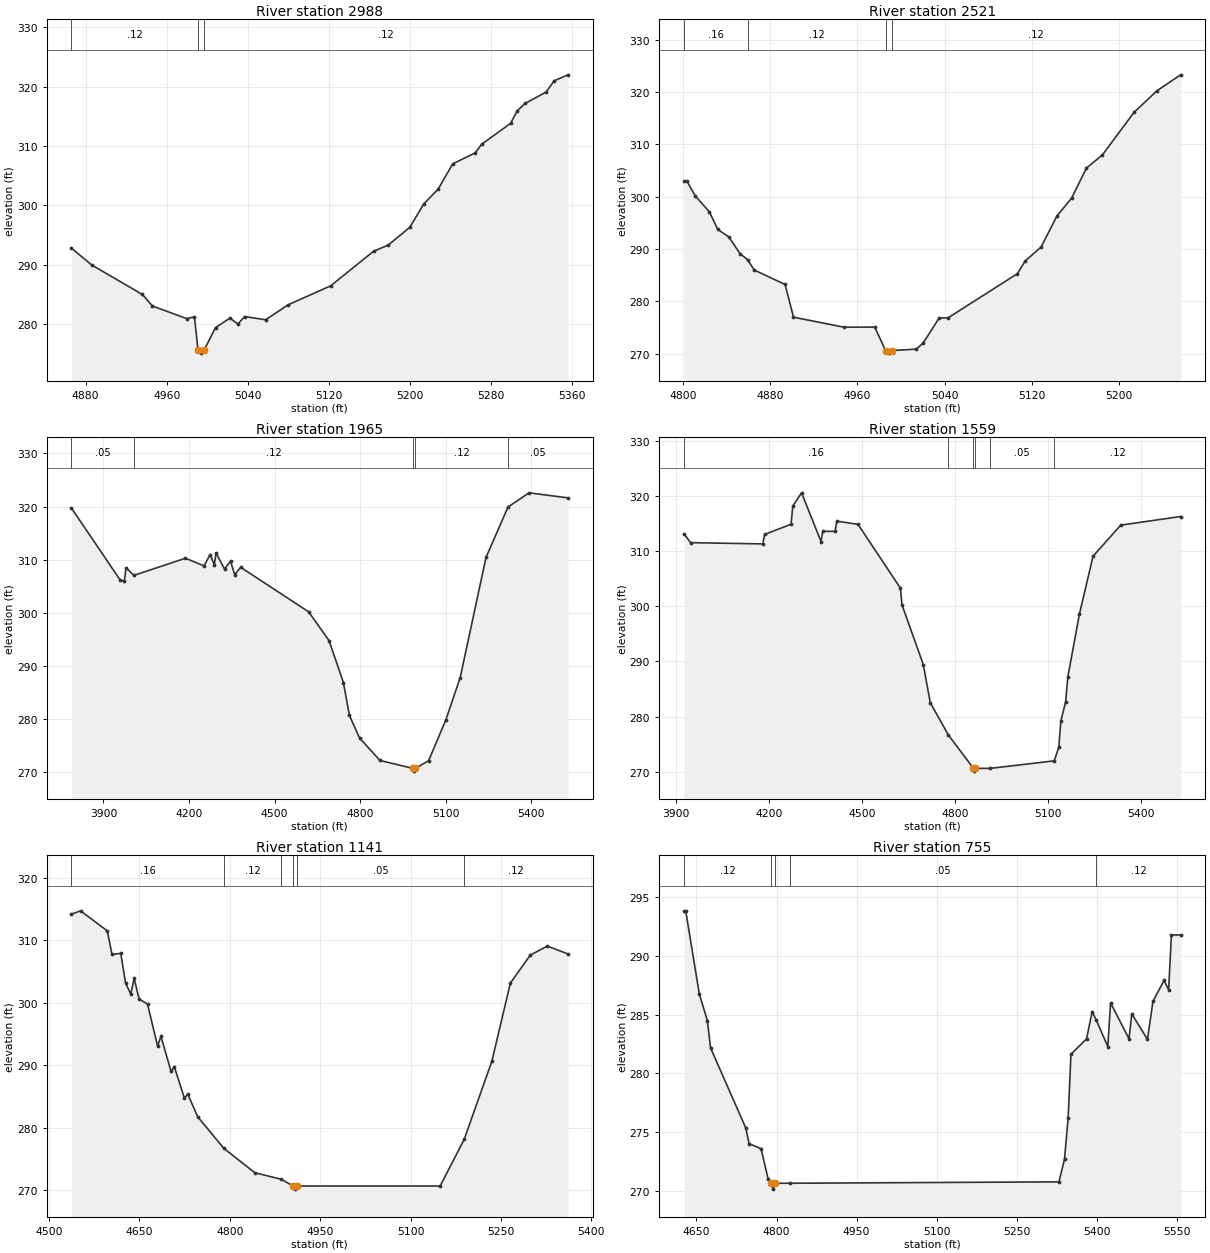
Type RM Length L Ch R = 1,2988,467,467,467
BEGIN DESCRIPTION:
UNT 02819 IN LACR 6.0
END DESCRIPTION:
XS GIS Cut Line= 3
      3658249.61     10626360.20      3658249.61     10626260.19
      3658549.59     10626010.21
#Sta/Elev= 30
  4866.0  292.76  4886.0  289.92  4936.0  284.95  4946.0  283.00  4979.7  280.88
  4987.5  281.15  4991.0  275.55  4993.8  275.05  4997.0  275.55  5008.3  279.36
  5022.6  280.96  5030.4  279.96  5037.0  281.22  5057.8  280.68  5079.9  283.19
  5122.2  286.42  5164.5  292.25  5178.8  293.26  5200.3  296.29  5214.0  300.22
  5228.3  302.74  5242.6  306.98  5264.8  308.84  5271.3  310.30  5299.9  313.84
  5306.4  315.95  5314.2  317.18  5335.0  319.12  5342.9  321.01  5356.5  322.01
#Mann=3,-1,0
  4866.0    0.12       0  4991.0    0.07       0  4997.0    0.12       0
Bank Sta=4991,4997
Exp/Cntr=0.3,0.1

Type RM Length L Ch R = 1,2521,556,556,556
BEGIN DESCRIPTION:
UNT 02819 IN LACR 5.0
END DESCRIPTION:
XS GIS Cut Line= 3
      3658549.61     10626660.19      3658599.61     10626460.19
      3658749.64     10626260.15
#Sta/Elev= 30
  4800.7  302.96  4803.3  302.96  4811.0  300.14  4823.9  297.13  4831.6  293.76
  4841.9  292.31  4852.2  289.10  4859.0  287.99  4865.1  286.00  4893.5  283.25
  4901.2  277.00  4947.6  275.09  4975.9  275.11  4985.8  270.64  4988.6  270.14
  4991.8  270.64  5014.1  270.90  5020.4  272.08  5035.0  276.82  5043.3  276.89
  5106.9  285.30  5114.1  287.73  5128.7  290.39  5143.3  296.32  5156.9  299.78
  5170.4  305.48  5185.0  307.96  5214.1  316.10  5235.0  320.20  5256.9  323.27
#Mann=4,-1,0
  4800.7    0.16       0  4859.0    0.12       0  4985.8    0.07       0
  4991.8    0.12       0
Bank Sta=4985.8,4991.8
Exp/Cntr=0.3,0.1

Type RM Length L Ch R = 1,1965,406,406,406
BEGIN DESCRIPTION:
UNT 02819 IN LACR 4.0
END DESCRIPTION:
XS GIS Cut Line= 3
      3658025.90     10627323.30      3659001.69     10626641.44
      3659064.03     10626094.70
#Sta/Elev= 30
  3788.0  319.69  3958.2  306.19  3973.1  305.88  3979.2  308.45  4006.8  307.03
  4187.6  310.25  4253.0  308.82  4274.0  310.95  4288.8  309.02  4294.9  311.25
  4324.6  308.21  4345.5  309.72  4360.3  307.15  4381.2  308.55  4619.3  300.16
  4690.9  294.75  4741.4  286.83  4762.4  280.65  4798.1  276.37  4869.7  272.15
  4986.7  270.64  4989.5  270.14  4992.7  270.64  5040.1  272.10  5100.5  279.79
  5150.8  287.76  5241.4  310.41  5318.4  319.90  5392.3  322.58  5528.7  321.63
#Mann=5,-1,0
  3788.0    0.05       0  4006.8    0.12       0  4986.7    0.07       0
  4992.7    0.12       0  5318.4    0.05       0
Bank Sta=4986.7,4992.7
Exp/Cntr=0.3,0.1

Type RM Length L Ch R = 1,1559,418,418,418
BEGIN DESCRIPTION:
UNT 02819 IN LACR 3.0
END DESCRIPTION:
XS GIS Cut Line= 2
      3658925.20     10627722.62      3659609.12     10626274.94
#Sta/Elev= 30
  3926.4  313.09  3947.1  311.51  4180.2  311.28  4185.8  312.99  4271.3  314.84
  4276.8  318.12  4305.1  320.53  4367.9  311.71  4373.4  313.55  4413.4  313.56
  4418.9  315.41  4487.2  314.82  4623.8  303.29  4629.4  300.18  4697.7  289.44
  4720.4  282.51  4778.5  276.69  4859.5  270.64  4862.3  270.14  4865.5  270.64
  4913.4  270.64  5119.9  272.00  5134.6  274.42  5141.3  279.19  5156.7  282.67
  5164.0  287.23  5201.0  298.52  5245.2  309.05  5334.4  314.68  5527.5  316.24
#Mann=6,-1,0
  3926.4    0.16       0  4778.5    0.12       0  4859.5   0.033       0
  4865.5    0.12       0  4913.4    0.05       0  5119.9    0.12       0
Bank Sta=4859.5,4865.5
Exp/Cntr=0.3,0.1

Type RM Length L Ch R = 1,1141,386,386,386
BEGIN DESCRIPTION:
UNT 02819 IN LACR 2.0
END DESCRIPTION:
XS GIS Cut Line= 3
      3659508.54     10627410.10      3659782.95     10626871.28
      3659827.99     10626656.63
#Sta/Elev= 30
  4537.2  314.19  4552.3  314.72  4596.7  311.50  4604.4  307.73  4619.0  307.91
  4626.9  303.16  4635.6  301.37  4641.2  303.92  4649.3  300.59  4663.4  299.78
  4680.1  293.06  4685.7  294.60  4702.3  289.04  4707.9  289.72  4724.6  284.72
  4730.2  285.35  4746.8  281.71  4790.2  276.66  4841.4  272.77  4885.0  271.73
  4905.1  270.64  4907.8  270.14  4911.1  270.64  5149.0  270.64  5188.9  278.09
  5234.9  290.63  5265.6  303.15  5298.7  307.63  5326.9  309.07  5361.2  307.81
#Mann=6,-1,0
  4537.2    0.16       0  4790.2    0.12       0  4885.0    0.05       0
  4905.1   0.033       0  4911.1    0.05       0  5188.9    0.12       0
Bank Sta=4905.1,4911.1
Exp/Cntr=0.3,0.1

Type RM Length L Ch R = 1,755,0,0,0
BEGIN DESCRIPTION:
UNT 02819 IN LACR 1.0
END DESCRIPTION:
XS GIS Cut Line= 3
      3659749.61     10627410.19      3660049.61     10627210.19
      3659899.62     10626660.23
#Sta/Elev= 30
  4626.8  293.85  4629.8  293.85  4655.3  286.77  4670.4  284.49  4676.4  282.17
  4742.5  275.34  4748.5  274.02  4771.0  273.59  4784.5  270.97  4790.6  270.64
  4793.3  270.14  4796.6  270.64  4824.5  270.64  5329.4  270.76  5339.8  272.69
  5346.7  276.23  5351.9  281.63  5381.2  282.95  5391.6  285.25  5399.6  284.51
  5421.0  282.28  5426.1  286.01  5460.7  282.95  5465.9  285.07  5495.3  282.90
  5505.6  286.13  5526.3  287.92  5535.0  287.13  5540.2  291.80  5557.4  291.79
#Mann=5,-1,0
  4626.8    0.12       0  4790.6   0.033       0  4796.6    0.12       0
  4824.5    0.05       0  5399.6    0.12       0
Bank Sta=4790.6,4796.6
Exp/Cntr=0.3,0.1

Chan Stop Cuts=-1