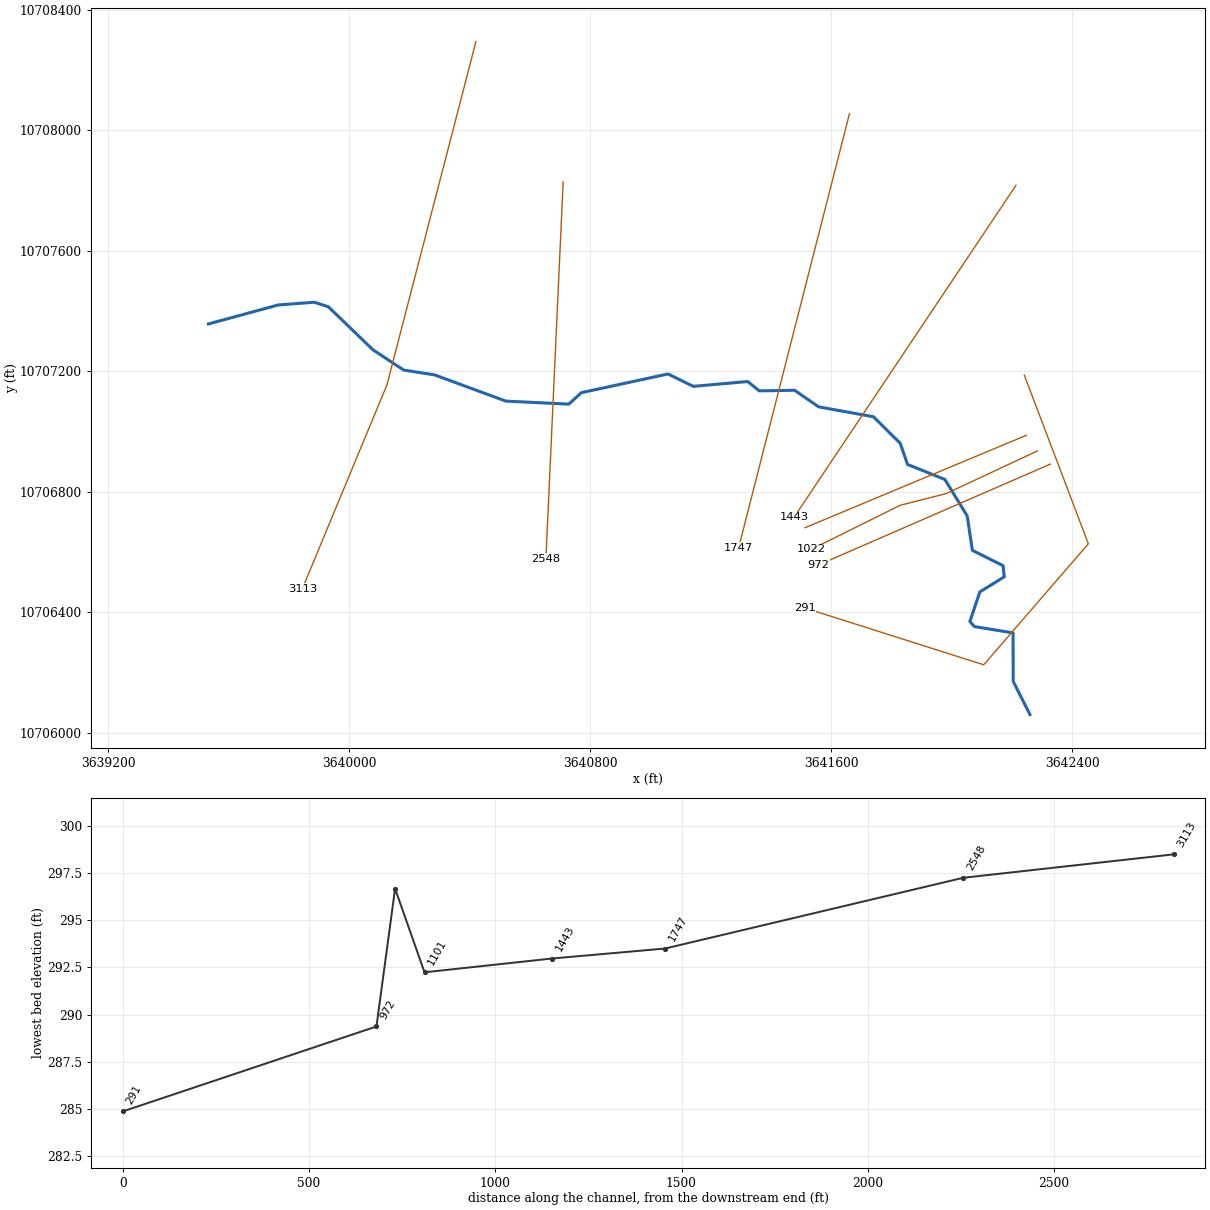
--- UNT 0292 IN LACR.prj (project) ---

Proj Title=UNT 0292 IN LACR Base Level Engineering
Current Plan=p01
Default Exp/Contr=0.3,0.1
English Units
Geom File=g01
Flow File=f01
Plan File=p01
BEGIN DESCRIPTION:
UNT 0292 IN LACR
END DESCRIPTION:

--- UNT 0292 IN LACR.p01 (plan) ---

Plan Title=Multiple Run
Short Identifier=Multiple
Geom File=g01
Flow File=f01
Subcritical Flow
K Sum by GR= 0
Std Step Tol= 0.01
Critical Tol= 0.01
Num of Std Step Trials= 20
Max Error Tol= 0.3
Flow Tol Ratio= 0.001
Split Flow NTrial= 30
Split Flow Tol= 0.02
Split Flow Ratio= 0.02
Log Output Level= 0
Friction Slope Method= 1
Unsteady Friction Slope Method= 2
Unsteady Bridges Friction Slope Method= 1
Parabolic Critical Depth
Global Vel Dist=  1 , 1 , 1
Global Log Level= 0
CheckData=True
Encroach Param= -1, 0, 0, 0
BEGIN DESCRIPTION:
Multiple Run
END DESCRIPTION:

--- UNT 0292 IN LACR.f01 (steady flow) ---

Flow Title=Multiple
Number of Profiles=7
Profile Names=10-year,25-year,50-year,1pct_min,100-year,1pct_plu,500-year
River Rch & RM= UNT 0292 IN LACR,Reach-1,3113
     507     649     757     645     872    1179    1154
Boundary for River Rch & Prof#=UNT 0292 IN LACR,Reach-1,1
Up Type=0
Dn Type=3
Dn Slope=0.005
Boundary for River Rch & Prof#=UNT 0292 IN LACR,Reach-1,2
Up Type=0
Dn Type=3
Dn Slope=0.005
Boundary for River Rch & Prof#=UNT 0292 IN LACR,Reach-1,3
Up Type=0
Dn Type=3
Dn Slope=0.005
Boundary for River Rch & Prof#=UNT 0292 IN LACR,Reach-1,4
Up Type=0
Dn Type=3
Dn Slope=0.005
Boundary for River Rch & Prof#=UNT 0292 IN LACR,Reach-1,5
Up Type=0
Dn Type=3
Dn Slope=0.005
Boundary for River Rch & Prof#=UNT 0292 IN LACR,Reach-1,6
Up Type=0
Dn Type=3
Dn Slope=0.005
Boundary for River Rch & Prof#=UNT 0292 IN LACR,Reach-1,7
Up Type=0
Dn Type=3
Dn Slope=0.005

--- UNT 0292 IN LACR.g01 (geometry) ---

Geom Title=Existing Conditions

River Reach=UNT 0292 IN LACR,Reach-1
Reach XY= 30
      3639532.69     10707357.00      3639764.75     10707420.00
      3639884.25     10707429.00      3639931.00     10707414.00
      3640079.25     10707271.00      3640181.00     10707204.00
      3640283.50     10707188.00      3640520.00     10707101.00
      3640729.00     10707091.00      3640770.75     10707129.00
      3641058.25     10707191.00      3641142.25     10707150.00
      3641322.75     10707166.00      3641361.00     10707135.00
      3641478.25     10707137.00      3641558.00     10707082.00
      3641740.25     10707049.00      3641829.00     10706961.00
      3641853.25     10706891.00      3641977.25     10706841.00
      3642051.25     10706720.00      3642068.50     10706606.00
      3642170.25     10706555.00      3642174.25     10706518.00
      3642093.25     10706468.00      3642060.25     10706370.00
      3642075.25     10706353.00      3642203.50     10706332.00
      3642204.00     10706171.00      3642259.50     10706061.00

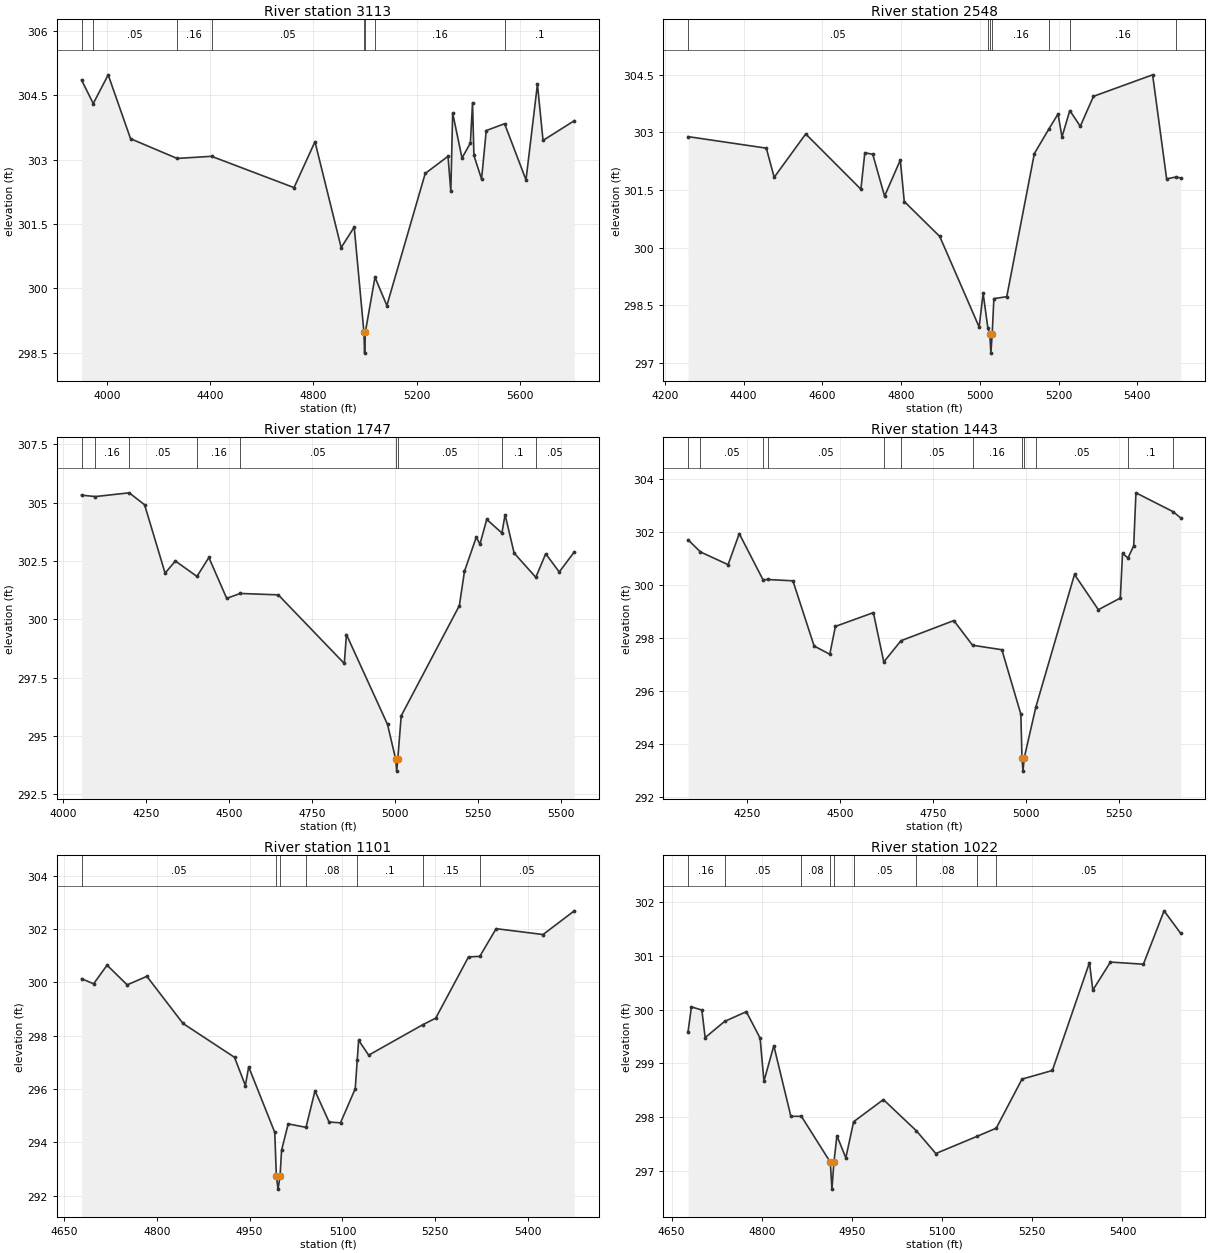
Type RM Length L Ch R = 1,3113,565,565,565
BEGIN DESCRIPTION:
UNT 0292 IN LACR 4.0
END DESCRIPTION:
XS GIS Cut Line= 3
      3640420.81     10708293.96      3640125.38     10707154.75
      3639844.52     10706478.23
#Sta/Elev= 30
  3901.6  304.86  3946.9  304.31  4004.8  304.98  4091.5  303.49  4271.9  303.03
  4405.2  303.08  4724.9  302.35  4806.1  303.42  4907.6  300.95  4958.1  301.43
  4995.6  298.99  4998.4  298.49  5001.6  298.99  5038.6  300.26  5084.7  299.60
  5233.3  302.68  5321.6  303.08  5332.5  302.26  5339.6  304.09  5375.8  303.04
  5408.3  303.39  5416.6  304.33  5422.0  303.10  5451.6  302.55  5469.8  303.68
  5540.8  303.84  5623.8  302.53  5668.1  304.76  5689.8  303.45  5811.0  303.91
#Mann=8,-1,0
  3901.6    0.16       0  3946.9    0.05       0  4271.9    0.16       0
  4405.2    0.05       0  4995.6    0.03       0  5001.6    0.05       0
  5038.6    0.16       0  5540.8     0.1       0
Bank Sta=4995.6,5001.6
Exp/Cntr=0.3,0.1

Type RM Length L Ch R = 1,2548,801,801,801
BEGIN DESCRIPTION:
UNT 0292 IN LACR 3.0
END DESCRIPTION:
XS GIS Cut Line= 2
      3640710.28     10707828.76      3640652.99     10706578.77
#Sta/Elev= 30
  4258.8  302.89  4457.6  302.59  4477.6  301.83  4557.7  302.96  4697.8  301.52
  4707.8  302.47  4727.9  302.43  4757.9  301.34  4797.9  302.28  4807.9  301.20
  4898.0  300.29  4998.1  297.93  5008.2  298.81  5020.3  297.90  5025.2  297.75
  5027.9  297.25  5031.2  297.75  5035.5  298.67  5068.2  298.72  5138.3  302.45
  5174.6  303.08  5198.4  303.48  5208.4  302.88  5228.3  303.57  5254.9  303.16
  5288.4  303.94  5438.6  304.50  5474.2  301.79  5499.0  301.84  5510.1  301.81
#Mann=7,-1,0
  4258.8    0.05       0  5020.3    0.16       0  5025.2    0.03       0
  5031.2    0.16       0  5174.6    0.05       0  5228.3    0.16       0
  5499.0    0.12       0
Bank Sta=5025.2,5031.2
Exp/Cntr=0.3,0.1

Type RM Length L Ch R = 1,1747,304,304,304
BEGIN DESCRIPTION:
UNT 0292 IN LACR 2.0
END DESCRIPTION:
XS GIS Cut Line= 2
      3641660.40     10708054.38      3641292.57     10706614.31
#Sta/Elev= 30
  4054.9  305.32  4096.4  305.26  4198.6  305.42  4245.0  304.91  4306.9  301.98
  4337.9  302.50  4403.0  301.84  4438.9  302.65  4492.7  300.90  4533.5  301.11
  4648.3  301.05  4847.4  298.11  4853.9  299.35  4977.8  295.50  5002.6  294.00
  5005.4  293.50  5008.6  294.00  5019.1  295.87  5194.5  300.59  5209.9  302.06
  5245.5  303.52  5256.5  303.22  5277.1  304.28  5322.8  303.70  5332.4  304.48
  5359.7  302.84  5425.1  301.80  5454.9  302.81  5495.8  302.03  5541.2  302.89
#Mann=9,-1,0
  4054.9    0.05       0  4096.4    0.16       0  4198.6    0.05       0
  4403.0    0.16       0  4533.5    0.05       0  5002.6    0.03       0
  5008.6    0.05       0  5322.8     0.1       0  5425.1    0.05       0
Bank Sta=5002.6,5008.6
Exp/Cntr=0.3,0.1

Type RM Length L Ch R = 1,1443,342,342,342
BEGIN DESCRIPTION:
Mapping XS 80d73561
END DESCRIPTION:
XS GIS Cut Line= 2
      3642213.09     10707816.82      3641476.95     10706716.09
#Sta/Elev= 30
  4091.1  301.70  4124.4  301.24  4198.8  300.76  4228.8  301.93  4292.6  300.19
  4304.7  300.20  4373.0  300.15  4430.0  297.69  4472.1  297.38  4487.1  298.43
  4589.2  298.95  4617.2  297.09  4663.4  297.89  4805.4  298.65  4855.7  297.72
  4934.5  297.55  4985.5  295.12  4988.6  293.47  4991.3  292.97  4994.6  293.47
  5025.9  295.39  5129.7  300.39  5193.8  299.06  5252.8  299.50  5258.8  301.19
  5273.4  301.01  5288.8  301.47  5294.8  303.47  5394.5  302.76  5415.3  302.52
#Mann=12,-1,0
  4091.1    0.16       0  4124.4    0.05       0  4292.6    0.16       0
  4304.7    0.05       0  4617.2    0.08       0  4663.4    0.05       0
  4855.7    0.16       0  4988.6    0.07       0  4994.6    0.16       0
  5025.9    0.05       0  5273.4     0.1       0  5394.5    0.05       0
Bank Sta=4988.6,4994.6
Exp/Cntr=0.3,0.1

Type RM Length L Ch R = 1,1101,79,79,79
BEGIN DESCRIPTION:
Mapping XS c69713b9
END DESCRIPTION:
XS GIS Cut Line= 2
      3642247.60     10706987.63      3641513.04     10706680.98
#Sta/Elev= 30
  4678.5  300.14  4698.0  299.95  4719.7  300.65  4752.2  299.91  4784.0  300.23
  4842.4  298.46  4925.6  297.19  4943.1  296.13  4948.5  296.83  4990.6  294.37
  4993.2  292.74  4995.9  292.24  4999.2  292.74  5001.6  293.70  5012.3  294.69
  5041.1  294.56  5055.6  295.93  5078.4  294.76  5096.8  294.73  5120.6  296.01
  5123.8  297.07  5126.1  297.83  5142.3  297.27  5229.4  298.41  5250.6  298.66
  5303.6  300.96  5321.8  300.98  5348.2  302.02  5424.0  301.80  5474.5  302.69
#Mann=7,-1,0
  4678.5    0.05       0  4993.2    0.03       0  4999.2    0.05       0
  5041.1    0.08       0  5123.8     0.1       0  5229.4    0.15       0
  5321.8    0.05       0
Bank Sta=4993.2,4999.2
Exp/Cntr=0.3,0.1

Type RM Length L Ch R = 1,1022,50,50,50
BEGIN DESCRIPTION:
Mapping XS 6f81b847
END DESCRIPTION:
XS GIS Cut Line= 4
      3642284.05     10706935.54      3641981.29     10706794.14
      3641829.20     10706755.46      3641534.73     10706609.61
#Sta/Elev= 30
  4677.3  299.58  4682.9  300.05  4700.3  299.99  4705.8  299.48  4738.2  299.78
  4774.3  299.96  4797.2  299.47  4803.6  298.67  4820.0  299.33  4848.4  298.02
  4865.9  298.02  4914.0  297.17  4916.7  296.67  4920.0  297.17  4925.0  297.66
  4939.8  297.25  4952.8  297.92  5002.3  298.33  5057.3  297.75  5089.5  297.33
  5158.4  297.65  5190.0  297.80  5232.9  298.71  5283.4  298.87  5345.1  300.87
  5350.7  300.36  5380.0  300.88  5434.8  300.84  5469.2  301.83  5497.0  301.41
#Mann=9,-1,0
  4677.3    0.16       0  4738.2    0.05       0  4865.9    0.08       0
  4914.0    0.04       0  4920.0    0.08       0  4952.8    0.05       0
  5057.3    0.08       0  5158.4     0.1       0  5190.0    0.05       0
Bank Sta=4914,4920
Exp/Cntr=0.3,0.1

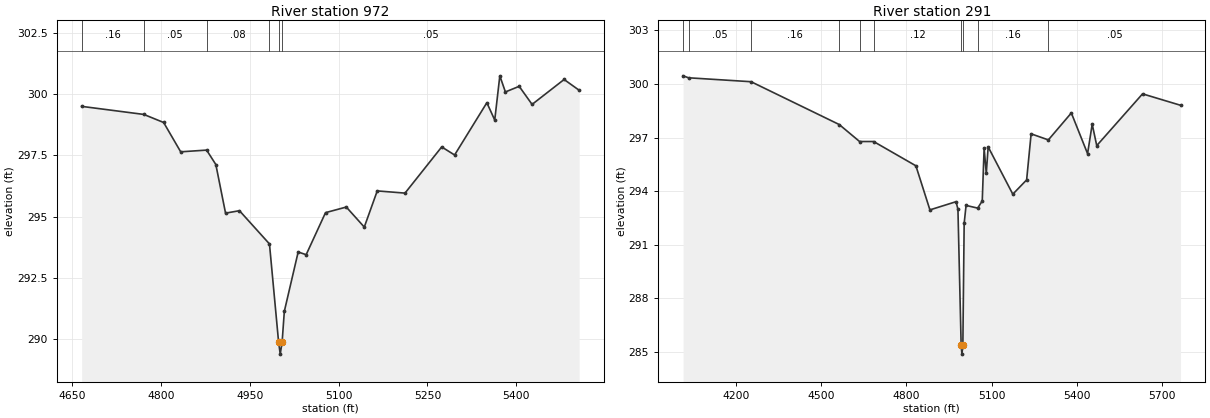
Type RM Length L Ch R = 1,972,681,681,681
BEGIN DESCRIPTION:
Mapping XS 26f98999
END DESCRIPTION:
XS GIS Cut Line= 2
      3642327.50     10706892.16      3641556.67     10706557.09
#Sta/Elev= 30
  4665.8  299.51  4770.8  299.18  4804.3  298.85  4833.1  297.65  4876.9  297.72
  4892.5  297.13  4908.9  295.14  4932.4  295.24  4983.1  293.88  4998.5  289.87
  5001.3  289.37  5004.5  289.87  5008.2  291.12  5031.6  293.55  5045.1  293.44
  5077.8  295.16  5112.9  295.39  5143.3  294.57  5165.2  296.05  5212.1  295.96
  5274.1  297.85  5295.9  297.52  5350.4  299.66  5363.7  298.95  5372.3  300.76
  5381.7  300.10  5405.0  300.33  5426.8  299.59  5480.9  300.61  5506.3  300.17
#Mann=6,-1,0
  4665.8    0.16       0  4770.8    0.05       0  4876.9    0.08       0
  4983.1    0.05       0  4998.5    0.04       0  5004.5    0.05       0
Bank Sta=4998.5,5004.5
Exp/Cntr=0.3,0.1

Type RM Length L Ch R = 1,291,0,0,0
BEGIN DESCRIPTION:
UNT 0292 IN LACR 1.0
END DESCRIPTION:
XS GIS Cut Line= 4
      3642240.68     10707187.46      3642453.34     10706627.61
      3642106.11     10706226.13      3641513.07     10706414.43
#Sta/Elev= 30
  4013.6  300.46  4033.0  300.35  4253.1  300.13  4563.7  297.73  4635.2  296.78
  4684.6  296.78  4833.5  295.42  4882.9  292.95  4975.0  293.41  4981.6  292.98
  4992.9  285.37  4995.6  284.87  4998.9  285.37  5003.5  292.19  5010.2  293.20
  5051.1  293.05  5067.2  293.45  5073.8  296.41  5081.4  294.99  5088.0  296.48
  5174.8  293.83  5223.5  294.63  5239.3  297.21  5300.0  296.87  5380.9  298.38
  5438.1  296.10  5454.4  297.75  5470.4  296.55  5631.7  299.45  5765.5  298.81
#Mann=10,-1,0
  4013.6     0.1       0  4033.0    0.05       0  4253.1    0.16       0
  4563.7    0.12       0  4635.2    0.16       0  4684.6    0.12       0
  4992.9    0.07       0  4998.9    0.12       0  5051.1    0.16       0
  5300.0    0.05       0
Bank Sta=4992.9,4998.9
Exp/Cntr=0.3,0.1

Chan Stop Cuts=-1