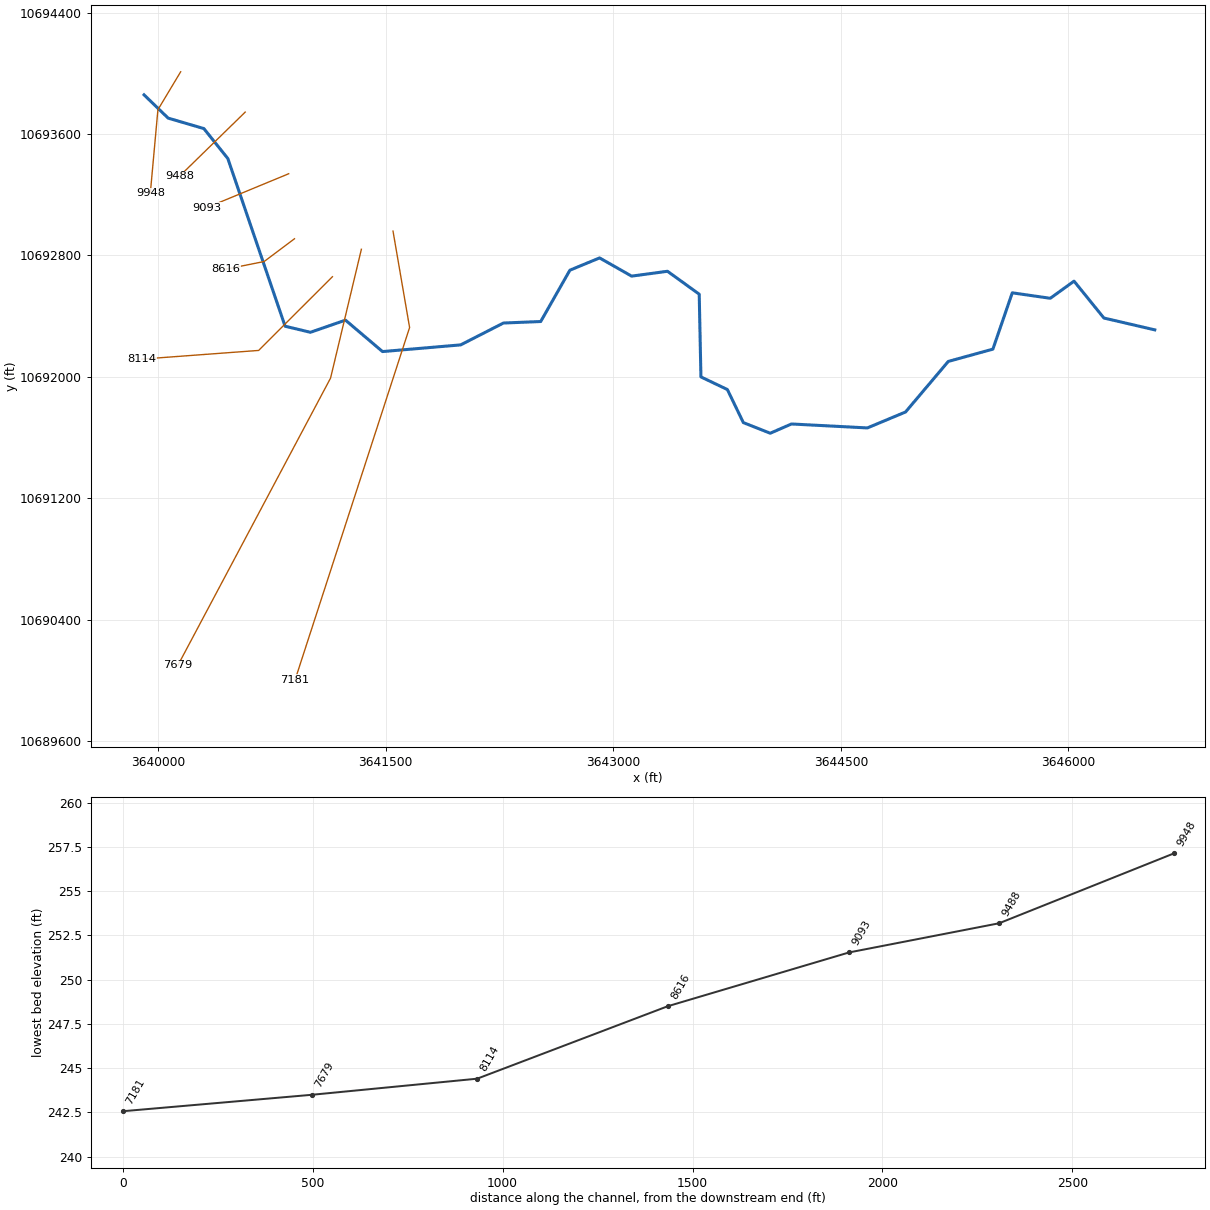
--- UNT 0293 IN LACR.prj (project) ---

Proj Title=UNT 0293 IN LACR Base Level Engineering
Current Plan=p01
Default Exp/Contr=0.3,0.1
English Units
Geom File=g01
Flow File=f01
Plan File=p01
BEGIN DESCRIPTION:
UNT 0293 IN LACR
END DESCRIPTION:

--- UNT 0293 IN LACR.p01 (plan) ---

Plan Title=Multiple Run
Short Identifier=Multiple
Geom File=g01
Flow File=f01
Subcritical Flow
K Sum by GR= 0
Std Step Tol= 0.01
Critical Tol= 0.01
Num of Std Step Trials= 20
Max Error Tol= 0.3
Flow Tol Ratio= 0.001
Split Flow NTrial= 30
Split Flow Tol= 0.02
Split Flow Ratio= 0.02
Log Output Level= 0
Friction Slope Method= 1
Unsteady Friction Slope Method= 2
Unsteady Bridges Friction Slope Method= 1
Parabolic Critical Depth
Global Vel Dist=  1 , 1 , 1
Global Log Level= 0
CheckData=True
Encroach Param= -1, 0, 0, 0
BEGIN DESCRIPTION:
Multiple Run
END DESCRIPTION:

--- UNT 0293 IN LACR.f01 (steady flow) ---

Flow Title=Multiple
Number of Profiles=7
Profile Names=10-year,25-year,50-year,1pct_min,100-year,1pct_plu,500-year
River Rch & RM= UNT 0293 IN LACR,Reach-1,9948
     661     870    1034     898    1214    1642    1668
Boundary for River Rch & Prof#=UNT 0293 IN LACR,Reach-1,1
Up Type=0
Dn Type=3
Dn Slope=0.005
Boundary for River Rch & Prof#=UNT 0293 IN LACR,Reach-1,2
Up Type=0
Dn Type=3
Dn Slope=0.005
Boundary for River Rch & Prof#=UNT 0293 IN LACR,Reach-1,3
Up Type=0
Dn Type=3
Dn Slope=0.005
Boundary for River Rch & Prof#=UNT 0293 IN LACR,Reach-1,4
Up Type=0
Dn Type=3
Dn Slope=0.005
Boundary for River Rch & Prof#=UNT 0293 IN LACR,Reach-1,5
Up Type=0
Dn Type=3
Dn Slope=0.005
Boundary for River Rch & Prof#=UNT 0293 IN LACR,Reach-1,6
Up Type=0
Dn Type=3
Dn Slope=0.005
Boundary for River Rch & Prof#=UNT 0293 IN LACR,Reach-1,7
Up Type=0
Dn Type=3
Dn Slope=0.005

--- UNT 0293 IN LACR.g01 (geometry) ---

Geom Title=Existing Conditions

River Reach=UNT 0293 IN LACR,Reach-1
Reach XY= 30
      3639908.29     10693858.29      3640067.00     10693705.00
      3640302.50     10693636.00      3640460.25     10693439.00
      3640837.75     10692334.00      3641004.50     10692294.00
      3641235.75     10692374.00      3641479.75     10692167.00
      3641994.75     10692211.00      3642276.50     10692355.00
      3642522.25     10692365.00      3642714.50     10692703.00
      3642910.25     10692784.00      3643121.25     10692664.00
      3643357.75     10692696.00      3643566.75     10692545.00
      3643578.00     10692000.00      3643752.25     10691917.00
      3643857.50     10691699.00      3644034.75     10691629.00
      3644174.75     10691690.00      3644674.75     10691664.00
      3644926.50     10691769.00      3645208.00     10692102.00
      3645502.00     10692183.00      3645629.75     10692554.00
      3645880.25     10692518.00      3646036.75     10692631.00
      3646233.50     10692388.00      3646568.75     10692310.00

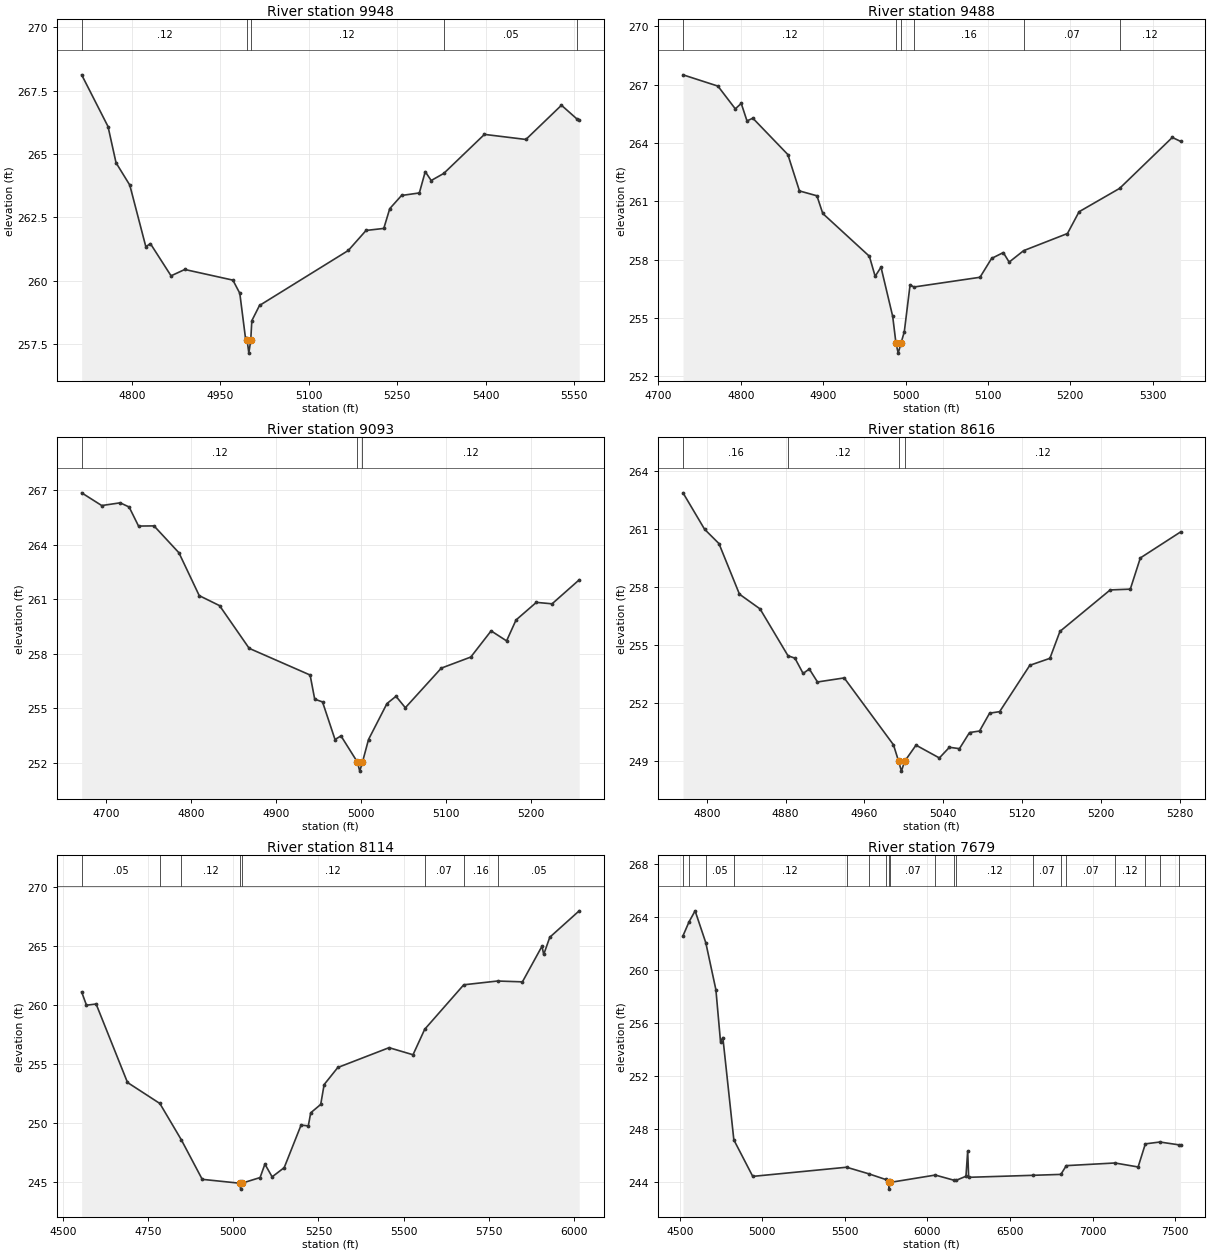
Type RM Length L Ch R = 1,9948,460,460,460
BEGIN DESCRIPTION:
UNT 0293 IN LACR 12.0
END DESCRIPTION:
XS GIS Cut Line= 3
      3640149.59     10694010.16      3639999.61     10693760.19
      3639949.61     10693210.17
#Sta/Elev= 30
  4714.6  268.12  4759.3  266.08  4772.9  264.65  4796.2  263.77  4823.4  261.34
  4831.2  261.46  4866.2  260.19  4889.5  260.44  4971.1  260.02  4982.8  259.50
  4992.5  257.72  4995.3  257.64  4998.1  257.14  5001.3  257.64  5003.2  258.42
  5016.2  259.02  5166.8  261.19  5196.9  261.98  5227.0  262.06  5237.1  262.84
  5257.1  263.36  5287.3  263.46  5297.3  264.30  5307.4  263.95  5328.7  264.23
  5397.7  265.77  5468.0  265.57  5528.3  266.92  5555.0  266.37  5558.4  266.35
#Mann=5,-1,0
  4714.6    0.12       0  4995.3    0.07       0  5001.3    0.12       0
  5328.7    0.05       0  5555.0    0.16       0
Bank Sta=4995.3,5001.3
Exp/Cntr=0.3,0.1

Type RM Length L Ch R = 1,9488,395,395,395
BEGIN DESCRIPTION:
UNT 0293 IN LACR 11.0
END DESCRIPTION:
XS GIS Cut Line= 2
      3640575.03     10693744.74      3640142.69     10693322.82
#Sta/Elev= 30
  4729.8  267.50  4772.2  266.92  4793.3  265.75  4800.5  266.03  4807.5  265.13
  4814.6  265.27  4857.1  263.40  4871.2  261.53  4892.4  261.28  4899.5  260.37
  4956.1  258.17  4963.1  257.14  4970.2  257.61  4984.4  255.08  4988.4  253.69
  4991.1  253.19  4994.4  253.69  4998.5  254.29  5005.5  256.70  5010.2  256.59
  5090.4  257.09  5104.5  258.06  5118.7  258.36  5125.8  257.87  5143.4  258.46
  5196.6  259.34  5210.7  260.46  5259.9  261.66  5323.9  264.28  5333.9  264.08
#Mann=6,-1,0
  4729.8    0.12       0  4988.4    0.07       0  4994.4    0.12       0
  5010.2    0.16       0  5143.4    0.07       0  5259.9    0.12       0
Bank Sta=4988.4,4994.4
Exp/Cntr=0.3,0.1

Type RM Length L Ch R = 1,9093,477,477,477
BEGIN DESCRIPTION:
UNT 0293 IN LACR 10.0
END DESCRIPTION:
XS GIS Cut Line= 2
      3640861.45     10693338.46      3640320.65     10693114.86
#Sta/Elev= 30
  4671.2  266.86  4694.8  266.16  4716.5  266.31  4727.0  266.08  4738.1  265.03
  4756.3  265.04  4785.6  263.56  4809.5  261.20  4833.4  260.65  4868.2  258.30
  4939.9  256.83  4945.3  255.50  4954.5  255.35  4969.2  253.28  4976.2  253.48
  4995.5  252.04  4998.3  251.54  5001.5  252.04  5008.6  253.28  5030.3  255.26
  5040.9  255.66  5051.9  255.03  5094.2  257.21  5128.9  257.82  5152.8  259.26
  5171.0  258.71  5182.1  259.86  5206.0  260.83  5224.5  260.75  5256.4  262.07
#Mann=3,-1,0
  4671.2    0.12       0  4995.5    0.07       0  5001.5    0.12       0
Bank Sta=4995.5,5001.5
Exp/Cntr=0.3,0.1

Type RM Length L Ch R = 1,8616,502,502,502
BEGIN DESCRIPTION:
UNT 0293 IN LACR 9.0
END DESCRIPTION:
XS GIS Cut Line= 3
      3640899.65     10692910.22      3640699.61     10692760.19
      3640449.61     10692710.19
#Sta/Elev= 30
  4775.9  262.86  4797.8  260.98  4812.4  260.24  4833.2  257.63  4854.1  256.87
  4882.5  254.45  4889.5  254.33  4897.8  253.54  4904.1  253.77  4912.4  253.10
  4939.5  253.31  4989.5  249.86  4994.8  249.00  4997.6  248.50  5000.8  249.00
  5012.4  249.84  5036.1  249.18  5046.3  249.73  5056.5  249.66  5066.7  250.49
  5076.9  250.57  5087.1  251.49  5097.3  251.57  5127.9  253.96  5148.3  254.32
  5158.5  255.71  5209.5  257.85  5229.9  257.89  5240.1  259.50  5280.9  260.84
#Mann=4,-1,0
  4775.9    0.16       0  4882.5    0.12       0  4994.8    0.07       0
  5000.8    0.12       0
Bank Sta=4994.8,5000.8
Exp/Cntr=0.3,0.1

Type RM Length L Ch R = 1,8114,435,435,435
BEGIN DESCRIPTION:
UNT 0293 IN LACR 8.0
END DESCRIPTION:
XS GIS Cut Line= 3
      3641149.61     10692660.19      3640663.42     10692174.49
      3639893.57     10692117.27
#Sta/Elev= 30
  4555.5  261.11  4569.6  259.99  4597.9  260.09  4689.9  253.44  4784.8  251.66
  4847.8  248.58  4909.1  245.23  5019.2  244.90  5021.9  244.40  5025.2  244.90
  5078.8  245.38  5092.9  246.52  5114.1  245.44  5149.5  246.22  5199.0  249.83
  5220.2  249.76  5227.3  250.87  5256.6  251.58  5266.6  253.26  5306.7  254.71
  5457.1  256.39  5527.3  255.79  5561.6  257.95  5676.1  261.72  5775.1  262.04
  5848.2  261.97  5905.6  264.99  5910.6  264.29  5928.4  265.75  6014.7  267.99
#Mann=8,-1,0
  4555.5    0.05       0  4784.8    0.16       0  4847.8    0.12       0
  5019.2    0.07       0  5025.2    0.12       0  5561.6    0.07       0
  5676.1    0.16       0  5775.1    0.05       0
Bank Sta=5019.2,5025.2
Exp/Cntr=0.3,0.1

Type RM Length L Ch R = 1,7679,498,498,498
BEGIN DESCRIPTION:
UNT 0293 IN LACR 7.0
END DESCRIPTION:
XS GIS Cut Line= 3
      3641340.49     10692841.11      3641137.37     10691992.20
      3640132.17     10690101.59
#Sta/Elev= 30
  4519.0  262.58  4555.5  263.63  4592.2  264.46  4657.2  262.05  4718.3  258.51
  4746.2  254.60  4760.4  254.91  4827.0  247.20  4941.5  244.45  5510.1  245.14
  5643.0  244.65  5745.9  244.22  5764.9  243.99  5767.6  243.49  5770.9  243.99
  6047.3  244.55  6160.7  244.16  6175.1  244.16  6233.2  244.46  6243.6  246.36
  6249.5  244.38  6636.5  244.53  6808.1  244.60  6841.0  245.26  7135.9  245.46
  7276.1  245.16  7319.9  246.90  7408.0  247.04  7521.3  246.83  7533.1  246.78
#Mann=19,-1,0
  4519.0    0.12       0  4555.5    0.07       0  4657.2    0.05       0
  4827.0    0.12       0  5510.1    0.07       0  5643.0    0.12       0
  5745.9    0.07       0  5764.9    0.07       0  5770.9    0.07       0
  6047.3    0.12       0  6160.7    0.07       0  6175.1    0.12       0
  6636.5    0.07       0  6808.1    0.12       0  6841.0    0.07       0
  7135.9    0.12       0  7319.9    0.07       0  7408.0    0.12       0
  7521.3    0.07       0
Bank Sta=5764.9,5770.9
Exp/Cntr=0.3,0.1

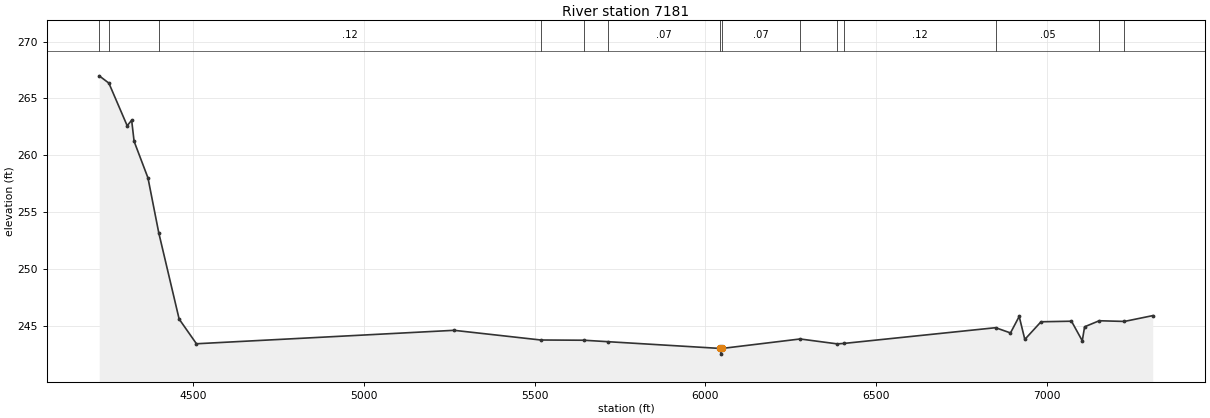
Type RM Length L Ch R = 1,7181,0,0,0
BEGIN DESCRIPTION:
UNT 0293 IN LACR 6.0
END DESCRIPTION:
XS GIS Cut Line= 3
      3641548.84     10692960.90      3641658.21     10692325.53
      3640903.41     10690003.86
#Sta/Elev= 30
  4224.1  266.99  4252.4  266.35  4306.0  262.61  4319.1  263.09  4326.3  261.24
  4366.9  258.03  4398.6  253.20  4458.2  245.64  4508.9  243.47  5263.4  244.65
  5517.5  243.80  5643.4  243.78  5715.4  243.65  6042.8  243.06  6045.6  242.56
  6048.8  243.06  6277.2  243.89  6385.9  243.46  6405.8  243.50  6849.9  244.88
  6893.4  244.42  6918.9  245.87  6935.4  243.85  6982.8  245.40  7072.1  245.45
  7103.7  243.73  7110.5  244.96  7153.3  245.49  7227.1  245.43  7310.1  245.94
#Mann=14,-1,0
  4224.1    0.16       0  4252.4    0.05       0  4398.6    0.12       0
  5517.5    0.07       0  5643.4    0.12       0  5715.4    0.07       0
  6042.8    0.07       0  6048.8    0.07       0  6277.2    0.12       0
  6385.9    0.07       0  6405.8    0.12       0  6849.9    0.05       0
  7153.3    0.07       0  7227.1    0.05       0
Bank Sta=6042.8,6048.8
Exp/Cntr=0.3,0.1

Chan Stop Cuts=-1