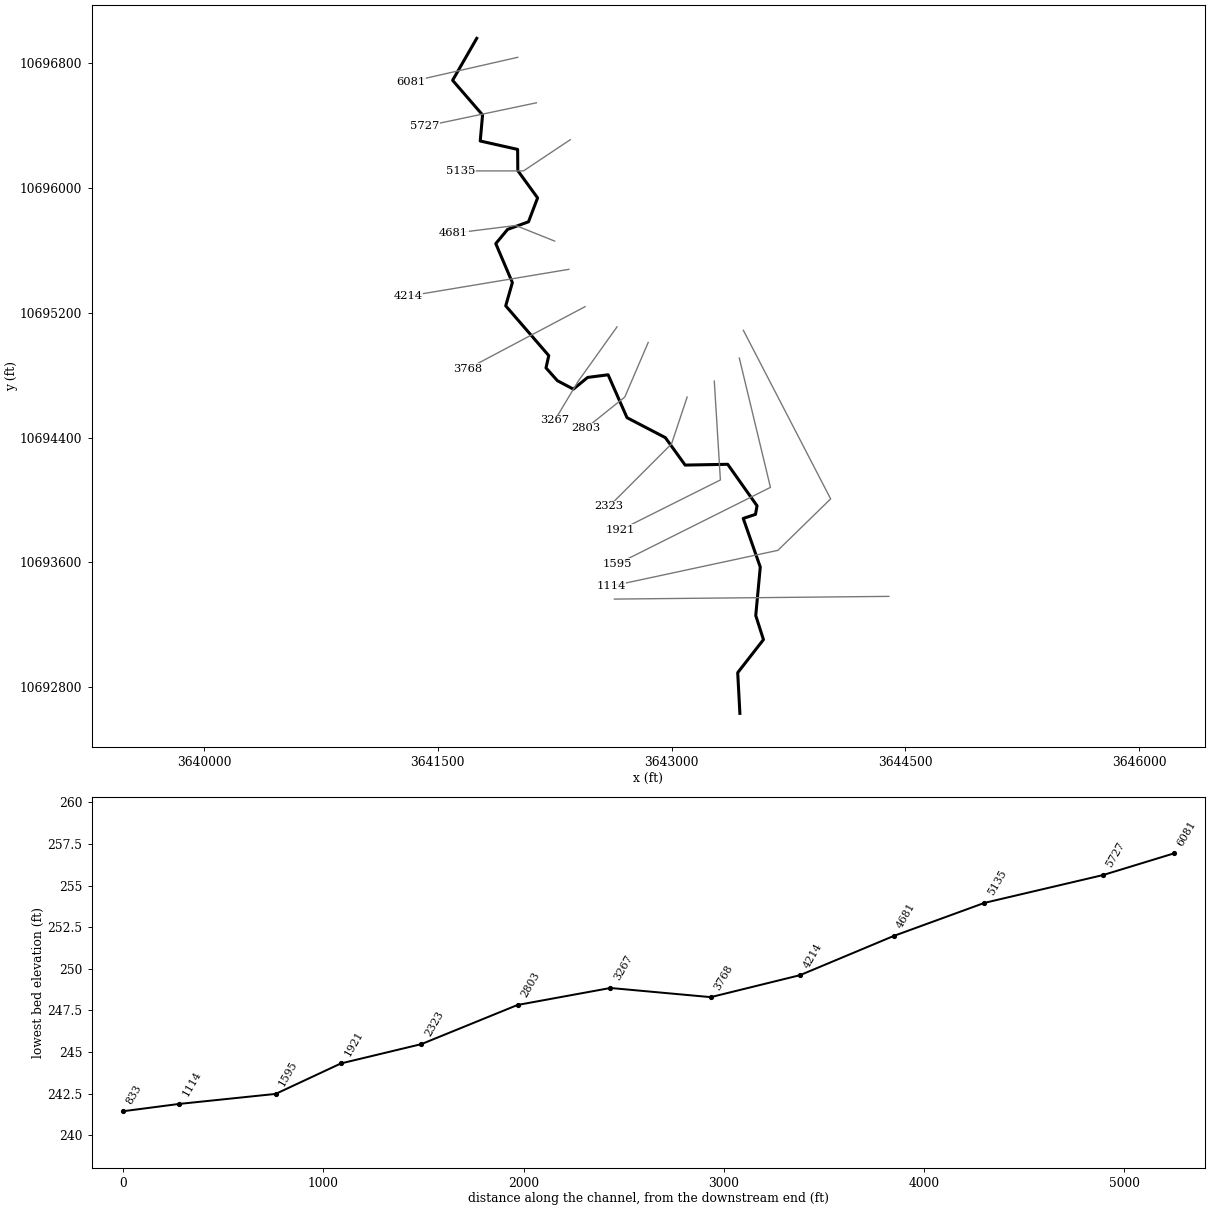
--- UNT 0294 IN LACR.prj (project) ---

Proj Title=UNT 0294 IN LACR Base Level Engineering
Current Plan=p01
Default Exp/Contr=0.3,0.1
English Units
Geom File=g01
Flow File=f01
Plan File=p01
BEGIN DESCRIPTION:
UNT 0294 IN LACR
END DESCRIPTION:

--- UNT 0294 IN LACR.p01 (plan) ---

Plan Title=Multiple Run
Short Identifier=Multiple
Geom File=g01
Flow File=f01
Subcritical Flow
K Sum by GR= 0
Std Step Tol= 0.01
Critical Tol= 0.01
Num of Std Step Trials= 20
Max Error Tol= 0.3
Flow Tol Ratio= 0.001
Split Flow NTrial= 30
Split Flow Tol= 0.02
Split Flow Ratio= 0.02
Log Output Level= 0
Friction Slope Method= 1
Unsteady Friction Slope Method= 2
Unsteady Bridges Friction Slope Method= 1
Parabolic Critical Depth
Global Vel Dist=  1 , 1 , 1
Global Log Level= 0
CheckData=True
Encroach Param= -1, 0, 0, 0
BEGIN DESCRIPTION:
Multiple Run
END DESCRIPTION:

--- UNT 0294 IN LACR.f01 (steady flow) ---

Flow Title=Multiple
Number of Profiles=7
Profile Names=10-year,25-year,50-year,1pct_min,100-year,1pct_plu,500-year
River Rch & RM= UNT 0294 IN LACR,Reach-1,6081
     456     599     711     620     839    1134    1167
Boundary for River Rch & Prof#=UNT 0294 IN LACR,Reach-1,1
Up Type=0
Dn Type=3
Dn Slope=0.005
Boundary for River Rch & Prof#=UNT 0294 IN LACR,Reach-1,2
Up Type=0
Dn Type=3
Dn Slope=0.005
Boundary for River Rch & Prof#=UNT 0294 IN LACR,Reach-1,3
Up Type=0
Dn Type=3
Dn Slope=0.005
Boundary for River Rch & Prof#=UNT 0294 IN LACR,Reach-1,4
Up Type=0
Dn Type=3
Dn Slope=0.005
Boundary for River Rch & Prof#=UNT 0294 IN LACR,Reach-1,5
Up Type=0
Dn Type=3
Dn Slope=0.005
Boundary for River Rch & Prof#=UNT 0294 IN LACR,Reach-1,6
Up Type=0
Dn Type=3
Dn Slope=0.005
Boundary for River Rch & Prof#=UNT 0294 IN LACR,Reach-1,7
Up Type=0
Dn Type=3
Dn Slope=0.005

--- UNT 0294 IN LACR.g01 (geometry) ---

Geom Title=Existing Conditions

River Reach=UNT 0294 IN LACR,Reach-1
Reach XY= 30
      3641749.61     10696960.19      3641594.75     10696691.00
      3641787.00     10696469.00      3641772.00     10696302.00
      3642012.00     10696248.00      3642013.00     10696112.00
      3642140.00     10695937.00      3642081.75     10695784.00
      3641947.50     10695735.00      3641871.75     10695644.00
      3641978.25     10695394.00      3641935.50     10695245.00
      3642211.75     10694926.00      3642194.00     10694847.00
      3642267.25     10694765.00      3642369.50     10694711.00
      3642461.00     10694786.00      3642592.50     10694803.00
      3642713.75     10694528.00      3642959.75     10694400.00
      3643086.75     10694224.00      3643359.75     10694229.00
      3643548.00     10693963.00      3643538.25     10693908.00
      3643459.50     10693882.00      3643568.75     10693570.00
      3643539.75     10693259.00      3643589.25     10693105.00
      3643424.00     10692893.00      3643438.00     10692632.00

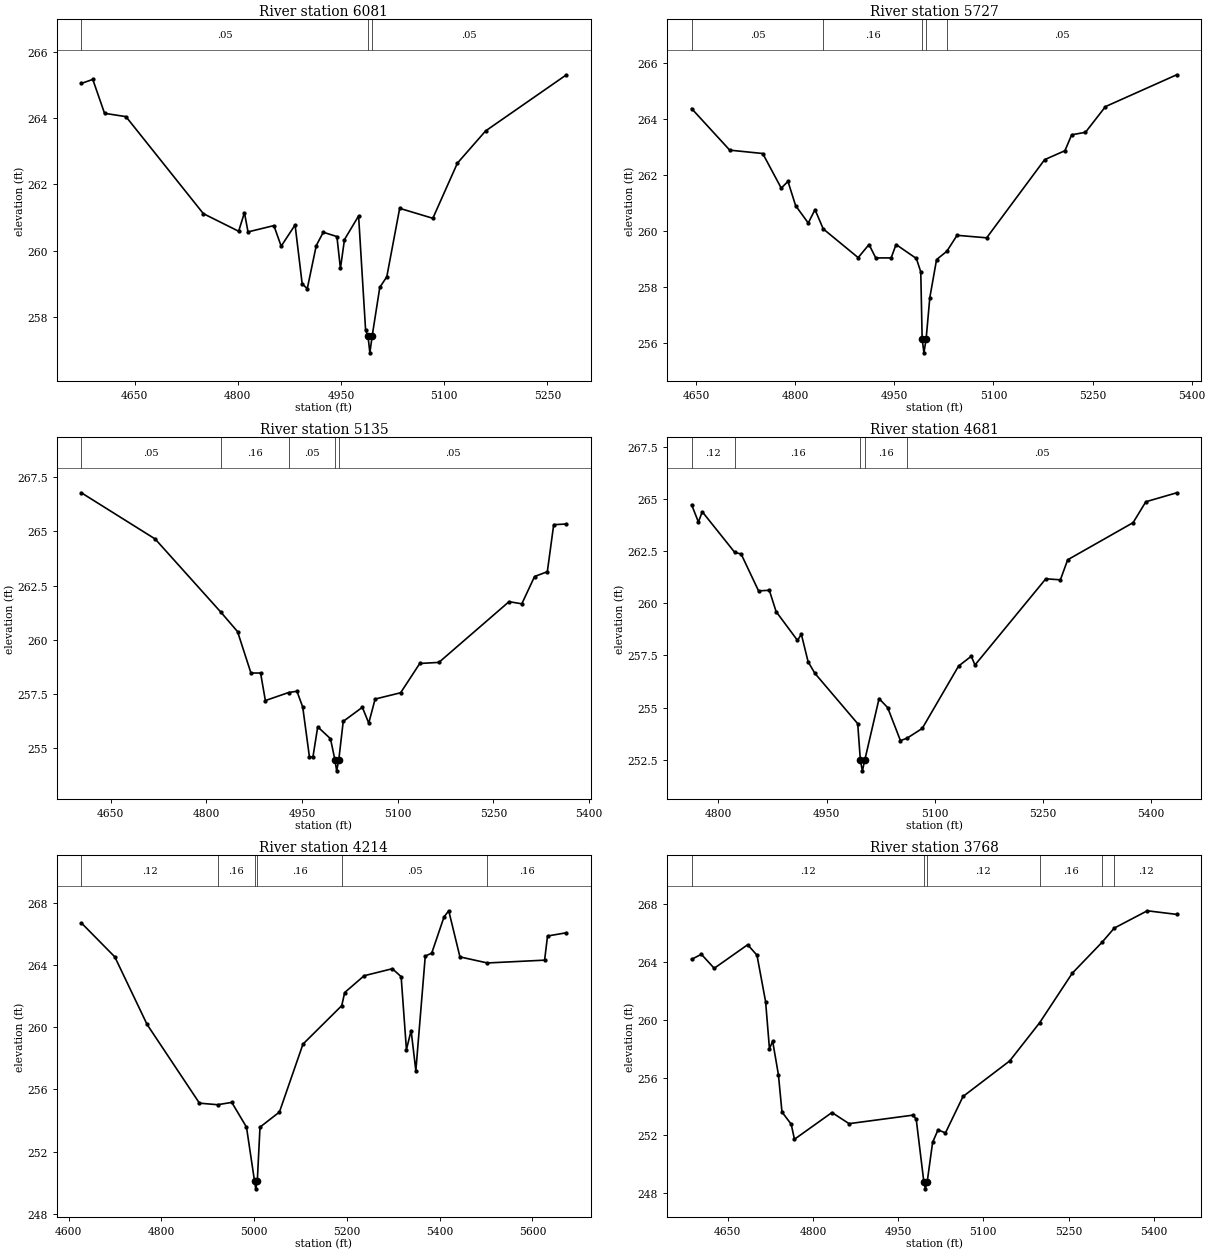
Type RM Length L Ch R = 1,6081,354,354,354
BEGIN DESCRIPTION:
UNT 0294 IN LACR 13.0
END DESCRIPTION:
XS GIS Cut Line= 2
      3642012.48     10696838.47      3641325.01     10696682.22
#Sta/Elev= 30
  4572.6  265.04  4589.2  265.16  4606.3  264.14  4637.4  264.04  4749.9  261.12
  4801.2  260.59  4809.6  261.15  4814.8  260.57  4852.4  260.76  4863.0  260.14
  4883.2  260.78  4893.5  259.01  4900.9  258.86  4914.0  260.16  4924.2  260.56
  4944.0  260.43  4949.1  259.47  4955.0  260.34  4975.5  261.05  4985.7  257.61
  4989.2  257.43  4991.9  256.93  4995.2  257.43  5006.3  258.90  5016.5  259.22
  5035.2  261.28  5083.4  260.98  5119.1  262.64  5160.1  263.61  5277.6  265.30
#Mann=3,-1,0
  4572.6    0.05       0  4989.2    0.03       0  4995.2    0.05       0
Bank Sta=4989.2,4995.2
Exp/Cntr=0.3,0.1

Type RM Length L Ch R = 1,5727,592,592,592
BEGIN DESCRIPTION:
UNT 0294 IN LACR 12.0
END DESCRIPTION:
XS GIS Cut Line= 2
      3642132.30     10696546.80      3641414.09     10696395.88
#Sta/Elev= 30
  4643.4  264.38  4701.1  262.89  4751.0  262.77  4779.0  261.53  4789.2  261.77
  4800.8  260.90  4819.9  260.28  4830.1  260.76  4842.5  260.07  4895.4  259.04
  4911.8  259.51  4922.0  259.03  4945.3  259.03  4952.7  259.51  4983.4  259.01
  4990.1  258.53  4992.2  256.13  4994.9  255.63  4998.2  256.13  5003.8  257.61
  5014.0  258.97  5029.6  259.27  5045.0  259.84  5089.8  259.75  5177.5  262.55
  5208.2  262.87  5218.4  263.44  5239.3  263.53  5269.5  264.45  5377.3  265.59
#Mann=5,-1,0
  4643.4    0.05       0  4842.5    0.16       0  4992.2    0.07       0
  4998.2    0.16       0  5029.6    0.05       0
Bank Sta=4992.2,4998.2
Exp/Cntr=0.3,0.1

Type RM Length L Ch R = 1,5135,454,454,454
BEGIN DESCRIPTION:
UNT 0294 IN LACR 11.0
END DESCRIPTION:
XS GIS Cut Line= 3
      3642349.63     10696310.20      3642049.61     10696110.19
      3641649.59     10696110.19
#Sta/Elev= 30
  4604.0  266.78  4719.7  264.65  4822.9  261.27  4848.9  260.38  4869.9  258.47
  4885.0  258.47  4892.5  257.20  4928.9  257.57  4942.0  257.63  4951.1  256.90
  4961.6  254.60  4967.1  254.60  4974.6  255.99  4994.6  255.44  5001.6  254.46
  5004.3  253.96  5007.6  254.46  5014.6  256.24  5044.6  256.89  5054.6  256.16
  5064.6  257.27  5104.6  257.56  5134.6  258.91  5164.6  258.96  5274.6  261.76
  5294.6  261.66  5314.6  262.92  5334.6  263.14  5344.6  265.31  5364.6  265.34
#Mann=5,-1,0
  4604.0    0.05       0  4822.9    0.16       0  4928.9    0.05       0
  5001.6    0.03       0  5007.6    0.05       0
Bank Sta=5001.6,5007.6
Exp/Cntr=0.3,0.1

Type RM Length L Ch R = 1,4681,467,467,467
BEGIN DESCRIPTION:
UNT 0294 IN LACR 10.0
END DESCRIPTION:
XS GIS Cut Line= 3
      3642249.57     10695660.21      3641999.61     10695760.19
      3641599.64     10695710.19
#Sta/Elev= 30
  4762.9  264.72  4772.3  263.89  4777.7  264.38  4822.8  262.43  4831.5  262.36
  4855.7  260.59  4870.6  260.62  4880.0  259.60  4909.6  258.22  4915.0  258.51
  4924.4  257.19  4933.8  256.64  4993.1  254.23  4996.8  252.47  4999.6  251.97
  5002.8  252.47  5022.7  255.43  5034.6  255.00  5052.3  253.42  5061.3  253.53
  5082.5  254.00  5132.9  256.99  5150.5  257.46  5155.6  257.04  5253.8  261.17
  5274.0  261.12  5284.1  262.08  5374.8  263.86  5392.4  264.86  5435.2  265.29
#Mann=5,-1,0
  4762.9    0.12       0  4822.8    0.16       0  4996.8    0.07       0
  5002.8    0.16       0  5061.3    0.05       0
Bank Sta=4996.8,5002.8
Exp/Cntr=0.3,0.1

Type RM Length L Ch R = 1,4214,446,446,446
BEGIN DESCRIPTION:
UNT 0294 IN LACR 9.0
END DESCRIPTION:
XS GIS Cut Line= 2
      3642340.68     10695479.10      3641309.41     10695307.23
#Sta/Elev= 30
  4627.7  266.69  4699.8  264.51  4769.4  260.17  4882.2  255.12  4921.3  255.02
  4951.9  255.17  4983.6  253.58  5000.9  250.12  5003.6  249.62  5006.9  250.12
  5012.7  253.58  5054.6  254.55  5105.3  258.91  5188.9  261.38  5195.2  262.22
  5237.1  263.30  5297.9  263.75  5316.9  263.24  5328.3  258.56  5338.4  259.78
  5348.6  257.20  5368.9  264.56  5382.8  264.75  5409.4  267.08  5419.5  267.47
  5443.6  264.51  5502.7  264.12  5626.1  264.30  5632.4  265.85  5673.2  266.06
#Mann=6,-1,0
  4627.7    0.12       0  4921.3    0.16       0  5000.9    0.07       0
  5006.9    0.16       0  5188.9    0.05       0  5502.7    0.16       0
Bank Sta=5000.9,5006.9
Exp/Cntr=0.3,0.1

Type RM Length L Ch R = 1,3768,501,501,501
BEGIN DESCRIPTION:
UNT 0294 IN LACR 8.0
END DESCRIPTION:
XS GIS Cut Line= 2
      3642444.78     10695239.78      3641689.64     10694840.51
#Sta/Elev= 30
  4586.3  264.18  4603.5  264.53  4626.1  263.56  4685.0  265.19  4701.4  264.47
  4716.6  261.25  4723.4  257.99  4729.0  258.52  4739.2  256.19  4745.4  253.62
  4761.7  252.77  4767.4  251.73  4833.4  253.58  4863.6  252.81  4976.2  253.40
  4981.8  253.12  4995.2  248.80  4997.9  248.30  5001.2  248.80  5010.7  251.52
  5020.2  252.38  5033.3  252.17  5064.2  254.69  5146.4  257.15  5199.1  259.79
  5256.6  263.22  5308.8  265.35  5330.5  266.34  5388.7  267.54  5440.5  267.29
#Mann=6,-1,0
  4586.3    0.12       0  4995.2    0.07       0  5001.2    0.12       0
  5199.1    0.16       0  5308.8    0.05       0  5330.5    0.12       0
Bank Sta=4995.2,5001.2
Exp/Cntr=0.3,0.1

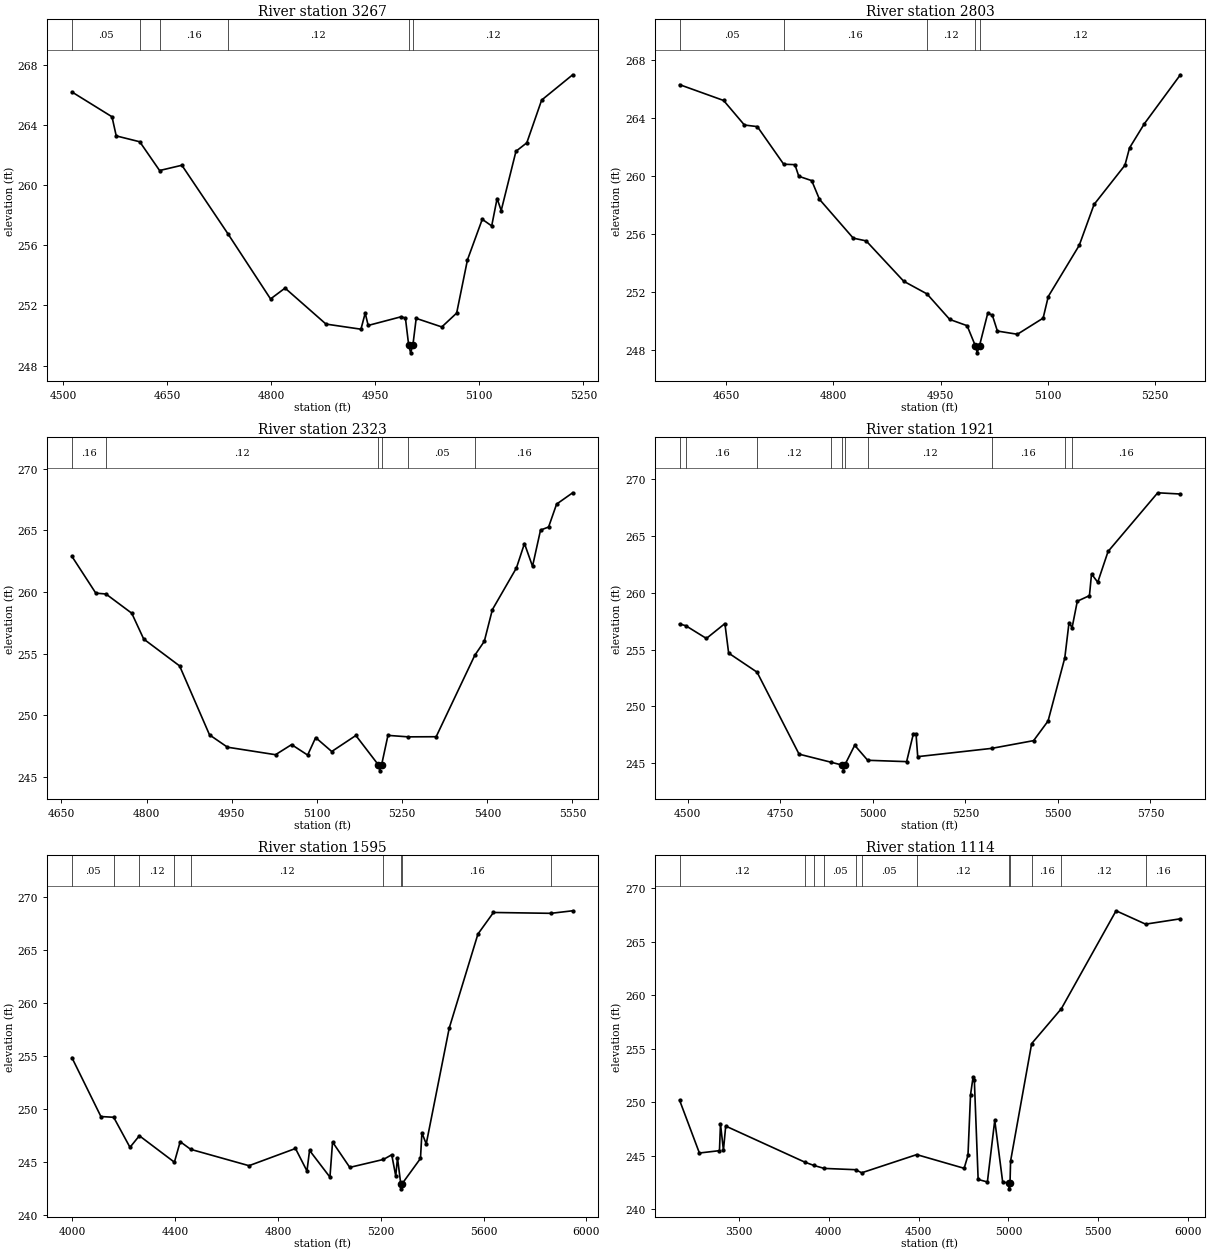
Type RM Length L Ch R = 1,3267,464,464,464
BEGIN DESCRIPTION:
UNT 0294 IN LACR 7.0
END DESCRIPTION:
XS GIS Cut Line= 3
      3642649.61     10695110.19      3642399.61     10694760.19
      3642249.59     10694510.16
#Sta/Elev= 30
  4512.8  266.18  4570.6  264.53  4576.7  263.26  4610.6  262.87  4639.2  260.96
  4671.3  261.31  4737.5  256.77  4799.1  252.43  4820.0  253.15  4879.0  250.76
  4929.4  250.42  4935.5  251.49  4939.8  250.67  4987.6  251.25  4993.5  251.15
  4998.2  249.35  5001.0  248.85  5004.2  249.35  5009.0  251.14  5045.9  250.57
  5067.3  251.49  5082.9  255.03  5104.2  257.72  5117.8  257.28  5125.6  259.10
  5131.5  258.30  5152.8  262.24  5168.4  262.80  5189.8  265.64  5234.5  267.32
#Mann=6,-1,0
  4512.8    0.05       0  4610.6    0.12       0  4639.2    0.16       0
  4737.5    0.12       0  4998.2    0.07       0  5004.2    0.12       0
Bank Sta=4998.2,5004.2
Exp/Cntr=0.3,0.1

Type RM Length L Ch R = 1,2803,480,480,480
BEGIN DESCRIPTION:
UNT 0294 IN LACR 6.0
END DESCRIPTION:
XS GIS Cut Line= 3
      3642849.60     10695010.18      3642699.61     10694660.19
      3642449.64     10694460.21
#Sta/Elev= 30
  4584.8  266.30  4646.4  265.21  4675.5  263.52  4693.6  263.41  4730.5  260.82
  4746.2  260.79  4751.6  259.99  4769.7  259.69  4780.6  258.40  4827.8  255.73
  4845.9  255.54  4898.5  252.76  4931.0  251.89  4962.9  250.13  4987.2  249.70
  4998.6  248.33  5001.3  247.83  5004.6  248.33  5016.0  250.54  5022.4  250.44
  5029.6  249.33  5057.6  249.11  5093.6  250.22  5100.8  251.71  5144.1  255.23
  5164.9  258.05  5208.1  260.75  5214.5  261.94  5235.3  263.61  5285.7  266.98
#Mann=5,-1,0
  4584.8    0.05       0  4730.5    0.16       0  4931.0    0.12       0
  4998.6    0.07       0  5004.6    0.12       0
Bank Sta=4998.6,5004.6
Exp/Cntr=0.3,0.1

Type RM Length L Ch R = 1,2323,402,402,402
BEGIN DESCRIPTION:
UNT 0294 IN LACR 5.0
END DESCRIPTION:
XS GIS Cut Line= 3
      3643099.60     10694660.17      3642999.61     10694360.19
      3642599.61     10693960.19
#Sta/Elev= 30
  4668.4  262.90  4710.5  259.91  4728.4  259.84  4773.8  258.28  4794.9  256.18
  4858.1  254.00  4910.8  248.40  4942.4  247.40  5027.0  246.79  5055.3  247.61
  5083.6  246.76  5097.7  248.18  5126.0  247.05  5168.5  248.35  5207.9  245.98
  5210.6  245.48  5213.9  245.98  5225.0  248.36  5260.5  248.24  5309.9  248.25
  5377.9  254.86  5394.7  256.00  5408.9  258.57  5451.3  261.96  5465.4  263.94
  5479.6  262.09  5493.7  265.03  5507.9  265.28  5522.0  267.14  5550.3  268.06
#Mann=6,-1,0
  4668.4    0.16       0  4728.4    0.12       0  5207.9    0.07       0
  5213.9    0.12       0  5260.5    0.05       0  5377.9    0.16       0
Bank Sta=5207.9,5213.9
Exp/Cntr=0.3,0.1

Type RM Length L Ch R = 1,1921,326,326,326
BEGIN DESCRIPTION:
UNT 0294 IN LACR 4.0
END DESCRIPTION:
XS GIS Cut Line= 3
      3643273.80     10694762.40      3643312.87     10694128.68
      3642670.51     10693807.50
#Sta/Elev= 30
  4477.9  257.26  4494.7  257.10  4550.3  255.98  4600.3  257.29  4610.4  254.69
  4687.2  253.01  4800.7  245.79  4888.1  245.07  4918.0  244.82  4920.7  244.32
  4924.0  244.82  4951.0  246.57  4986.1  245.25  5091.3  245.13  5109.6  247.59
  5116.7  247.59  5121.3  245.57  5321.4  246.30  5434.4  246.98  5473.5  248.71
  5518.7  254.27  5530.1  257.37  5538.4  256.93  5552.5  259.26  5585.3  259.75
  5590.9  261.66  5607.7  260.93  5635.6  263.64  5769.8  268.81  5831.0  268.70
#Mann=10,-1,0
  4477.9    0.05       0  4494.7    0.16       0  4687.2    0.12       0
  4888.1    0.07       0  4918.0    0.07       0  4924.0    0.07       0
  4986.1    0.12       0  5321.4    0.16       0  5518.7     0.1       0
  5538.4    0.16       0
Bank Sta=4918,4924
Exp/Cntr=0.3,0.1

Type RM Length L Ch R = 1,1595,481,481,481
BEGIN DESCRIPTION:
UNT 0294 IN LACR 3.0
END DESCRIPTION:
XS GIS Cut Line= 3
      3643434.40     10694909.90      3643634.05     10694080.94
      3642653.90     10693590.87
#Sta/Elev= 30
  3998.0  254.85  4110.9  249.30  4160.6  249.23  4224.0  246.40  4260.5  247.49
  4396.8  245.00  4419.4  246.93  4460.3  246.21  4687.1  244.67  4868.0  246.29
  4912.7  244.17  4922.7  246.11  5002.1  243.59  5012.2  246.90  5079.2  244.51
  5210.4  245.26  5242.5  245.70  5258.1  243.70  5264.9  245.40  5277.5  242.99
  5280.2  242.49  5283.5  242.99  5354.3  245.35  5359.9  247.77  5376.7  246.72
  5466.1  257.62  5577.9  266.49  5638.3  268.52  5861.9  268.44  5946.5  268.68
#Mann=9,-1,0
  3998.0    0.05       0  4160.6    0.07       0  4260.5    0.12       0
  4396.8    0.07       0  4460.3    0.12       0  5210.4    0.16       0
  5277.5    0.07       0  5283.5    0.16       0  5861.9    0.12       0
Bank Sta=5277.5,5283.5
Exp/Cntr=0.3,0.1

Type RM Length L Ch R = 1,1114,281,281,281
BEGIN DESCRIPTION:
UNT 0294 IN LACR 2.0
END DESCRIPTION:
XS GIS Cut Line= 4
      3643460.42     10695087.92      3644020.33     10694007.15
      3643681.79     10693677.29      3642609.75     10693447.26
#Sta/Elev= 30
  3170.2  250.17  3280.3  245.24  3392.0  245.46  3397.6  247.96  3414.1  245.50
  3426.7  247.76  3866.4  244.39  3916.9  244.08  3974.6  243.80  4149.5  243.68
  4183.3  243.39  4489.5  245.09  4753.4  243.81  4774.7  245.02  4788.9  250.68
  4803.0  252.33  4810.0  252.10  4831.3  242.77  4882.7  242.53  4923.7  248.30
  4967.6  242.55  5002.5  242.39  5005.2  241.89  5008.5  242.39  5011.8  244.49
  5129.0  255.47  5294.5  258.74  5598.7  267.89  5763.0  266.64  5956.5  267.14
#Mann=12,-1,0
  3170.2    0.12       0  3866.4    0.05       0  3916.9    0.07       0
  3974.6    0.05       0  4149.5    0.07       0  4183.3    0.05       0
  4489.5    0.12       0  5002.5    0.07       0  5008.5    0.12       0
  5129.0    0.16       0  5294.5    0.12       0  5763.0    0.16       0
Bank Sta=5002.5,5008.5
Exp/Cntr=0.3,0.1

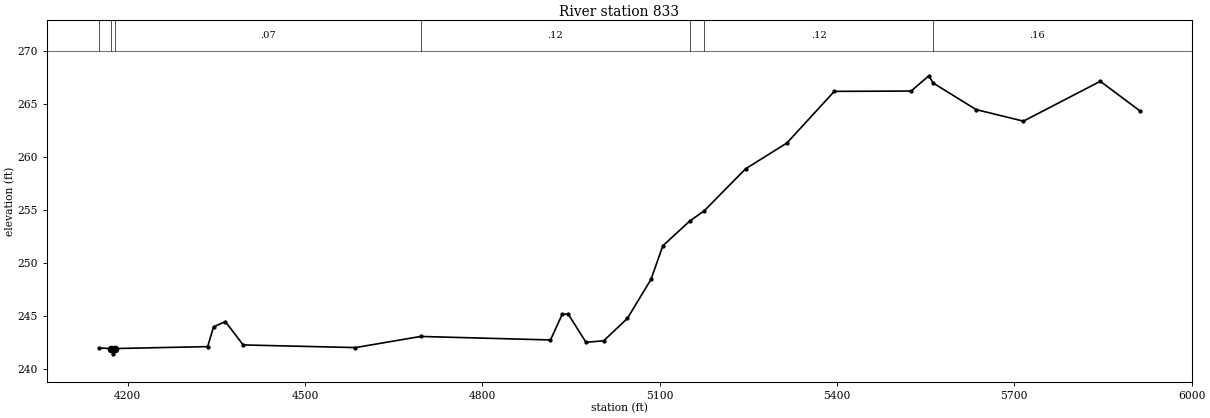
Type RM Length L Ch R = 1,833,0,0,0
BEGIN DESCRIPTION:
UNT 0294 IN LACR 1.0
END DESCRIPTION:
XS GIS Cut Line= 2
      3644393.60     10693382.15      3642632.98     10693364.81
#Sta/Elev= 30
  4151.3  242.00  4172.3  241.95  4175.0  241.45  4178.3  241.95  4335.3  242.13
  4345.3  244.00  4365.3  244.49  4395.3  242.29  4585.3  242.04  4695.6  243.09
  4915.3  242.76  4935.3  245.20  4945.3  245.20  4975.3  242.54  5005.3  242.68
  5045.3  244.79  5085.3  248.47  5105.3  251.64  5150.5  253.96  5175.5  254.95
  5245.3  258.90  5315.3  261.34  5395.4  266.21  5525.4  266.24  5555.4  267.68
  5562.8  266.99  5635.4  264.49  5715.4  263.40  5845.4  267.16  5912.0  264.39
#Mann=7,-1,0
  4151.3    0.07       0  4172.3    0.07       0  4178.3    0.07       0
  4695.6    0.12       0  5150.5    0.16       0  5175.5    0.12       0
  5562.8    0.16       0
Bank Sta=4172.3,4178.3
Exp/Cntr=0.3,0.1

Chan Stop Cuts=-1