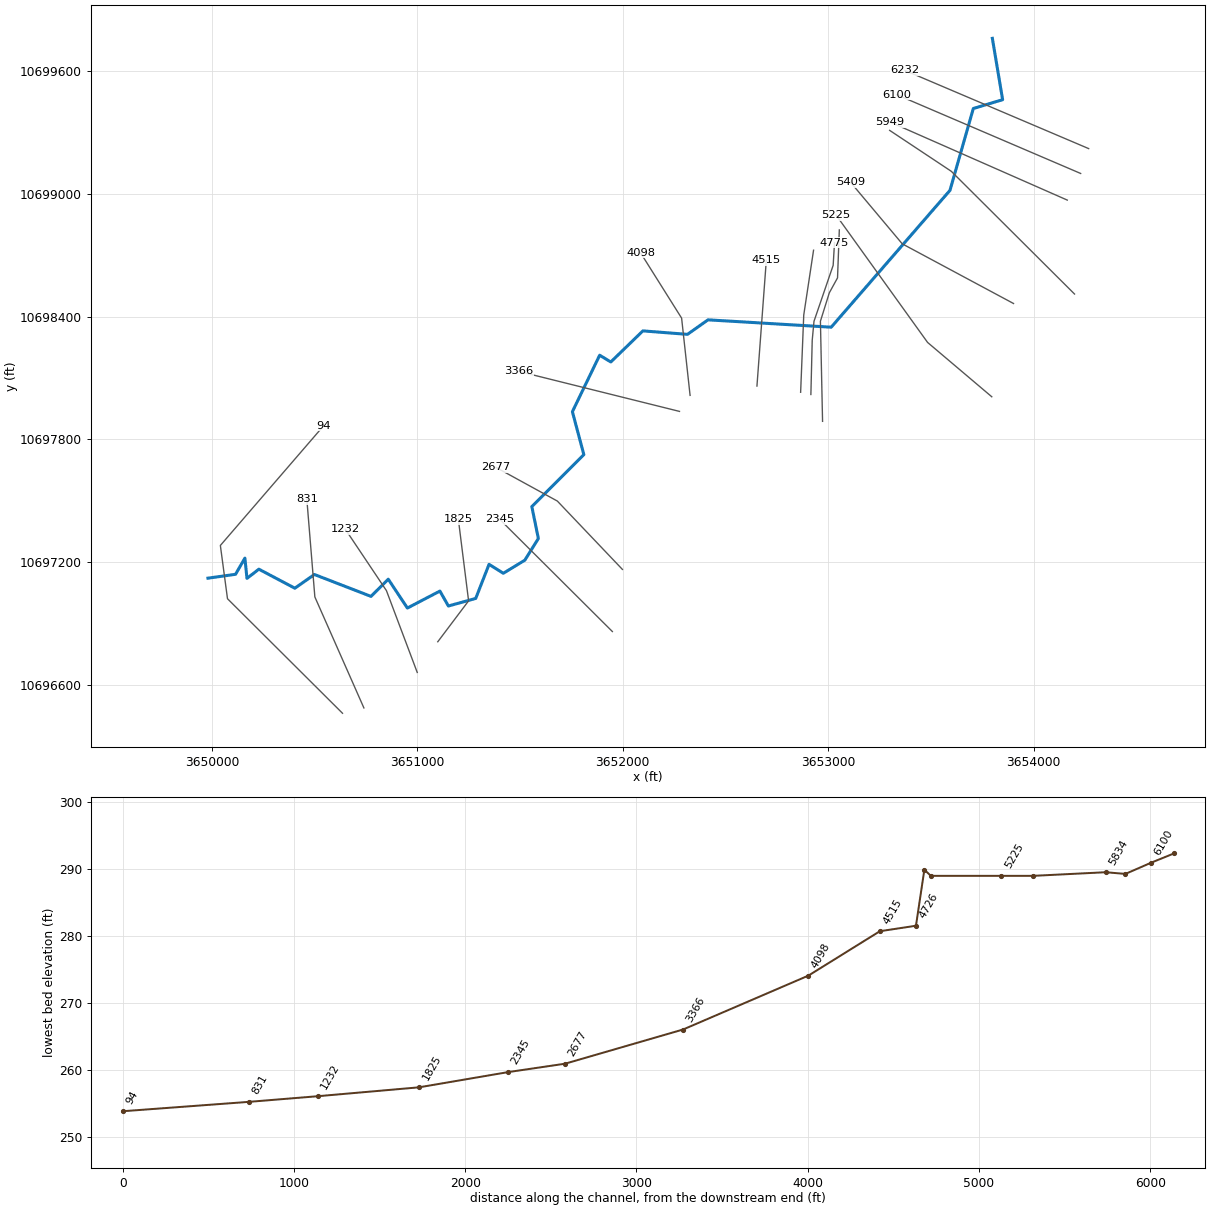
--- UNT 0296 IN LACR.prj (project) ---

Proj Title=UNT 0296 IN LACR Base Level Engineering
Current Plan=p01
Default Exp/Contr=0.3,0.1
English Units
Geom File=g01
Flow File=f01
Plan File=p01
BEGIN DESCRIPTION:
UNT 0296 IN LACR
END DESCRIPTION:

--- UNT 0296 IN LACR.p01 (plan) ---

Plan Title=Multiple Run
Short Identifier=Multiple
Geom File=g01
Flow File=f01
Subcritical Flow
K Sum by GR= 0
Std Step Tol= 0.01
Critical Tol= 0.01
Num of Std Step Trials= 20
Max Error Tol= 0.3
Flow Tol Ratio= 0.001
Split Flow NTrial= 30
Split Flow Tol= 0.02
Split Flow Ratio= 0.02
Log Output Level= 0
Friction Slope Method= 1
Unsteady Friction Slope Method= 2
Unsteady Bridges Friction Slope Method= 1
Parabolic Critical Depth
Global Vel Dist=  1 , 1 , 1
Global Log Level= 0
CheckData=True
Encroach Param= -1, 0, 0, 0
BEGIN DESCRIPTION:
Multiple Run
END DESCRIPTION:

--- UNT 0296 IN LACR.f01 (steady flow) ---

Flow Title=Multiple
Number of Profiles=7
Profile Names=10-year,25-year,50-year,1pct_min,100-year,1pct_plu,500-year
River Rch & RM= UNT 0296 IN LACR,Reach-1,6232
     299     393     468     411     556     752     788
River Rch & RM= UNT 0296 IN LACR,Reach-1,5949
     395     528     637     565     764    1033    1105
River Rch & RM= UNT 0296 IN LACR,Reach-1,2677
     635     873    1072     968    1309    1770    1959
Boundary for River Rch & Prof#=UNT 0296 IN LACR,Reach-1,1
Up Type=0
Dn Type=3
Dn Slope=0.005
Boundary for River Rch & Prof#=UNT 0296 IN LACR,Reach-1,2
Up Type=0
Dn Type=3
Dn Slope=0.005
Boundary for River Rch & Prof#=UNT 0296 IN LACR,Reach-1,3
Up Type=0
Dn Type=3
Dn Slope=0.005
Boundary for River Rch & Prof#=UNT 0296 IN LACR,Reach-1,4
Up Type=0
Dn Type=3
Dn Slope=0.005
Boundary for River Rch & Prof#=UNT 0296 IN LACR,Reach-1,5
Up Type=0
Dn Type=3
Dn Slope=0.005
Boundary for River Rch & Prof#=UNT 0296 IN LACR,Reach-1,6
Up Type=0
Dn Type=3
Dn Slope=0.005
Boundary for River Rch & Prof#=UNT 0296 IN LACR,Reach-1,7
Up Type=0
Dn Type=3
Dn Slope=0.005

--- UNT 0296 IN LACR.g01 (geometry) ---

Geom Title=Existing Conditions

River Reach=UNT 0296 IN LACR,Reach-1
Reach XY= 30
      3653799.61     10699760.19      3653849.61     10699460.19
      3653706.90     10699417.14      3653593.25     10699017.00
      3653015.00     10698348.00      3652415.25     10698384.00
      3652315.25     10698313.00      3652098.25     10698330.00
      3651942.00     10698178.00      3651887.75     10698211.00
      3651755.00     10697935.00      3651810.75     10697725.00
      3651557.50     10697471.00      3651589.25     10697315.00
      3651523.50     10697209.00      3651418.75     10697145.00
      3651349.18     10697188.58      3651284.25     10697022.00
      3651151.25     10696985.00      3651110.00     10697058.00
      3650951.75     10696975.00      3650858.50     10697116.00
      3650774.50     10697032.00      3650499.00     10697139.00
      3650403.75     10697072.00      3650228.50     10697165.00
      3650170.75     10697120.00      3650160.50     10697219.00
      3650115.00     10697140.00      3649980.50     10697121.00

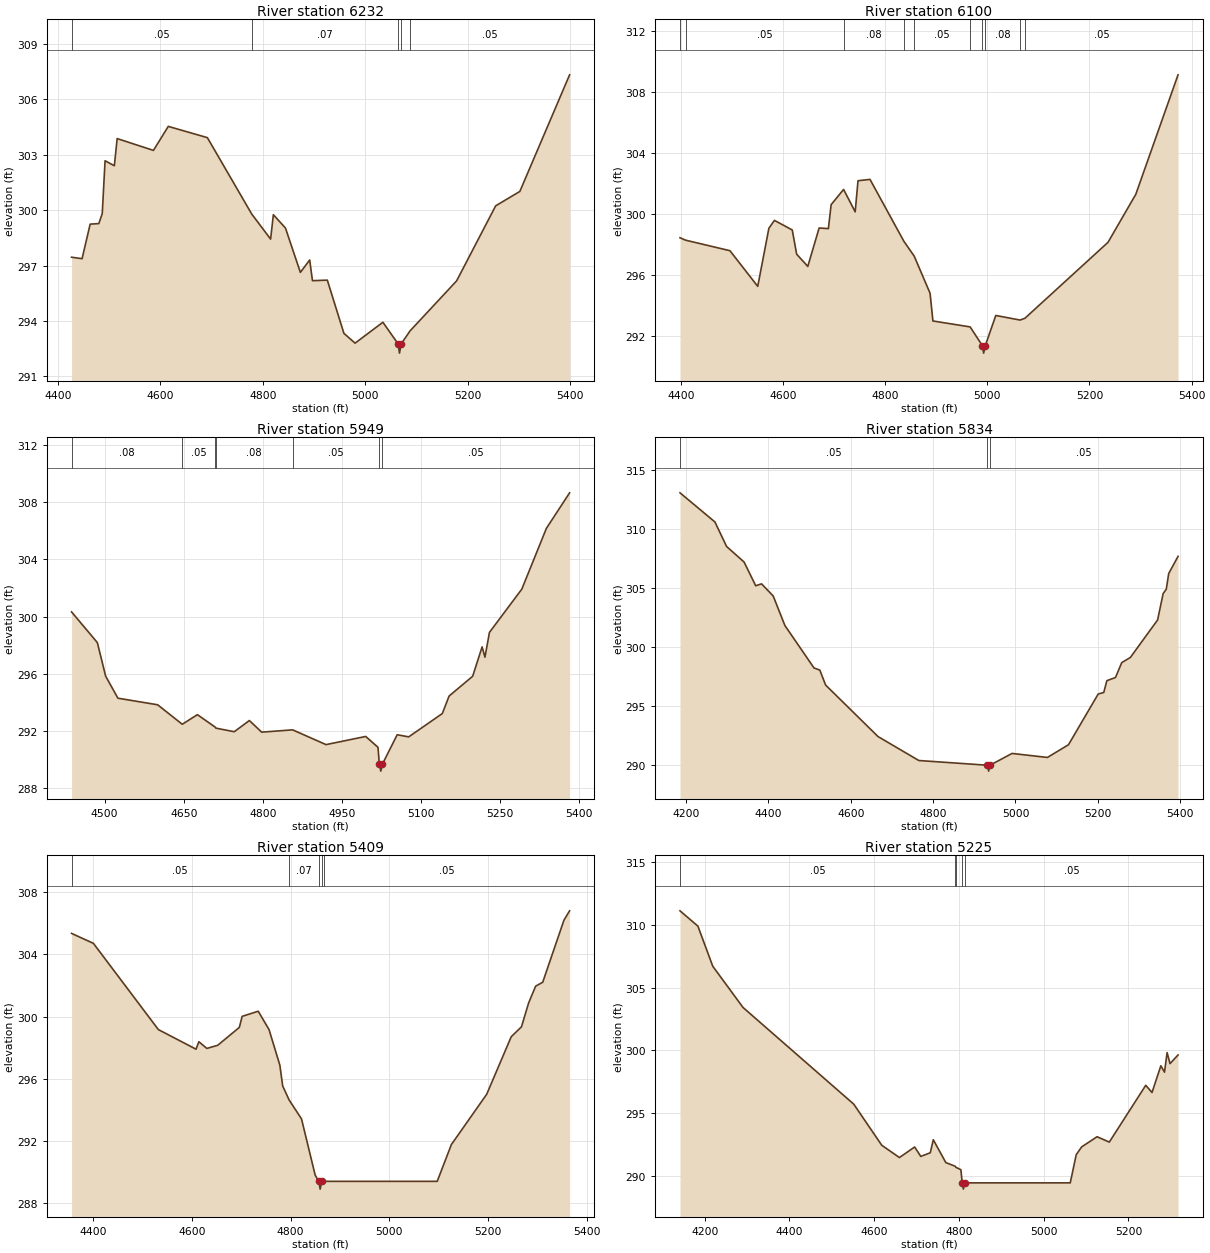
Type RM Length L Ch R = 1,6232,132,132,132
BEGIN DESCRIPTION:
UNT 0296 IN LACR 14.0
END DESCRIPTION:
XS GIS Cut Line= 2
      3654268.49     10699221.11      3653374.54     10699602.99
#Sta/Elev= 30
  4426.5  297.45  4447.0  297.37  4462.8  299.24  4479.7  299.27  4486.4  299.81
  4491.9  302.67  4510.0  302.40  4515.5  303.87  4586.3  303.23  4615.3  304.53
  4691.6  303.92  4778.1  299.79  4815.0  298.43  4820.4  299.75  4844.0  299.03
  4873.1  296.63  4891.3  297.30  4896.7  296.18  4925.7  296.21  4958.1  293.33
  4979.9  292.80  5034.2  293.93  5063.9  292.76  5066.6  292.26  5069.9  292.76
  5087.1  293.46  5178.1  296.17  5254.3  300.23  5301.5  301.01  5398.6  307.32
#Mann=5,-1,0
  4426.5    0.05       0  4778.1    0.07       0  5063.9    0.07       0
  5069.9    0.07       0  5087.1    0.05       0
Bank Sta=5063.9,5069.9
Exp/Cntr=0.3,0.1

Type RM Length L Ch R = 1,6100,151,151,151
BEGIN DESCRIPTION:
Mapping XS b7d361eb
END DESCRIPTION:
XS GIS Cut Line= 2
      3654229.44     10699099.58      3653333.63     10699484.73
#Sta/Elev= 30
  4398.3  298.46  4409.4  298.30  4496.1  297.61  4550.5  295.27  4572.3  299.08
  4583.2  299.60  4618.1  298.97  4626.7  297.38  4648.5  296.58  4670.7  299.10
  4688.8  299.06  4694.2  300.63  4718.6  301.63  4741.3  300.16  4746.8  302.20
  4770.3  302.29  4836.6  298.23  4856.9  297.25  4887.9  294.82  4893.5  293.00
  4966.4  292.61  4990.1  291.39  4992.8  290.89  4996.1  291.39  5016.6  293.36
  5064.2  293.06  5073.7  293.18  5236.3  298.16  5290.7  301.31  5373.4  309.15
#Mann=10,-1,0
  4398.3    0.12       0  4409.4    0.05       0  4718.6    0.08       0
  4836.6    0.07       0  4856.9    0.05       0  4966.4    0.08       0
  4990.1    0.07       0  4996.1    0.08       0  5064.2    0.07       0
  5073.7    0.05       0
Bank Sta=4990.1,4996.1
Exp/Cntr=0.3,0.1

Type RM Length L Ch R = 1,5949,115,115,115
BEGIN DESCRIPTION:
Mapping XS ddcd52d1
END DESCRIPTION:
XS GIS Cut Line= 2
      3654164.33     10698969.37      3653300.61     10699351.32
#Sta/Elev= 30
  4437.2  300.32  4486.1  298.18  4501.8  295.84  4525.1  294.30  4600.4  293.84
  4647.1  292.48  4675.8  293.15  4710.0  292.27  4710.8  292.21  4745.7  291.96
  4774.4  292.74  4797.7  291.93  4856.4  292.09  4919.7  291.06  4995.0  291.63
  5018.3  290.87  5020.8  289.71  5023.6  289.21  5026.8  289.71  5054.7  291.75
  5076.5  291.60  5140.3  293.23  5153.1  294.45  5197.8  295.83  5215.7  297.88
  5221.1  297.16  5229.6  298.89  5291.0  301.91  5337.6  306.15  5381.6  308.63
#Mann=7,-1,0
  4437.2    0.08       0  4647.1    0.05       0  4710.0     0.1       0
  4710.8    0.08       0  4856.4    0.05       0  5020.8    0.03       0
  5026.8    0.05       0
Bank Sta=5020.8,5026.8
Exp/Cntr=0.3,0.1

Type RM Length L Ch R = 1,5834,425,425,425
BEGIN DESCRIPTION:
UNT 0296 IN LACR 13.0
END DESCRIPTION:
XS GIS Cut Line= 3
      3654199.61     10698510.19      3653599.61     10699110.19
      3653299.59     10699310.20
#Sta/Elev= 30
  4185.6  313.06  4270.4  310.59  4298.7  308.51  4341.2  307.19  4369.4  305.18
  4383.6  305.34  4411.9  304.31  4440.2  301.81  4510.9  298.21  4525.0  298.03
  4539.1  296.76  4666.4  292.39  4765.4  290.36  4932.1  289.96  4934.9  289.46
  4938.1  289.96  4991.7  290.96  5077.7  290.62  5128.8  291.70  5200.9  296.00
  5214.4  296.13  5221.9  297.13  5242.9  297.40  5258.0  298.66  5279.0  299.10
  5345.1  302.28  5358.6  304.52  5366.1  304.88  5372.1  306.22  5394.7  307.67
#Mann=3,-1,0
  4185.6    0.05       0  4932.1    0.03       0  4938.1    0.05       0
Bank Sta=4932.1,4938.1
Exp/Cntr=0.3,0.1

Type RM Length L Ch R = 1,5409,184,184,184
BEGIN DESCRIPTION:
UNT 0296 IN LACR 12.0
END DESCRIPTION:
XS GIS Cut Line= 3
      3653902.65     10698463.81      3653360.94     10698755.50
      3653109.32     10699056.41
#Sta/Elev= 30
  4357.0  305.35  4401.2  304.71  4532.6  299.17  4608.8  297.91  4614.5  298.39
  4630.7  297.96  4652.6  298.16  4696.4  299.31  4702.1  300.02  4734.6  300.35
  4756.5  299.17  4778.4  296.88  4784.1  295.55  4796.9  294.66  4822.2  293.43
  4849.8  289.82  4857.2  289.42  4859.9  288.92  4863.2  289.42  4867.7  289.42
  5096.7  289.42  5125.3  291.78  5196.9  295.02  5246.4  298.71  5267.2  299.35
  5281.5  300.87  5295.8  301.96  5310.1  302.21  5353.1  306.20  5364.5  306.80
#Mann=5,-1,0
  4357.0    0.05       0  4796.9    0.07       0  4857.2   0.033       0
  4863.2    0.07       0  4867.7    0.05       0
Bank Sta=4857.2,4863.2
Exp/Cntr=0.3,0.1

Type RM Length L Ch R = 1,5225,412,412,412
BEGIN DESCRIPTION:
Mapping XS 2d9d520b
END DESCRIPTION:
XS GIS Cut Line= 3
      3653796.74     10698007.90      3653484.21     10698273.55
      3653039.18     10698895.56
#Sta/Elev= 30
  4141.9  311.12  4184.1  309.90  4219.2  306.70  4290.6  303.41  4551.8  295.70
  4617.9  292.42  4659.6  291.44  4695.5  292.28  4710.0  291.53  4732.4  291.82
  4739.5  292.86  4769.0  291.04  4791.4  290.74  4792.8  290.66  4804.6  290.47
  4807.7  289.42  4810.5  288.92  4813.7  289.42  5062.6  289.42  5076.7  291.67
  5089.6  292.29  5125.9  293.10  5154.7  292.67  5240.7  297.20  5255.5  296.63
  5276.4  298.76  5285.0  298.25  5291.1  299.81  5298.0  298.93  5316.9  299.62
#Mann=5,-1,0
  4141.9    0.05       0  4791.4    0.07       0  4792.8    0.05       0
  4807.7   0.033       0  4813.7    0.05       0
Bank Sta=4807.7,4813.7
Exp/Cntr=0.3,0.1

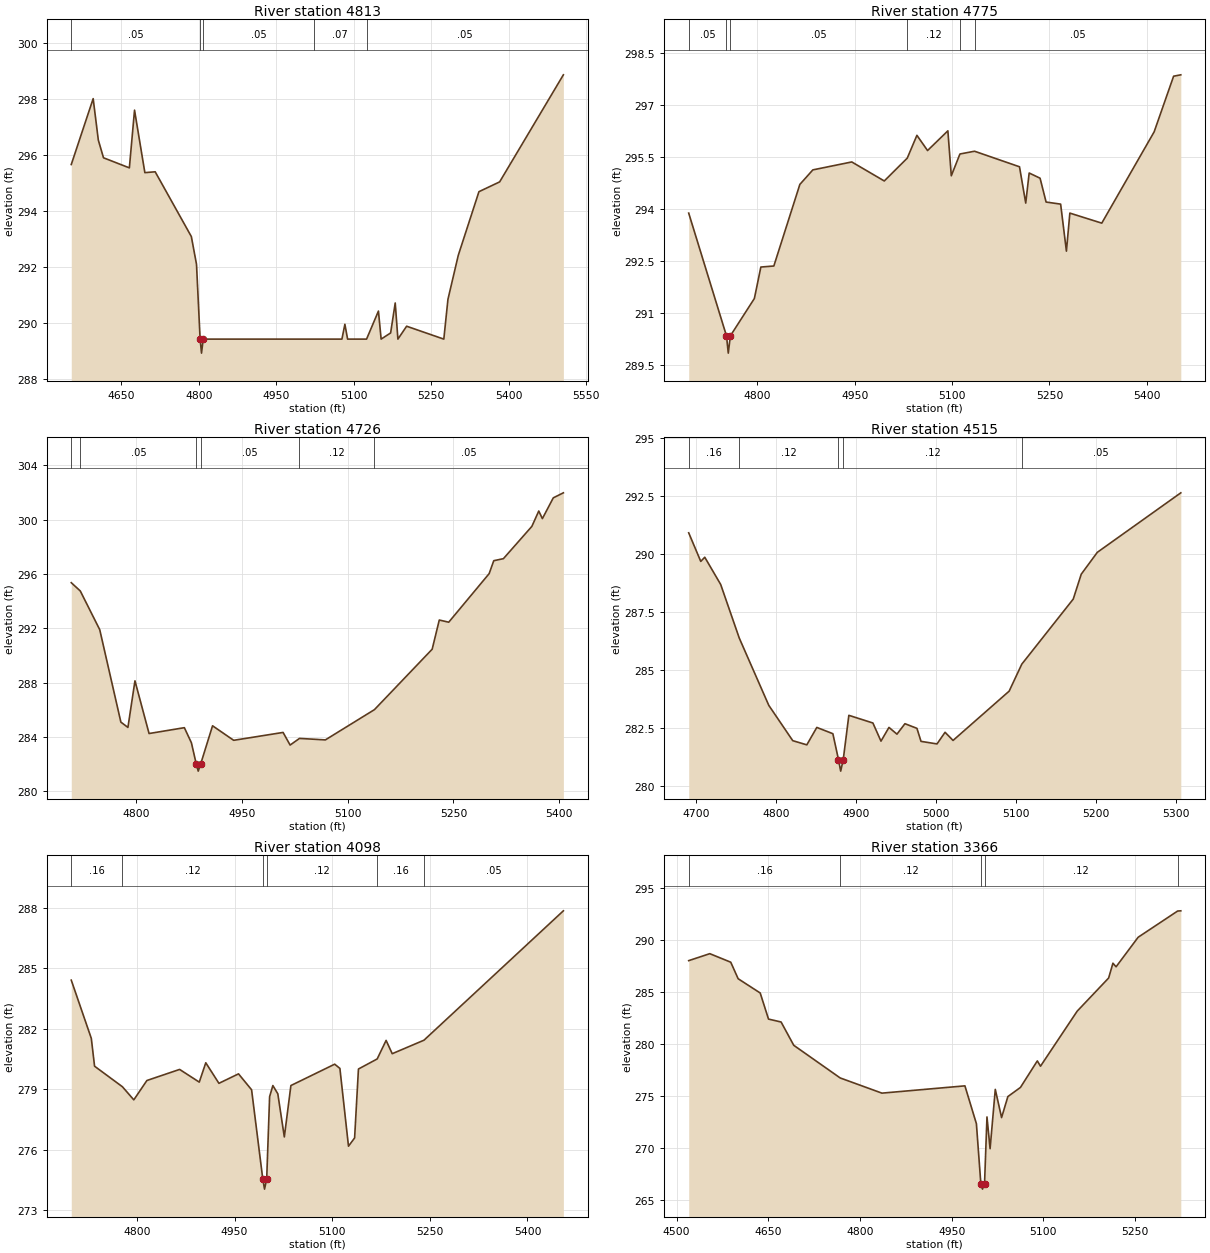
Type RM Length L Ch R = 1,4813,38,38,38
BEGIN DESCRIPTION:
Mapping XS 170d0507
END DESCRIPTION:
XS GIS Cut Line= 5
      3652972.92     10697887.75      3652962.51     10698377.37
      3653005.91     10698516.26      3653045.84     10698589.18
      3653054.52     10698823.54
#Sta/Elev= 30
  4553.2  295.65  4595.6  298.00  4605.6  296.52  4615.6  295.89  4665.7  295.53
  4675.7  297.59  4695.7  295.36  4715.7  295.39  4785.7  293.08  4795.7  292.09
  4802.7  289.42  4805.4  288.92  4808.7  289.42  5022.3  289.42  5077.3  289.42
  5083.0  289.95  5088.3  289.42  5125.0  289.42  5148.0  290.42  5153.2  289.42
  5171.6  289.64  5180.5  290.71  5185.7  289.42  5202.6  289.88  5274.6  289.42
  5282.6  290.84  5302.6  292.41  5342.6  294.68  5382.7  295.03  5506.1  298.85
#Mann=5,-1,0
  4553.2    0.05       0  4802.7   0.033       0  4808.7    0.05       0
  5022.3    0.07       0  5125.0    0.05       0
Bank Sta=4802.7,4808.7
Exp/Cntr=0.3,0.1

Type RM Length L Ch R = 1,4775,49,49,49
BEGIN DESCRIPTION:
UNT 0296 IN LACR 11.0
END DESCRIPTION:
XS GIS Cut Line= 5
      3652916.07     10698018.99      3652922.58     10698283.79
      3652931.26     10698377.10      3653024.58     10698650.54
      3653031.09     10698761.23
#Sta/Elev= 30
  4694.0  293.88  4752.2  290.33  4755.0  289.83  4758.2  290.33  4795.2  291.41
  4805.2  292.32  4825.2  292.35  4865.3  294.71  4885.3  295.13  4945.3  295.36
  4995.4  294.81  5030.8  295.47  5045.7  296.13  5062.1  295.69  5093.4  296.26
  5098.7  294.96  5112.0  295.59  5134.5  295.67  5203.8  295.22  5213.4  294.17
  5218.7  295.04  5235.5  294.89  5244.8  294.20  5267.2  294.14  5276.1  292.78
  5281.4  293.88  5330.6  293.59  5411.3  296.23  5441.3  297.84  5452.4  297.88
#Mann=6,-1,0
  4694.0    0.05       0  4752.2    0.03       0  4758.2    0.05       0
  5030.8    0.12       0  5112.0    0.07       0  5134.5    0.05       0
Bank Sta=4752.2,4758.2
Exp/Cntr=0.3,0.1

Type RM Length L Ch R = 1,4726,211,211,211
BEGIN DESCRIPTION:
Mapping XS 3d48f664
END DESCRIPTION:
XS GIS Cut Line= 3
      3652866.16     10698029.84      3652881.35     10698407.49
      3652929.10     10698724.35
#Sta/Elev= 30
  4707.6  295.36  4720.4  294.75  4748.0  291.90  4778.0  285.09  4788.0  284.70
  4798.0  288.13  4818.0  284.25  4868.1  284.68  4878.1  283.57  4885.1  281.98
  4887.8  281.48  4891.1  281.98  4908.1  284.82  4938.1  283.75  5008.2  284.33
  5018.2  283.40  5031.5  283.89  5068.2  283.78  5137.9  286.01  5219.8  290.46
  5229.9  292.61  5243.3  292.45  5300.7  296.03  5307.2  296.98  5320.9  297.13
  5361.3  299.51  5371.1  300.64  5376.2  300.08  5391.7  301.61  5406.0  301.98
#Mann=6,-1,0
  4707.6    0.16       0  4720.4    0.05       0  4885.1    0.03       0
  4891.1    0.05       0  5031.5    0.12       0  5137.9    0.05       0
Bank Sta=4885.1,4891.1
Exp/Cntr=0.3,0.1

Type RM Length L Ch R = 1,4515,417,417,417
BEGIN DESCRIPTION:
UNT 0296 IN LACR 10.0
END DESCRIPTION:
XS GIS Cut Line= 2
      3652653.49     10698060.30      3652699.06     10698674.41
#Sta/Elev= 30
  4690.7  290.91  4705.8  289.68  4710.8  289.86  4730.7  288.69  4754.0  286.38
  4790.9  283.49  4820.9  281.97  4838.5  281.79  4851.0  282.54  4871.1  282.27
  4878.1  281.16  4880.9  280.66  4884.1  281.16  4891.1  283.06  4921.2  282.73
  4931.3  281.95  4941.3  282.54  4951.3  282.25  4961.3  282.70  4976.3  282.50
  4981.4  281.94  5001.4  281.83  5011.5  282.33  5021.5  281.98  5091.7  284.10
  5107.5  285.26  5171.9  288.06  5181.9  289.13  5202.0  290.07  5306.5  292.63
#Mann=5,-1,0
  4690.7    0.16       0  4754.0    0.12       0  4878.1    0.07       0
  4884.1    0.12       0  5107.5    0.05       0
Bank Sta=4878.1,4884.1
Exp/Cntr=0.3,0.1

Type RM Length L Ch R = 1,4098,732,732,732
BEGIN DESCRIPTION:
UNT 0296 IN LACR 9.0
END DESCRIPTION:
XS GIS Cut Line= 3
      3652327.96     10698014.68      3652286.73     10698392.30
      3652087.08     10698711.31
#Sta/Elev= 30
  4699.0  284.41  4729.8  281.52  4734.8  280.14  4777.6  279.12  4795.1  278.47
  4815.2  279.43  4865.5  279.98  4895.7  279.35  4905.7  280.31  4925.9  279.29
  4956.0  279.76  4976.1  278.97  4993.3  274.54  4996.0  274.04  4999.3  274.54
  5003.8  278.63  5008.8  279.18  5016.4  278.77  5026.4  276.63  5036.5  279.18
  5103.8  280.24  5111.8  280.03  5125.0  276.17  5134.4  276.58  5140.3  280.00
  5169.1  280.50  5182.8  281.42  5192.2  280.76  5241.0  281.43  5455.2  287.85
#Mann=6,-1,0
  4699.0    0.16       0  4777.6    0.12       0  4993.3    0.07       0
  4999.3    0.12       0  5169.1    0.16       0  5241.0    0.05       0
Bank Sta=4993.3,4999.3
Exp/Cntr=0.3,0.1

Type RM Length L Ch R = 1,3366,689,689,689
BEGIN DESCRIPTION:
UNT 0296 IN LACR 8.0
END DESCRIPTION:
XS GIS Cut Line= 2
      3652276.34     10697936.37      3651495.08     10698131.69
#Sta/Elev= 30
  4519.7  287.97  4554.2  288.64  4588.5  287.82  4600.6  286.23  4636.7  284.86
  4650.3  282.35  4670.9  282.07  4691.6  279.83  4767.6  276.69  4835.9  275.23
  4971.7  275.93  4990.5  272.29  4997.8  266.50  5000.5  266.00  5003.8  266.50
  5007.8  272.94  5012.9  269.89  5021.4  275.59  5031.7  272.88  5042.0  274.90
  5062.6  275.78  5090.2  278.33  5095.4  277.82  5155.4  283.11  5206.9  286.30
  5213.9  287.72  5219.1  287.38  5255.2  290.22  5319.8  292.74  5325.0  292.76
#Mann=5,-1,0
  4519.7    0.16       0  4767.6    0.12       0  4997.8    0.07       0
  5003.8    0.12       0  5319.8    0.16       0
Bank Sta=4997.8,5003.8
Exp/Cntr=0.3,0.1

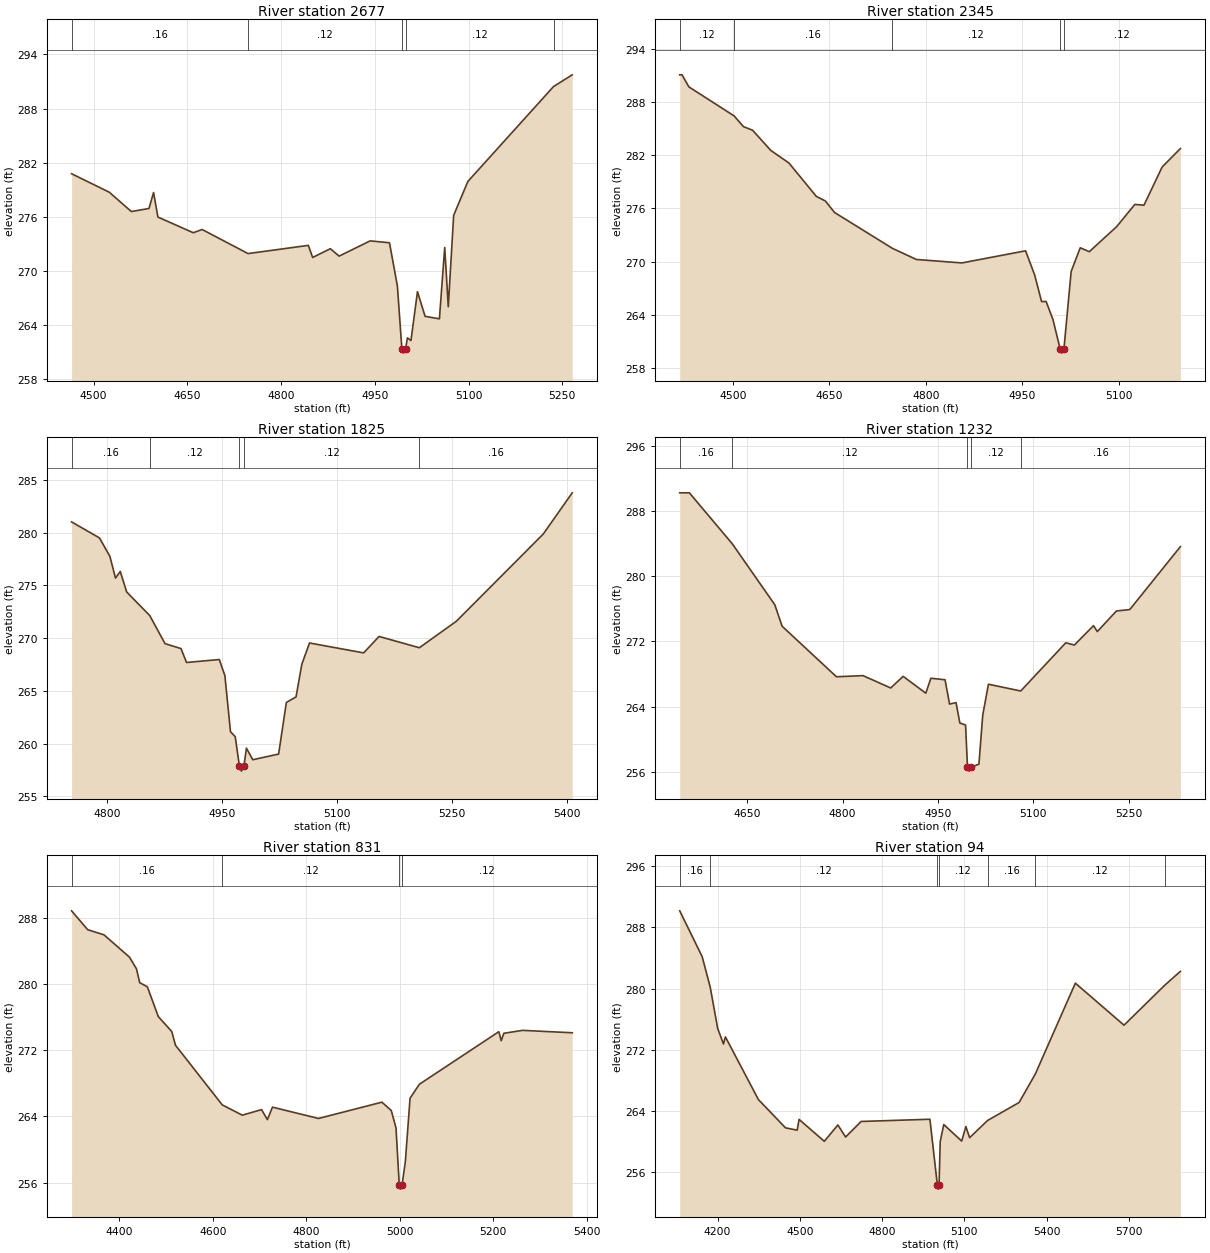
Type RM Length L Ch R = 1,2677,332,332,332
BEGIN DESCRIPTION:
UNT 0296 IN LACR 5.0
END DESCRIPTION:
XS GIS Cut Line= 3
      3651998.53     10697163.83      3651681.72     10697498.01
      3651383.44     10697662.27
#Sta/Elev= 30
  4464.8  280.78  4525.2  278.73  4560.4  276.59  4588.7  276.93  4596.0  278.70
  4602.9  275.98  4659.5  274.24  4673.7  274.60  4747.1  271.93  4843.6  272.84
  4850.5  271.50  4878.8  272.47  4892.9  271.65  4942.5  273.34  4973.4  273.13
  4986.1  268.33  4993.2  261.40  4995.9  260.90  4999.2  261.40  5002.1  262.59
  5007.8  262.30  5018.2  267.71  5030.4  264.98  5053.3  264.70  5061.8  272.61
  5067.5  266.04  5076.1  276.17  5098.9  279.93  5235.9  290.44  5265.8  291.74
#Mann=5,-1,0
  4464.8    0.16       0  4747.1    0.12       0  4993.2    0.07       0
  4999.2    0.12       0  5235.9    0.16       0
Bank Sta=4993.2,4999.2
Exp/Cntr=0.3,0.1

Type RM Length L Ch R = 1,2345,520,520,520
BEGIN DESCRIPTION:
UNT 0296 IN LACR 4.0
END DESCRIPTION:
XS GIS Cut Line= 3
      3651949.64     10696860.16      3651549.61     10697260.19
      3651399.58     10697410.22
#Sta/Elev= 30
  4417.5  291.09  4421.1  291.09  4431.7  289.73  4502.0  286.45  4516.5  285.24
  4530.7  284.83  4559.0  282.55  4587.2  281.13  4629.7  277.36  4643.8  276.84
  4658.0  275.54  4747.9  271.49  4785.2  270.23  4855.9  269.84  4954.9  271.21
  4969.1  268.45  4979.7  265.48  4986.8  265.48  4997.4  263.45  5008.5  260.15
  5011.3  259.65  5014.5  260.15  5025.7  268.87  5039.8  271.55  5053.9  271.11
  5096.4  273.94  5124.6  276.45  5138.8  276.36  5167.1  280.68  5195.4  282.76
#Mann=5,-1,0
  4417.5    0.12       0  4502.0    0.16       0  4747.9    0.12       0
  5008.5    0.07       0  5014.5    0.12       0
Bank Sta=5008.5,5014.5
Exp/Cntr=0.3,0.1

Type RM Length L Ch R = 1,1825,593,593,593
BEGIN DESCRIPTION:
UNT 0296 IN LACR 3.0
END DESCRIPTION:
XS GIS Cut Line= 3
      3651099.62     10696810.20      3651249.61     10697010.19
      3651199.61     10697410.19
#Sta/Elev= 30
  4753.6  281.03  4790.0  279.51  4803.6  277.76  4810.9  275.70  4817.1  276.33
  4825.5  274.38  4855.6  272.14  4875.5  269.48  4896.3  269.01  4903.6  267.69
  4946.3  267.97  4953.6  266.44  4960.9  261.12  4967.1  260.65  4972.5  257.88
  4975.2  257.38  4978.5  257.88  4981.7  259.56  4990.0  258.46  5023.7  259.00
  5033.8  263.90  5046.4  264.42  5054.0  267.53  5064.0  269.54  5134.6  268.60
  5154.7  270.16  5207.3  269.09  5255.5  271.60  5368.9  279.88  5406.7  283.79
#Mann=5,-1,0
  4753.6    0.16       0  4855.6    0.12       0  4972.5    0.07       0
  4978.5    0.12       0  5207.3    0.16       0
Bank Sta=4972.5,4978.5
Exp/Cntr=0.3,0.1

Type RM Length L Ch R = 1,1232,401,401,401
BEGIN DESCRIPTION:
UNT 0296 IN LACR 2.0
END DESCRIPTION:
XS GIS Cut Line= 3
      3650999.62     10696660.15      3650849.61     10697060.19
      3650649.61     10697360.19
#Sta/Elev= 30
  4543.6  290.29  4558.8  290.29  4626.2  284.03  4693.2  276.52  4704.7  273.88
  4790.2  267.66  4832.0  267.80  4875.6  266.28  4895.2  267.71  4930.8  265.64
  4938.8  267.48  4961.1  267.29  4968.2  264.30  4978.4  264.48  4984.4  261.97
  4993.4  261.72  4996.4  256.55  4999.1  256.05  5002.4  256.55  5014.4  256.90
  5020.4  262.94  5029.4  266.74  5080.2  265.91  5151.1  271.84  5164.6  271.56
  5194.7  273.95  5200.7  273.22  5230.7  275.75  5251.8  275.93  5331.4  283.67
#Mann=5,-1,0
  4543.6    0.16       0  4626.2    0.12       0  4996.4    0.07       0
  5002.4    0.12       0  5080.2    0.16       0
Bank Sta=4996.4,5002.4
Exp/Cntr=0.3,0.1

Type RM Length L Ch R = 1,831,737,737,737
BEGIN DESCRIPTION:
Mapping XS b7d461c5
END DESCRIPTION:
XS GIS Cut Line= 3
      3650739.87     10696486.74      3650501.17     10697029.26
      3650462.16     10697505.95
#Sta/Elev= 30
  4297.7  288.85  4332.2  286.57  4367.0  285.95  4421.6  283.25  4436.5  281.84
  4443.5  280.16  4459.8  279.67  4483.2  276.07  4512.0  274.26  4520.0  272.60
  4620.1  265.39  4662.9  264.15  4704.1  264.82  4716.6  263.61  4727.5  265.12
  4825.9  263.75  4961.6  265.72  4981.6  264.71  4991.7  262.62  4998.7  255.71
  5001.5  255.21  5004.7  255.71  5011.7  258.54  5021.8  266.20  5041.8  267.89
  5211.7  274.24  5216.8  273.15  5222.5  274.05  5262.6  274.40  5368.7  274.11
#Mann=4,-1,0
  4297.7    0.16       0  4620.1    0.12       0  4998.7    0.07       0
  5004.7    0.12       0
Bank Sta=4998.7,5004.7
Exp/Cntr=0.3,0.1

Type RM Length L Ch R = 1,94,0,0,0
BEGIN DESCRIPTION:
UNT 0296 IN LACR 1.0
END DESCRIPTION:
XS GIS Cut Line= 4
      3650635.74     10696460.66      3650075.82     10697020.57
      3650041.10     10697280.99      3650543.85     10697866.10
#Sta/Elev= 30
  4061.8  290.17  4143.6  284.19  4173.1  280.19  4200.2  274.81  4221.4  272.77
  4228.4  273.70  4348.6  265.52  4447.6  261.82  4490.1  261.51  4497.1  262.92
  4589.1  260.06  4638.6  262.19  4666.8  260.62  4723.4  262.65  4974.3  262.94
  5001.6  254.31  5004.3  253.81  5007.6  254.31  5011.9  260.05  5024.8  262.25
  5090.1  260.09  5105.5  261.98  5119.1  260.53  5184.7  262.78  5299.6  265.13
  5358.6  268.84  5504.8  280.72  5682.2  275.23  5832.3  280.50  5887.8  282.26
#Mann=7,-1,0
  4061.8    0.16       0  4173.1    0.12       0  5001.6    0.07       0
  5007.6    0.12       0  5184.7    0.16       0  5358.6    0.12       0
  5832.3    0.16       0
Bank Sta=5001.6,5007.6
Exp/Cntr=0.3,0.1

Chan Stop Cuts=-1