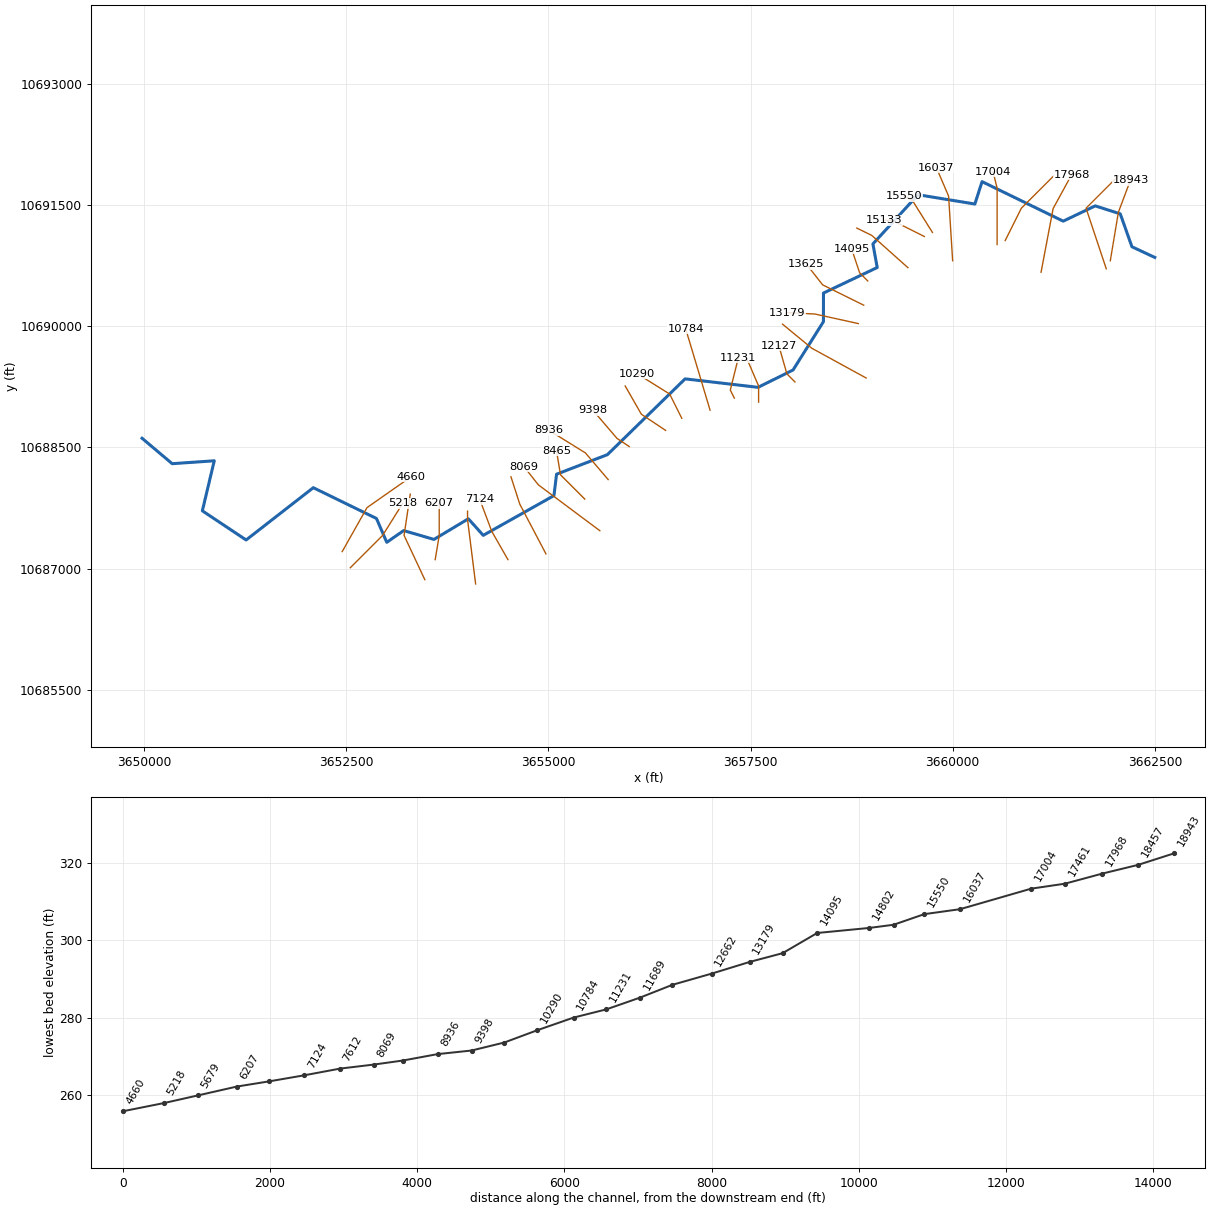
--- UNT 0299 IN LACR.prj (project) ---

Proj Title=UNT 0299 IN LACR Base Level Engineering
Current Plan=p01
Default Exp/Contr=0.3,0.1
English Units
Geom File=g01
Flow File=f01
Plan File=p01
Y Axis Title=Elevation
X Axis Title(PF)=Main Channel Distance
X Axis Title(XS)=Station
BEGIN DESCRIPTION:
UNT 0299 IN LACR
END DESCRIPTION:
DSS Export Rating Curves= 0
DSS Export Rating Curve Sorted= 0
DSS Export Volume Flow Curves= 0
DXF OffsetX= 0
DXF OffsetY= 0
DXF ScaleX= 1
DXF ScaleY= 10

--- UNT 0299 IN LACR.p01 (plan) ---

Plan Title=Multiple Run
Short Identifier=Multiple
Geom File=g01
Flow File=f01
Subcritical Flow
K Sum by GR= 0
Std Step Tol= 0.01
Critical Tol= 0.01
Num of Std Step Trials= 20
Max Error Tol= 0.3
Flow Tol Ratio= 0.001
Split Flow NTrial= 30
Split Flow Tol= 0.02
Split Flow Ratio= 0.02
Log Output Level= 0
Friction Slope Method= 1
Unsteady Friction Slope Method= 2
Unsteady Bridges Friction Slope Method= 1
Parabolic Critical Depth
Global Vel Dist=  1 , 1 , 1
Global Log Level= 0
CheckData=True
Encroach Param= -1, 0, 0, 0
BEGIN DESCRIPTION:
Multiple Run
END DESCRIPTION:

--- UNT 0299 IN LACR.f01 (steady flow) ---

Flow Title=Multiple
Number of Profiles=7
Profile Names=10-year,25-year,50-year,1pct_min,100-year,1pct_plu,500-year
River Rch & RM= UNT 0299 IN LACR,Reach-1,18943
     671     913    1112     994    1344    1818    1975
River Rch & RM= UNT 0299 IN LACR,Reach-1,12127
     900    1240    1523    1371    1854    2508    2764
Boundary for River Rch & Prof#=UNT 0299 IN LACR,Reach-1,1
Up Type=0
Dn Type=3
Dn Slope=0.005
Boundary for River Rch & Prof#=UNT 0299 IN LACR,Reach-1,2
Up Type=0
Dn Type=3
Dn Slope=0.005
Boundary for River Rch & Prof#=UNT 0299 IN LACR,Reach-1,3
Up Type=0
Dn Type=3
Dn Slope=0.005
Boundary for River Rch & Prof#=UNT 0299 IN LACR,Reach-1,4
Up Type=0
Dn Type=3
Dn Slope=0.005
Boundary for River Rch & Prof#=UNT 0299 IN LACR,Reach-1,5
Up Type=0
Dn Type=3
Dn Slope=0.005
Boundary for River Rch & Prof#=UNT 0299 IN LACR,Reach-1,6
Up Type=0
Dn Type=3
Dn Slope=0.005
Boundary for River Rch & Prof#=UNT 0299 IN LACR,Reach-1,7
Up Type=0
Dn Type=3
Dn Slope=0.005

--- UNT 0299 IN LACR.g01 (geometry) ---

Geom Title=Existing Conditions

River Reach=UNT 0299 IN LACR,Reach-1
Reach XY= 30
      3662499.75     10690851.00      3662217.25     10690983.00
      3662073.00     10691390.00      3661763.25     10691489.00
      3661367.25     10691300.00      3660363.50     10691789.00
      3660274.50     10691512.00      3659571.00     10691627.00
      3659013.50     10691018.00      3659066.75     10690726.00
      3658402.00     10690410.00      3658401.75     10690056.00
      3658026.00     10689458.00      3657593.50     10689243.00
      3656690.50     10689348.00      3655729.75     10688410.00
      3655100.75     10688168.00      3655068.50     10687903.00
      3654193.50     10687411.00      3654010.50     10687616.00
      3653584.25     10687361.00      3653209.75     10687470.00
      3653000.75     10687325.00      3652873.25     10687620.00
      3652092.25     10688001.00      3651261.25     10687354.00
      3650719.75     10687715.00      3650867.00     10688334.00
      3650346.75     10688298.00      3649974.00     10688613.00

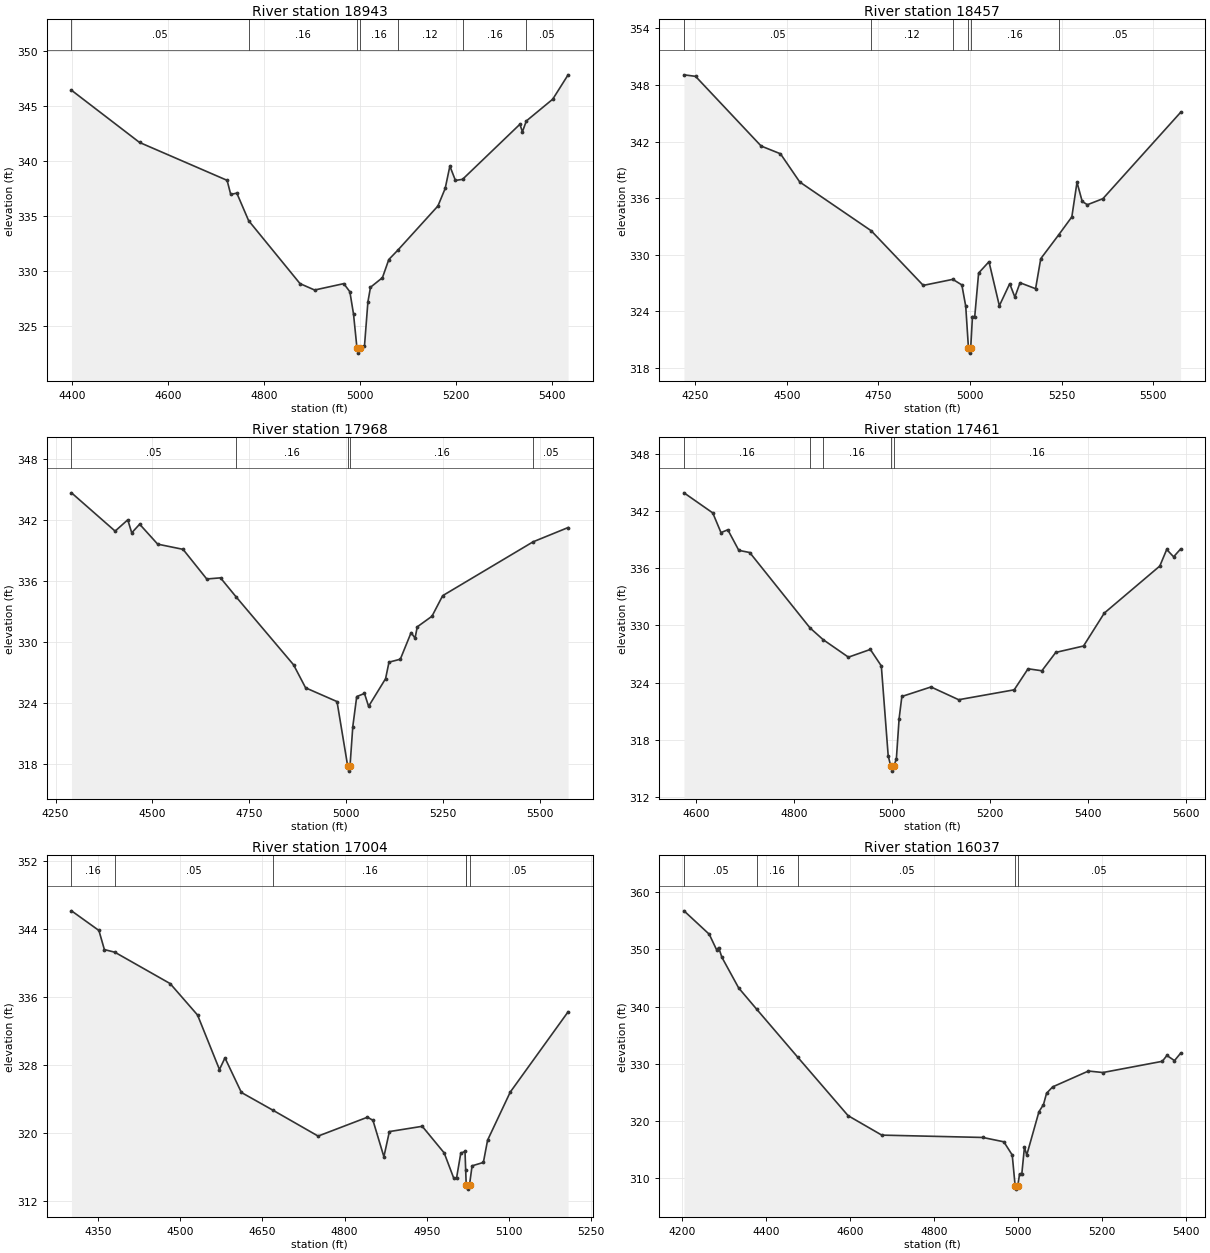
Type RM Length L Ch R = 1,18943,486,486,486
BEGIN DESCRIPTION:
UNT 0299 IN LACR 36.0
END DESCRIPTION:
XS GIS Cut Line= 3
      3661949.61     10690810.22      3662049.61     10691410.19
      3662199.59     10691810.14
#Sta/Elev= 30
  4399.2  346.42  4541.1  341.68  4723.6  338.24  4731.2  336.96  4743.9  337.08
  4768.5  334.58  4875.7  328.86  4906.1  328.28  4966.9  328.86  4979.6  328.12
  4987.2  326.10  4994.3  323.05  4997.1  322.55  5000.3  323.05  5010.1  323.21
  5017.2  327.20  5022.6  328.53  5047.5  329.40  5060.8  331.05  5079.4  331.89
  5163.2  335.91  5178.3  337.50  5188.1  339.53  5199.7  338.23  5214.5  338.33
  5334.1  343.33  5339.4  342.65  5347.5  343.63  5402.6  345.61  5434.6  347.82
#Mann=7,-1,0
  4399.2    0.05       0  4768.5    0.16       0  4994.3    0.07       0
  5000.3    0.16       0  5079.4    0.12       0  5214.5    0.16       0
  5347.5    0.05       0
Bank Sta=4994.3,5000.3
Exp/Cntr=0.3,0.1

Type RM Length L Ch R = 1,18457,489,489,489
BEGIN DESCRIPTION:
UNT 0299 IN LACR 35.0
END DESCRIPTION:
XS GIS Cut Line= 3
      3661899.61     10690710.19      3661649.61     10691460.19
      3662049.64     10691860.22
#Sta/Elev= 30
  4218.8  349.08  4250.4  348.92  4429.6  341.53  4482.3  340.71  4535.0  337.72
  4730.2  332.55  4872.3  326.76  4953.0  327.40  4977.7  326.81  4988.3  324.55
  4995.8  320.08  4998.6  319.58  5001.8  320.08  5006.7  323.46  5012.9  323.46
  5023.5  328.07  5051.8  329.27  5080.1  324.60  5108.4  326.94  5122.5  325.52
  5136.6  327.04  5179.1  326.41  5193.2  329.59  5242.6  332.14  5278.1  334.02
  5292.2  337.69  5306.4  335.66  5320.5  335.31  5362.9  335.95  5575.1  345.10
#Mann=6,-1,0
  4218.8    0.05       0  4730.2    0.12       0  4953.0    0.16       0
  4995.8    0.07       0  5001.8    0.16       0  5242.6    0.05       0
Bank Sta=4995.8,5001.8
Exp/Cntr=0.3,0.1

Type RM Length L Ch R = 1,17968,507,507,507
BEGIN DESCRIPTION:
UNT 0299 IN LACR 34.0
END DESCRIPTION:
XS GIS Cut Line= 3
      3661093.13     10690667.59      3661242.44     10691455.80
      3661471.41     10691875.59
#Sta/Elev= 30
  4291.2  344.64  4403.7  340.88  4436.3  341.99  4446.5  340.71  4466.9  341.56
  4513.4  339.60  4578.8  339.09  4639.9  336.18  4675.4  336.29  4715.0  334.45
  4863.8  327.75  4894.8  325.49  4975.8  324.14  5003.3  317.81  5006.0  317.31
  5009.3  317.81  5016.5  321.69  5026.6  324.63  5046.6  324.94  5057.2  323.67
  5101.0  326.39  5109.8  328.01  5139.0  328.30  5166.8  330.91  5177.0  330.37
  5182.7  331.48  5220.6  332.52  5248.2  334.54  5481.4  339.83  5571.6  341.23
#Mann=5,-1,0
  4291.2    0.05       0  4715.0    0.16       0  5003.3    0.07       0
  5009.3    0.16       0  5481.4    0.05       0
Bank Sta=5003.3,5009.3
Exp/Cntr=0.3,0.1

Type RM Length L Ch R = 1,17461,457,457,457
BEGIN DESCRIPTION:
UNT 0299 IN LACR 33.0
END DESCRIPTION:
XS GIS Cut Line= 3
      3660649.62     10691060.20      3660849.61     10691460.19
      3661249.62     10691860.20
#Sta/Elev= 30
  4575.5  343.93  4634.2  341.82  4651.0  339.75  4664.9  340.05  4687.3  337.89
  4709.6  337.66  4832.6  329.74  4859.3  328.51  4910.9  326.67  4955.6  327.48
  4978.0  325.75  4992.0  316.33  4997.3  315.20  5000.1  314.70  5003.3  315.20
  5008.7  315.99  5014.3  320.22  5019.9  322.54  5079.3  323.54  5135.8  322.20
  5249.0  323.24  5277.3  325.45  5305.5  325.24  5333.8  327.17  5390.4  327.84
  5432.8  331.30  5546.0  336.24  5560.1  337.98  5574.2  337.21  5588.4  338.03
#Mann=5,-1,0
  4575.5    0.16       0  4832.6    0.05       0  4859.3    0.16       0
  4997.3    0.07       0  5003.3    0.16       0
Bank Sta=4997.3,5003.3
Exp/Cntr=0.3,0.1

Type RM Length L Ch R = 1,17004,967,967,967
BEGIN DESCRIPTION:
UNT 0299 IN LACR 32.0
END DESCRIPTION:
XS GIS Cut Line= 3
      3660549.61     10691010.23      3660549.61     10691710.19
      3660499.61     10691910.17
#Sta/Elev= 30
  4301.6  346.16  4351.6  343.85  4361.6  341.60  4380.7  341.29  4481.6  337.60
  4531.6  333.90  4571.6  327.49  4581.6  328.86  4611.6  324.79  4669.8  322.68
  4751.6  319.66  4841.6  321.88  4851.6  321.52  4871.6  317.23  4881.6  320.19
  4941.6  320.81  4981.6  317.68  4999.1  314.70  5004.1  314.70  5011.9  317.65
  5019.6  317.85  5020.8  315.71  5021.8  313.92  5024.5  313.42  5027.8  313.92
  5032.5  316.16  5053.1  316.56  5060.8  319.18  5102.1  324.83  5207.7  334.28
#Mann=6,-1,0
  4301.6    0.16       0  4380.7    0.05       0  4669.8    0.16       0
  5020.8    0.05       0  5021.8    0.07       0  5027.8    0.05       0
Bank Sta=5021.8,5027.8
Exp/Cntr=0.3,0.1

Type RM Length L Ch R = 1,16037,487,487,487
BEGIN DESCRIPTION:
UNT 0299 IN LACR 30.0
END DESCRIPTION:
XS GIS Cut Line= 3
      3659999.61     10690810.22      3659949.61     10691610.19
      3659799.62     10691960.17
#Sta/Elev= 30
  4204.6  356.74  4264.7  352.65  4282.2  349.94  4287.2  350.32  4294.7  348.64
  4334.8  343.26  4377.6  339.55  4475.5  331.15  4595.3  320.94  4675.5  317.54
  4916.0  317.13  4966.1  316.37  4986.1  314.06  4993.1  308.60  4995.9  308.10
  4999.1  308.60  5003.6  310.76  5008.9  310.76  5015.2  315.45  5020.6  314.05
  5049.7  321.63  5060.5  322.88  5067.8  324.85  5082.3  325.97  5167.5  328.74
  5202.0  328.48  5343.4  330.44  5354.3  331.46  5372.4  330.56  5386.9  331.85
#Mann=5,-1,0
  4204.6    0.05       0  4377.6    0.16       0  4475.5    0.05       0
  4993.1    0.03       0  4999.1    0.05       0
Bank Sta=4993.1,4999.1
Exp/Cntr=0.3,0.1

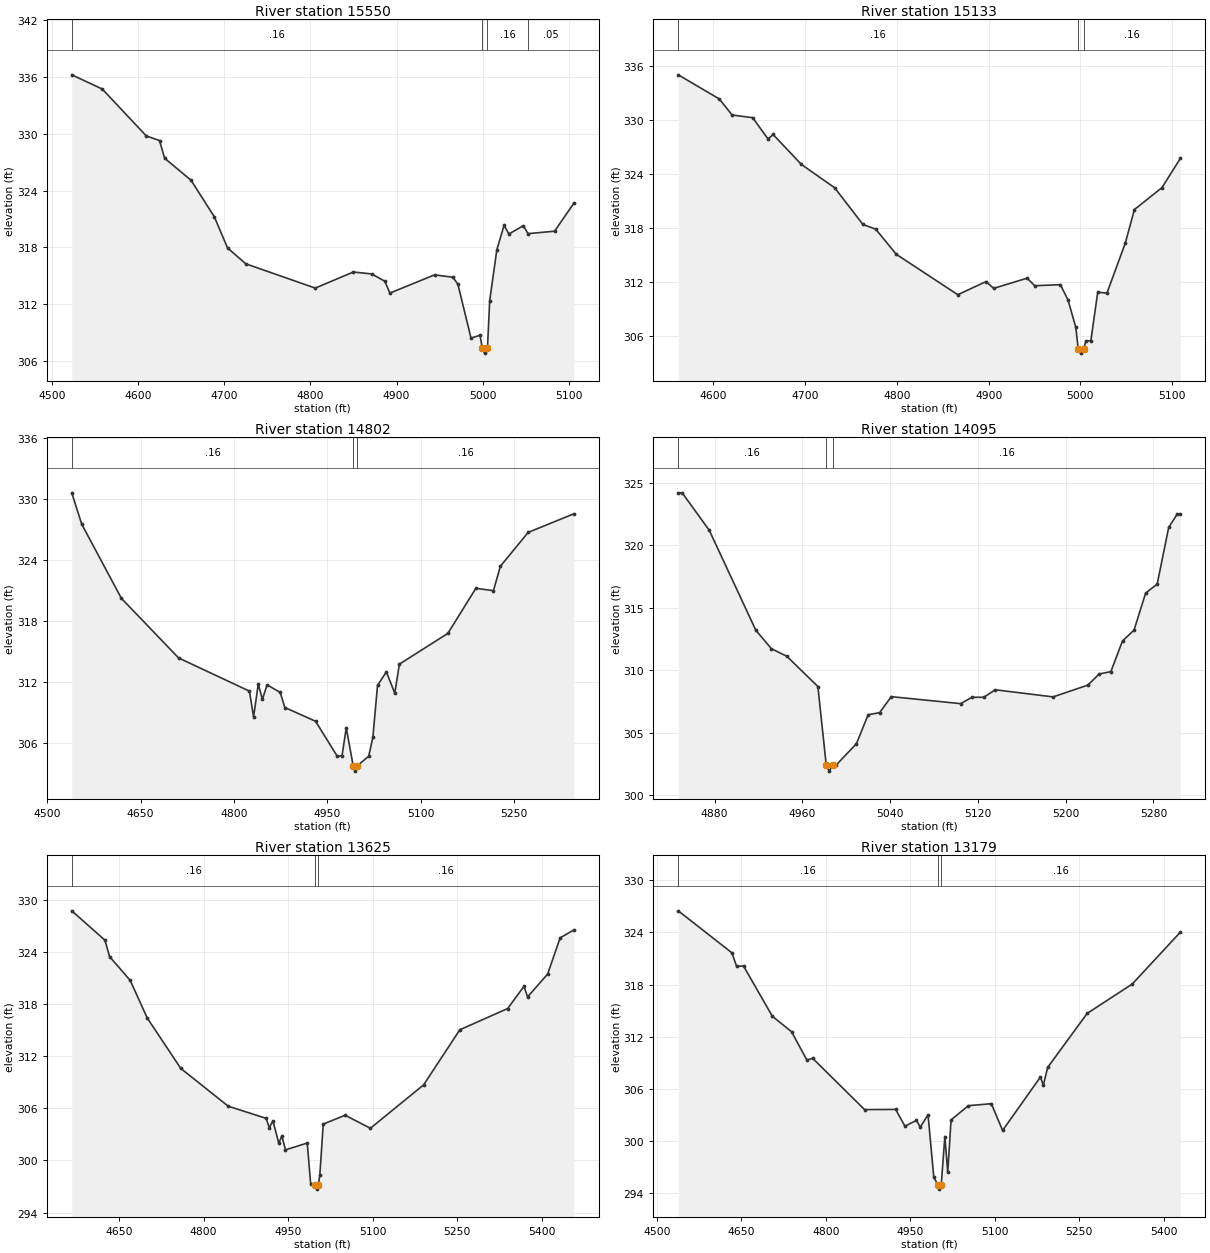
Type RM Length L Ch R = 1,15550,417,417,417
BEGIN DESCRIPTION:
UNT 0299 IN LACR 29.0
END DESCRIPTION:
XS GIS Cut Line= 3
      3659749.60     10691160.20      3659499.61     10691560.19
      3659399.60     10691610.19
#Sta/Elev= 30
  4522.6  336.25  4558.0  334.75  4609.3  329.78  4624.6  329.30  4630.5  327.43
  4661.2  325.10  4688.3  321.23  4703.6  317.94  4724.8  316.26  4805.6  313.69
  4849.8  315.39  4871.1  315.19  4886.4  314.42  4892.3  313.16  4944.2  315.09
  4965.4  314.84  4971.3  314.11  4986.6  308.40  4997.1  308.70  4999.7  307.31
  5002.4  306.81  5005.7  307.31  5008.3  312.36  5016.6  317.74  5025.0  320.33
  5030.6  319.41  5047.4  320.29  5052.9  319.45  5083.7  319.71  5106.1  322.67
#Mann=4,-1,0
  4522.6    0.16       0  4999.7    0.07       0  5005.7    0.16       0
  5052.9    0.05       0
Bank Sta=4999.7,5005.7
Exp/Cntr=0.3,0.1

Type RM Length L Ch R = 1,15133,331,331,331
BEGIN DESCRIPTION:
UNT 0299 IN LACR 28.0
END DESCRIPTION:
XS GIS Cut Line= 3
      3659649.64     10691110.18      3659249.61     10691310.19
      3659149.65     10691310.19
#Sta/Elev= 30
  4561.7  335.03  4606.5  332.34  4620.4  330.56  4642.8  330.26  4659.6  327.89
  4665.1  328.39  4695.9  325.06  4732.2  322.46  4763.0  318.38  4777.0  317.85
  4799.3  315.06  4866.4  310.56  4897.1  312.02  4905.5  311.27  4941.9  312.40
  4950.2  311.56  4978.2  311.68  4986.6  309.95  4995.0  306.92  4997.6  304.56
  5000.3  304.06  5003.6  304.56  5006.1  305.43  5011.4  305.43  5018.9  310.85
  5028.9  310.73  5048.9  316.29  5058.9  320.04  5088.9  322.48  5108.9  325.72
#Mann=3,-1,0
  4561.7    0.16       0  4997.6    0.07       0  5003.6    0.16       0
Bank Sta=4997.6,5003.6
Exp/Cntr=0.3,0.1

Type RM Length L Ch R = 1,14802,707,707,707
BEGIN DESCRIPTION:
UNT 0299 IN LACR 27.0
END DESCRIPTION:
XS GIS Cut Line= 3
      3659446.41     10690724.36      3658999.32     10691123.70
      3658813.64     10691214.38
#Sta/Elev= 30
  4539.5  330.58  4555.5  327.50  4619.1  320.22  4711.0  314.36  4824.7  311.10
  4831.4  308.57  4838.9  311.79  4845.6  310.30  4853.1  311.72  4874.1  310.97
  4881.6  309.49  4930.9  308.14  4966.0  304.68  4973.5  304.77  4980.2  307.51
  4991.4  303.74  4994.2  303.24  4997.4  303.74  5016.2  304.70  5022.9  306.55
  5030.4  311.66  5044.6  312.99  5058.1  310.90  5065.5  313.75  5143.3  316.77
  5188.3  321.20  5216.5  320.97  5227.7  323.37  5272.2  326.69  5345.6  328.52
#Mann=3,-1,0
  4539.5    0.16       0  4991.4    0.07       0  4997.4    0.16       0
Bank Sta=4991.4,4997.4
Exp/Cntr=0.3,0.1

Type RM Length L Ch R = 1,14095,470,470,470
BEGIN DESCRIPTION:
UNT 0299 IN LACR 26.0
END DESCRIPTION:
XS GIS Cut Line= 3
      3658949.63     10690560.17      3658849.61     10690660.19
      3658749.60     10690960.21
#Sta/Elev= 30
  4846.8  324.20  4850.4  324.20  4875.1  321.20  4917.5  313.21  4931.7  311.73
  4945.8  311.12  4974.1  308.70  4981.7  302.43  4984.5  301.93  4987.7  302.43
  4990.9  302.43  5009.3  304.13  5019.9  306.44  5030.4  306.61  5041.0  307.89
  5104.2  307.33  5114.7  307.84  5125.3  307.84  5135.8  308.44  5188.5  307.87
  5220.1  308.81  5230.7  309.71  5241.2  309.89  5251.8  312.35  5262.3  313.21
  5272.9  316.18  5283.4  316.89  5293.9  321.43  5301.8  322.51  5304.5  322.51
#Mann=3,-1,0
  4846.8    0.16       0  4981.7    0.07       0  4987.7    0.16       0
Bank Sta=4981.7,4987.7
Exp/Cntr=0.3,0.1

Type RM Length L Ch R = 1,13625,446,446,446
BEGIN DESCRIPTION:
UNT 0299 IN LACR 25.0
END DESCRIPTION:
XS GIS Cut Line= 3
      3658899.63     10690260.18      3658391.74     10690511.36
      3658191.57     10690766.76
#Sta/Elev= 30
  4566.0  328.75  4624.9  325.37  4633.0  323.49  4669.8  320.73  4699.9  316.41
  4759.5  310.60  4843.7  306.25  4911.0  304.85  4916.6  303.76  4923.0  304.57
  4933.4  301.99  4939.0  302.84  4945.3  301.22  4983.9  302.01  4990.0  297.33
  4997.7  297.20  5000.5  296.70  5003.7  297.20  5006.3  298.36  5012.3  304.19
  5051.2  305.21  5096.0  303.71  5190.5  308.71  5254.7  315.05  5339.7  317.50
  5368.6  320.06  5375.0  318.84  5410.6  321.47  5432.8  325.64  5457.1  326.55
#Mann=3,-1,0
  4566.0    0.16       0  4997.7    0.07       0  5003.7    0.16       0
Bank Sta=4997.7,5003.7
Exp/Cntr=0.3,0.1

Type RM Length L Ch R = 1,13179,517,517,517
BEGIN DESCRIPTION:
UNT 0299 IN LACR 24.0
END DESCRIPTION:
XS GIS Cut Line= 3
      3658832.74     10690032.19      3658297.99     10690150.25
      3657954.46     10690167.60
#Sta/Elev= 30
  4538.0  326.49  4633.4  321.65  4641.6  320.10  4653.9  320.14  4705.1  314.35
  4739.2  312.57  4766.5  309.30  4776.7  309.51  4868.9  303.60  4924.1  303.62
  4940.6  301.69  4961.1  302.36  4967.8  301.58  4981.6  303.00  4991.8  295.82
  4999.0  294.94  5001.8  294.44  5005.0  294.94  5011.5  300.49  5016.6  296.38
  5022.5  302.41  5053.2  304.05  5094.0  304.28  5114.0  301.20  5181.3  307.36
  5186.3  306.40  5194.1  308.46  5264.2  314.68  5344.3  318.06  5429.6  324.03
#Mann=3,-1,0
  4538.0    0.16       0  4999.0    0.07       0  5005.0    0.16       0
Bank Sta=4999,5005
Exp/Cntr=0.3,0.1

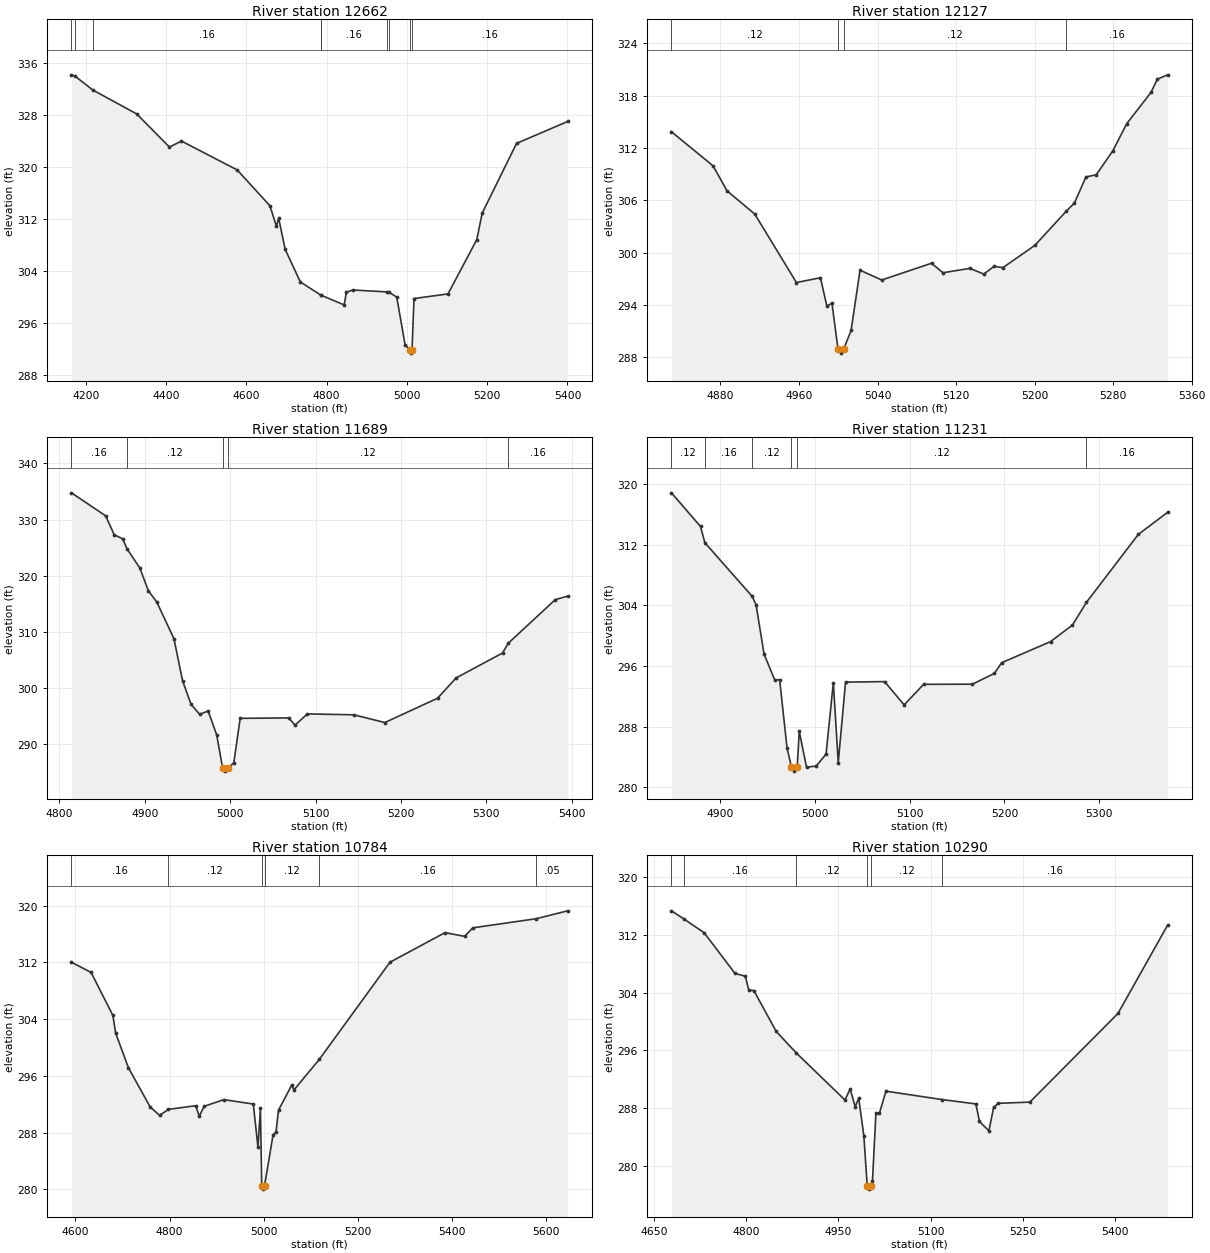
Type RM Length L Ch R = 1,12662,535,535,535
BEGIN DESCRIPTION:
UNT 0299 IN LACR 23.0
END DESCRIPTION:
XS GIS Cut Line= 3
      3658929.90     10689358.61      3658257.19     10689727.28
      3657895.25     10690025.22
#Sta/Elev= 30
  4164.6  334.18  4173.0  334.00  4217.4  331.86  4327.1  328.17  4408.6  323.08
  4438.6  324.00  4577.4  319.56  4658.9  314.06  4675.0  310.92  4680.7  312.14
  4696.8  307.37  4734.7  302.35  4785.9  300.32  4786.0  300.32  4843.8  298.82
  4849.5  300.77  4865.6  301.11  4950.8  300.82  4955.9  300.77  4974.8  300.01
  4995.6  292.70  5006.9  291.91  5009.7  291.41  5012.9  291.91  5017.8  299.80
  5102.5  300.51  5174.2  308.85  5187.6  312.92  5273.2  323.64  5400.5  327.01
#Mann=9,-1,0
  4164.6    0.16       0  4173.0    0.12       0  4217.4    0.16       0
  4785.9    0.12       0  4786.0    0.16       0  4950.8    0.12       0
  4955.9    0.16       0  5006.9    0.07       0  5012.9    0.16       0
Bank Sta=5006.9,5012.9
Exp/Cntr=0.3,0.1

Type RM Length L Ch R = 1,12127,438,438,438
BEGIN DESCRIPTION:
UNT 0299 IN LACR 22.0
END DESCRIPTION:
XS GIS Cut Line= 3
      3658049.62     10689310.18      3657949.61     10689410.19
      3657849.62     10689760.15
#Sta/Elev= 30
  4830.1  313.87  4872.5  309.96  4886.7  307.10  4915.0  304.43  4957.4  296.59
  4981.9  297.14  4988.4  293.88  4993.6  294.23  4999.7  289.00  5002.5  288.50
  5005.7  289.00  5013.1  291.10  5022.2  298.00  5044.3  296.88  5095.0  298.80
  5106.7  297.71  5134.0  298.21  5148.3  297.56  5158.7  298.44  5167.8  298.30
  5200.3  300.85  5232.4  304.78  5240.6  305.70  5252.3  308.69  5262.7  308.93
  5279.6  311.66  5293.9  314.80  5318.6  318.38  5325.1  319.90  5335.5  320.39
#Mann=4,-1,0
  4830.1    0.12       0  4999.7    0.07       0  5005.7    0.12       0
  5232.4    0.16       0
Bank Sta=4999.7,5005.7
Exp/Cntr=0.3,0.1

Type RM Length L Ch R = 1,11689,458,458,458
BEGIN DESCRIPTION:
UNT 0299 IN LACR 21.0
END DESCRIPTION:
XS GIS Cut Line= 3
      3657599.61     10689060.19      3657599.61     10689260.19
      3657449.60     10689610.20
#Sta/Elev= 30
  4814.3  334.76  4854.3  330.66  4864.3  327.31  4874.3  326.55  4879.3  324.79
  4894.3  321.37  4904.3  317.33  4914.3  315.27  4934.3  308.76  4944.3  301.31
  4954.3  297.09  4964.3  295.32  4974.3  295.90  4984.3  291.65  4991.3  285.70
  4994.1  285.20  4997.3  285.70  5004.3  286.68  5011.8  294.60  5068.7  294.68
  5076.0  293.38  5090.5  295.39  5144.9  295.23  5181.1  293.85  5242.8  298.18
  5264.5  301.79  5318.9  306.24  5325.6  307.98  5380.6  315.74  5395.1  316.36
#Mann=5,-1,0
  4814.3    0.16       0  4879.3    0.12       0  4991.3    0.07       0
  4997.3    0.12       0  5325.6    0.16       0
Bank Sta=4991.3,4997.3
Exp/Cntr=0.3,0.1

Type RM Length L Ch R = 1,11231,447,447,447
BEGIN DESCRIPTION:
UNT 0299 IN LACR 20.0
END DESCRIPTION:
XS GIS Cut Line= 3
      3657299.59     10689110.23      3657249.61     10689210.19
      3657349.62     10689610.22
#Sta/Elev= 30
  4848.3  318.86  4879.0  314.42  4883.6  312.28  4933.6  305.20  4937.7  304.08
  4946.1  297.61  4957.3  294.20  4962.6  294.20  4970.4  285.21  4975.1  282.65
  4977.8  282.15  4981.1  282.65  4983.3  287.39  4991.0  282.66  5001.3  282.83
  5011.6  284.39  5019.3  293.82  5024.5  283.28  5032.2  293.89  5073.4  293.96
  5094.1  290.89  5114.7  293.60  5166.2  293.62  5189.4  295.04  5197.1  296.45
  5248.7  299.23  5271.9  301.42  5286.6  304.40  5341.4  313.37  5372.4  316.29
#Mann=6,-1,0
  4848.3    0.12       0  4883.6    0.16       0  4933.6    0.12       0
  4975.1    0.07       0  4981.1    0.12       0  5286.6    0.16       0
Bank Sta=4975.1,4981.1
Exp/Cntr=0.3,0.1

Type RM Length L Ch R = 1,10784,494,494,494
BEGIN DESCRIPTION:
UNT 0299 IN LACR 19.0
END DESCRIPTION:
XS GIS Cut Line= 2
      3656999.60     10688960.22      3656697.29     10689969.73
#Sta/Elev= 30
  4591.7  312.04  4633.4  310.59  4679.6  304.53  4685.6  302.01  4712.7  297.14
  4758.7  291.62  4778.9  290.42  4797.7  291.27  4855.5  291.78  4863.1  290.30
  4873.5  291.70  4915.3  292.64  4977.9  292.02  4987.8  285.91  4993.0  291.43
  4995.8  280.51  4998.5  280.01  5001.8  280.51  5019.7  287.61  5026.1  288.11
  5031.4  291.15  5059.2  294.66  5064.4  294.02  5118.0  298.32  5268.2  312.04
  5385.0  316.21  5426.8  315.69  5444.1  316.89  5579.0  318.18  5645.5  319.29
#Mann=6,-1,0
  4591.7    0.16       0  4797.7    0.12       0  4995.8    0.07       0
  5001.8    0.12       0  5118.0    0.16       0  5579.0    0.05       0
Bank Sta=4995.8,5001.8
Exp/Cntr=0.3,0.1

Type RM Length L Ch R = 1,10290,448,448,448
BEGIN DESCRIPTION:
UNT 0299 IN LACR 18.0
END DESCRIPTION:
XS GIS Cut Line= 3
      3656649.59     10688860.22      3656499.61     10689160.19
      3656099.59     10689410.20
#Sta/Elev= 30
  4678.6  315.36  4698.9  314.23  4731.7  312.33  4782.0  306.67  4798.8  306.28
  4804.3  304.38  4812.7  304.28  4849.1  298.61  4881.8  295.62  4960.9  289.10
  4969.3  290.64  4977.6  288.15  4983.2  289.36  4991.6  284.12  4997.0  277.23
  4999.7  276.73  5003.0  277.23  5005.6  277.84  5011.2  287.26  5016.9  287.26
  5027.5  290.33  5118.9  289.16  5173.8  288.56  5179.7  286.12  5195.0  284.82
  5202.7  288.08  5210.3  288.64  5261.6  288.81  5404.9  301.11  5485.7  313.37
#Mann=6,-1,0
  4678.6    0.05       0  4698.9    0.16       0  4881.8    0.12       0
  4997.0    0.07       0  5003.0    0.12       0  5118.9    0.16       0
Bank Sta=4997,5003
Exp/Cntr=0.3,0.1

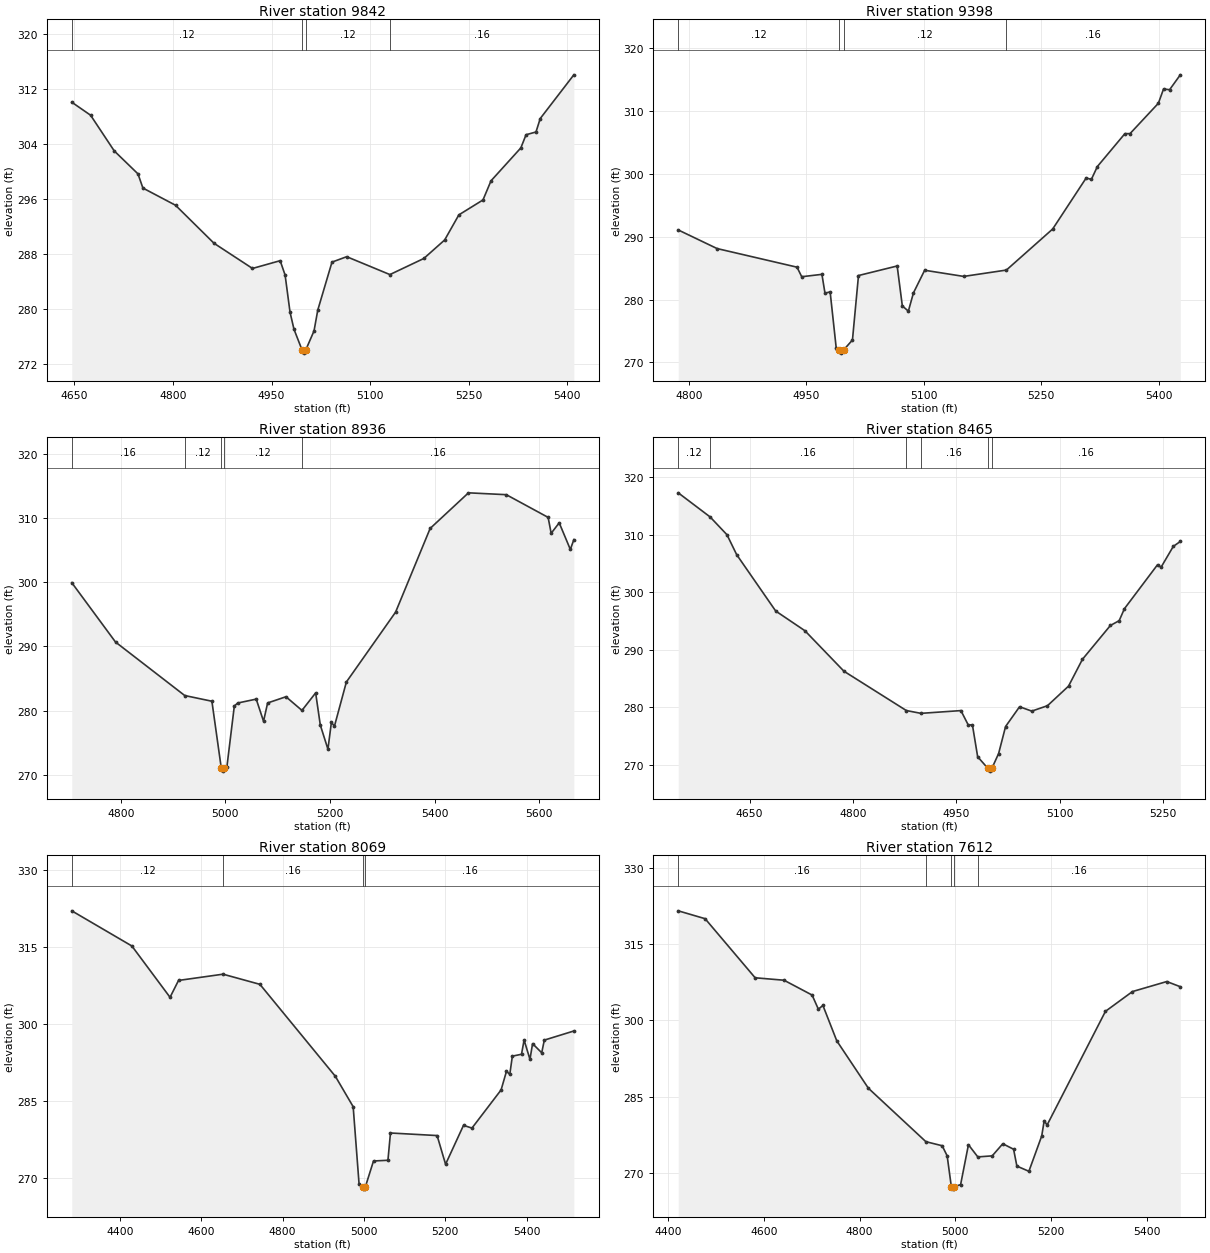
Type RM Length L Ch R = 1,9842,444,444,444
BEGIN DESCRIPTION:
UNT 0299 IN LACR 17.0
END DESCRIPTION:
XS GIS Cut Line= 3
      3656449.62     10688710.18      3656149.61     10688910.19
      3655949.60     10689260.20
#Sta/Elev= 30
  4646.1  310.03  4674.7  308.14  4710.7  302.95  4746.8  299.61  4754.3  297.55
  4803.9  295.05  4862.5  289.52  4921.0  285.86  4963.1  286.99  4970.6  284.90
  4978.1  279.50  4984.1  277.02  4996.2  274.05  4998.9  273.55  5002.2  274.05
  5014.6  276.78  5020.3  279.81  5041.9  286.78  5064.3  287.57  5130.0  284.97
  5181.6  287.31  5213.3  290.00  5234.9  293.65  5271.6  295.82  5283.8  298.60
  5329.2  303.39  5337.1  305.30  5352.2  305.70  5358.7  307.66  5409.8  314.01
#Mann=4,-1,0
  4646.1    0.12       0  4996.2    0.07       0  5002.2    0.12       0
  5130.0    0.16       0
Bank Sta=4996.2,5002.2
Exp/Cntr=0.3,0.1

Type RM Length L Ch R = 1,9398,462,462,462
BEGIN DESCRIPTION:
UNT 0299 IN LACR 16.0
END DESCRIPTION:
XS GIS Cut Line= 3
      3655999.59     10688510.20      3655849.61     10688610.19
      3655549.63     10688960.16
#Sta/Elev= 30
  4786.5  291.07  4836.1  288.11  4938.2  285.15  4944.2  283.63  4970.0  284.01
  4973.9  281.02  4980.5  281.22  4988.2  272.36  4991.7  271.98  4994.5  271.48
  4997.7  271.98  5009.0  273.57  5016.7  283.82  5066.1  285.34  5072.7  278.98
  5080.4  278.16  5086.9  281.06  5101.2  284.66  5151.1  283.68  5205.6  284.69
  5264.7  291.22  5307.5  299.34  5314.1  299.11  5321.8  301.16  5356.9  306.38
  5363.5  306.39  5399.7  311.22  5406.3  313.49  5414.0  313.37  5427.7  315.74
#Mann=4,-1,0
  4786.5    0.12       0  4991.7    0.07       0  4997.7    0.12       0
  5205.6    0.16       0
Bank Sta=4991.7,4997.7
Exp/Cntr=0.3,0.1

Type RM Length L Ch R = 1,8936,471,471,471
BEGIN DESCRIPTION:
UNT 0299 IN LACR 15.0
END DESCRIPTION:
XS GIS Cut Line= 3
      3655738.99     10688101.61      3655457.72     10688431.50
      3655009.78     10688709.29
#Sta/Elev= 30
  4706.0  299.94  4789.7  290.68  4922.1  282.34  4974.1  281.45  4992.0  271.05
  4994.7  270.55  4998.0  271.05  5002.7  271.14  5017.0  280.70  5023.5  281.17
  5058.9  281.78  5072.9  278.33  5080.7  281.18  5115.8  282.15  5146.4  280.02
  5172.6  282.75  5181.5  277.74  5196.1  273.97  5202.7  278.14  5208.6  277.57
  5231.4  284.45  5325.6  295.35  5391.7  308.40  5465.0  313.95  5537.4  313.66
  5617.4  310.12  5623.2  307.64  5638.6  309.27  5659.9  305.12  5666.6  306.65
#Mann=5,-1,0
  4706.0    0.16       0  4922.1    0.12       0  4992.0    0.07       0
  4998.0    0.12       0  5146.4    0.16       0
Bank Sta=4992,4998
Exp/Cntr=0.3,0.1

Type RM Length L Ch R = 1,8465,396,396,396
BEGIN DESCRIPTION:
UNT 0299 IN LACR 14.0
END DESCRIPTION:
XS GIS Cut Line= 3
      3655449.58     10687860.22      3655149.61     10688160.19
      3655099.60     10688460.22
#Sta/Elev= 30
  4546.6  317.30  4592.8  313.11  4617.3  310.01  4631.4  306.54  4688.0  296.74
  4730.4  293.31  4787.0  286.27  4877.5  279.43  4898.7  278.94  4956.7  279.42
  4967.3  276.93  4973.4  276.93  4981.0  271.39  4995.7  269.39  4998.5  268.89
  5001.7  269.39  5011.4  271.95  5021.5  276.65  5041.8  280.09  5059.5  279.33
  5082.3  280.27  5112.8  283.67  5133.0  288.34  5173.6  294.23  5186.3  295.06
  5193.9  297.14  5242.0  304.80  5247.1  304.36  5264.8  307.98  5275.0  308.84
#Mann=6,-1,0
  4546.6    0.12       0  4592.8    0.16       0  4877.5    0.12       0
  4898.7    0.16       0  4995.7    0.07       0  5001.7    0.16       0
Bank Sta=4995.7,5001.7
Exp/Cntr=0.3,0.1

Type RM Length L Ch R = 1,8069,457,457,457
BEGIN DESCRIPTION:
UNT 0299 IN LACR 13.0
END DESCRIPTION:
XS GIS Cut Line= 3
      3655635.82     10687468.84      3654875.40     10688036.55
      3654698.30     10688260.53
#Sta/Elev= 30
  4281.5  322.13  4429.3  315.27  4523.1  305.26  4544.0  308.55  4653.4  309.77
  4744.1  307.79  4929.6  289.85  4973.4  283.92  4988.0  268.75  4997.6  268.34
  5000.3  267.84  5003.6  268.34  5023.4  273.33  5058.9  273.47  5065.1  278.79
  5179.8  278.29  5200.6  272.69  5244.7  280.28  5265.5  279.75  5337.1  287.19
  5350.4  290.84  5358.5  290.23  5364.8  293.78  5387.3  294.15  5393.7  296.93
  5408.1  293.15  5414.5  296.22  5437.0  294.44  5443.4  296.91  5516.0  298.69
#Mann=4,-1,0
  4281.5    0.12       0  4653.4    0.16       0  4997.6    0.07       0
  5003.6    0.16       0
Bank Sta=4997.6,5003.6
Exp/Cntr=0.3,0.1

Type RM Length L Ch R = 1,7612,488,488,488
BEGIN DESCRIPTION:
UNT 0299 IN LACR 12.0
END DESCRIPTION:
XS GIS Cut Line= 3
      3654969.14     10687182.42      3654646.24     10687796.96
      3654536.92     10688135.33
#Sta/Elev= 30
  4420.7  321.58  4476.9  320.03  4581.5  308.40  4641.9  307.92  4700.6  305.00
  4713.7  302.22  4723.2  302.96  4752.2  295.99  4818.3  286.66  4938.5  276.14
  4972.6  275.34  4983.0  273.35  4991.7  267.30  4994.4  266.80  4997.7  267.30
  5011.1  267.68  5027.5  275.54  5047.1  273.14  5077.2  273.35  5099.3  275.73
  5121.9  274.65  5128.8  271.33  5153.9  270.31  5180.7  277.26  5185.9  280.27
  5191.9  279.41  5314.0  301.80  5370.5  305.69  5442.2  307.66  5470.5  306.64
#Mann=5,-1,0
  4420.7    0.16       0  4938.5    0.12       0  4991.7    0.07       0
  4997.7    0.12       0  5047.1    0.16       0
Bank Sta=4991.7,4997.7
Exp/Cntr=0.3,0.1

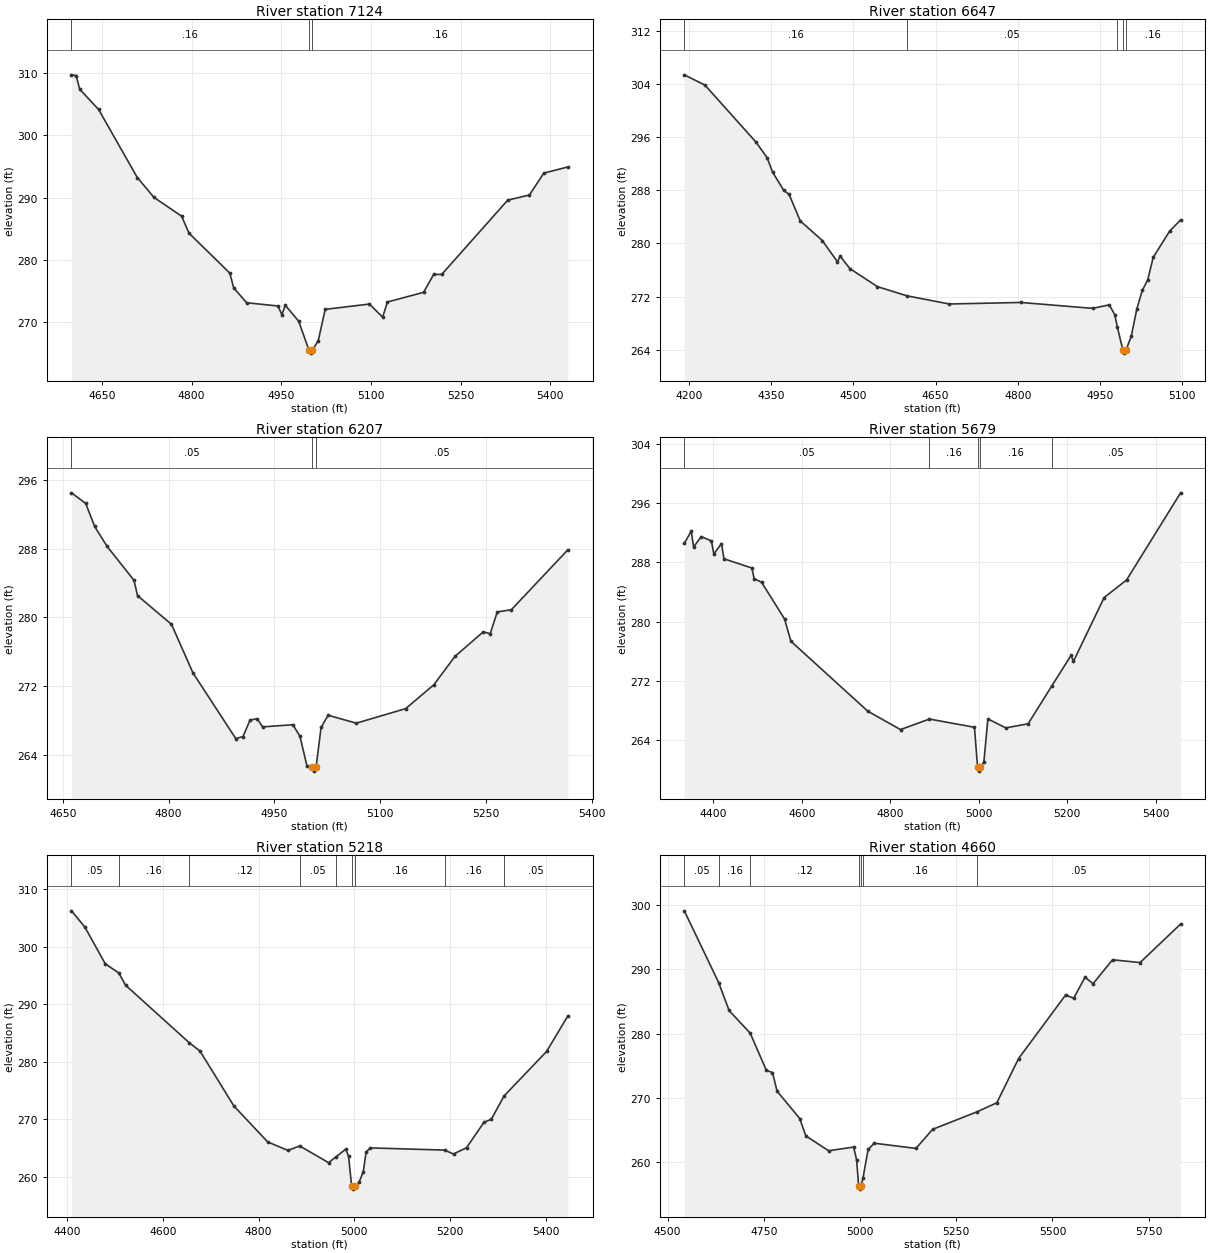
Type RM Length L Ch R = 1,7124,477,477,477
BEGIN DESCRIPTION:
UNT 0299 IN LACR 11.0
END DESCRIPTION:
XS GIS Cut Line= 3
      3654499.61     10687110.18      3654299.61     10687460.19
      3654149.62     10687860.17
#Sta/Elev= 30
  4599.0  309.69  4606.9  309.57  4612.7  307.39  4644.4  304.13  4709.1  293.22
  4737.2  290.02  4783.3  287.02  4795.5  284.31  4863.9  277.89  4870.4  275.53
  4892.0  273.14  4944.5  272.62  4951.0  271.22  4956.8  272.72  4979.1  270.19
  4996.2  265.56  4999.0  265.06  5002.2  265.56  5011.9  267.08  5023.5  272.08
  5097.4  272.93  5119.6  270.83  5127.6  273.26  5188.1  274.81  5205.0  277.68
  5218.4  277.68  5328.8  289.59  5365.2  290.42  5389.3  293.93  5429.3  294.91
#Mann=3,-1,0
  4599.0    0.16       0  4996.2    0.07       0  5002.2    0.16       0
Bank Sta=4996.2,5002.2
Exp/Cntr=0.3,0.1

Type RM Length L Ch R = 1,6647,440,440,440
BEGIN DESCRIPTION:
UNT 0299 IN LACR 10.0
END DESCRIPTION:
XS GIS Cut Line= 3
      3654099.60     10686810.24      3653999.61     10687610.19
      3653999.61     10687710.21
#Sta/Elev= 30
  4191.2  305.40  4228.9  303.85  4322.2  295.25  4342.3  292.93  4352.4  290.74
  4372.6  288.02  4382.6  287.39  4402.8  283.41  4443.1  280.45  4470.8  277.24
  4475.8  278.08  4493.5  276.22  4543.9  273.50  4597.7  272.12  4674.9  270.89
  4805.9  271.12  4936.9  270.23  4967.1  270.76  4977.2  269.28  4981.8  267.44
  4991.9  263.99  4994.6  263.49  4997.9  263.99  5007.4  266.06  5017.4  270.11
  5027.4  272.93  5037.4  274.54  5047.4  277.92  5077.4  281.86  5097.4  283.55
#Mann=5,-1,0
  4191.2    0.16       0  4597.7    0.05       0  4981.8    0.16       0
  4991.9    0.07       0  4997.9    0.16       0
Bank Sta=4991.9,4997.9
Exp/Cntr=0.3,0.1

Type RM Length L Ch R = 1,6207,528,528,528
BEGIN DESCRIPTION:
UNT 0299 IN LACR 9.0
END DESCRIPTION:
XS GIS Cut Line= 3
      3653599.62     10687110.24      3653649.61     10687410.19
      3653649.61     10687810.20
#Sta/Elev= 30
  4662.1  294.47  4682.3  293.24  4695.0  290.56  4712.7  288.24  4750.8  284.31
  4755.8  282.53  4804.0  279.19  4834.4  273.56  4895.2  265.92  4905.4  266.15
  4915.5  268.08  4925.6  268.23  4933.2  267.28  4976.2  267.53  4986.2  266.20
  4996.2  262.73  5003.2  262.64  5005.9  262.14  5009.2  262.64  5016.2  267.22
  5026.2  268.63  5066.2  267.71  5136.2  269.40  5176.2  272.17  5206.2  275.47
  5246.2  278.31  5256.2  278.11  5266.2  280.63  5286.2  280.89  5366.2  287.84
#Mann=3,-1,0
  4662.1    0.05       0  5003.2    0.03       0  5009.2    0.05       0
Bank Sta=5003.2,5009.2
Exp/Cntr=0.3,0.1

Type RM Length L Ch R = 1,5679,461,461,461
BEGIN DESCRIPTION:
UNT 0299 IN LACR 8.0
END DESCRIPTION:
XS GIS Cut Line= 3
      3653471.61     10686862.05      3653214.66     10687410.67
      3653291.05     10687921.08
#Sta/Elev= 30
  4334.2  290.54  4349.7  292.19  4355.2  290.07  4372.5  291.46  4395.4  290.87
  4400.9  289.12  4418.2  290.52  4423.7  288.47  4486.7  287.23  4492.2  285.78
  4508.8  285.31  4560.7  280.37  4575.1  277.36  4748.9  267.93  4822.9  265.45
  4888.3  266.87  4990.1  265.76  4997.2  260.35  4999.9  259.85  5003.2  260.35
  5011.3  261.05  5020.4  266.89  5060.9  265.68  5111.4  266.23  5165.4  271.38
  5208.7  275.47  5213.7  274.63  5283.3  283.25  5333.9  285.61  5456.1  297.36
#Mann=5,-1,0
  4334.2    0.05       0  4888.3    0.16       0  4997.2    0.07       0
  5003.2    0.16       0  5165.4    0.05       0
Bank Sta=4997.2,5003.2
Exp/Cntr=0.3,0.1

Type RM Length L Ch R = 1,5218,558,558,558
BEGIN DESCRIPTION:
UNT 0299 IN LACR 7.0
END DESCRIPTION:
XS GIS Cut Line= 3
      3652549.64     10687010.22      3652949.61     10687410.19
      3653199.59     10687810.15
#Sta/Elev= 30
  4408.9  306.28  4437.1  303.43  4479.6  297.05  4507.7  295.48  4522.0  293.34
  4655.4  283.31  4677.6  281.88  4748.3  272.34  4819.0  266.08  4861.4  264.60
  4886.0  265.38  4946.3  262.47  4961.0  263.44  4982.2  264.83  4988.1  263.55
  4994.5  258.37  4997.3  257.87  5000.5  258.37  5009.9  259.04  5018.8  260.91
  5024.7  264.31  5033.5  265.04  5188.8  264.66  5207.4  263.98  5234.6  265.07
  5271.1  269.50  5286.5  270.03  5313.1  274.08  5402.0  281.82  5446.2  287.97
#Mann=9,-1,0
  4408.9    0.05       0  4507.7    0.16       0  4655.4    0.12       0
  4886.0    0.05       0  4961.0    0.16       0  4994.5   0.035       0
  5000.5    0.16       0  5188.8    0.16       0  5313.1    0.05       0
Bank Sta=4994.5,5000.5
Exp/Cntr=0.3,0.1

Type RM Length L Ch R = 1,4660,363,363,363
BEGIN DESCRIPTION:
UNT 0299 IN LACR 6.0
END DESCRIPTION:
XS GIS Cut Line= 3
      3652449.60     10687210.18      3652756.33     10687754.42
      3653300.61     10688135.76
#Sta/Elev= 30
  4543.6  299.14  4632.9  287.94  4659.9  283.60  4714.8  280.06  4756.7  274.27
  4772.6  273.93  4784.7  271.01  4843.4  266.76  4859.3  264.05  4918.5  261.73
  4983.5  262.31  4991.3  260.27  4996.5  256.25  4999.2  255.75  5002.5  256.25
  5007.6  257.43  5021.1  261.94  5037.0  262.91  5145.3  262.10  5188.9  265.08
  5304.8  267.82  5355.4  269.21  5412.0  276.11  5534.1  286.01  5555.0  285.51
  5584.6  288.78  5605.6  287.79  5656.1  291.51  5727.6  291.07  5832.9  297.08
#Mann=7,-1,0
  4543.6    0.05       0  4632.9    0.16       0  4714.8    0.12       0
  4996.5    0.07       0  5002.5    0.12       0  5007.6    0.16       0
  5304.8    0.05       0
Bank Sta=4996.5,5002.5
Exp/Cntr=0.3,0.1