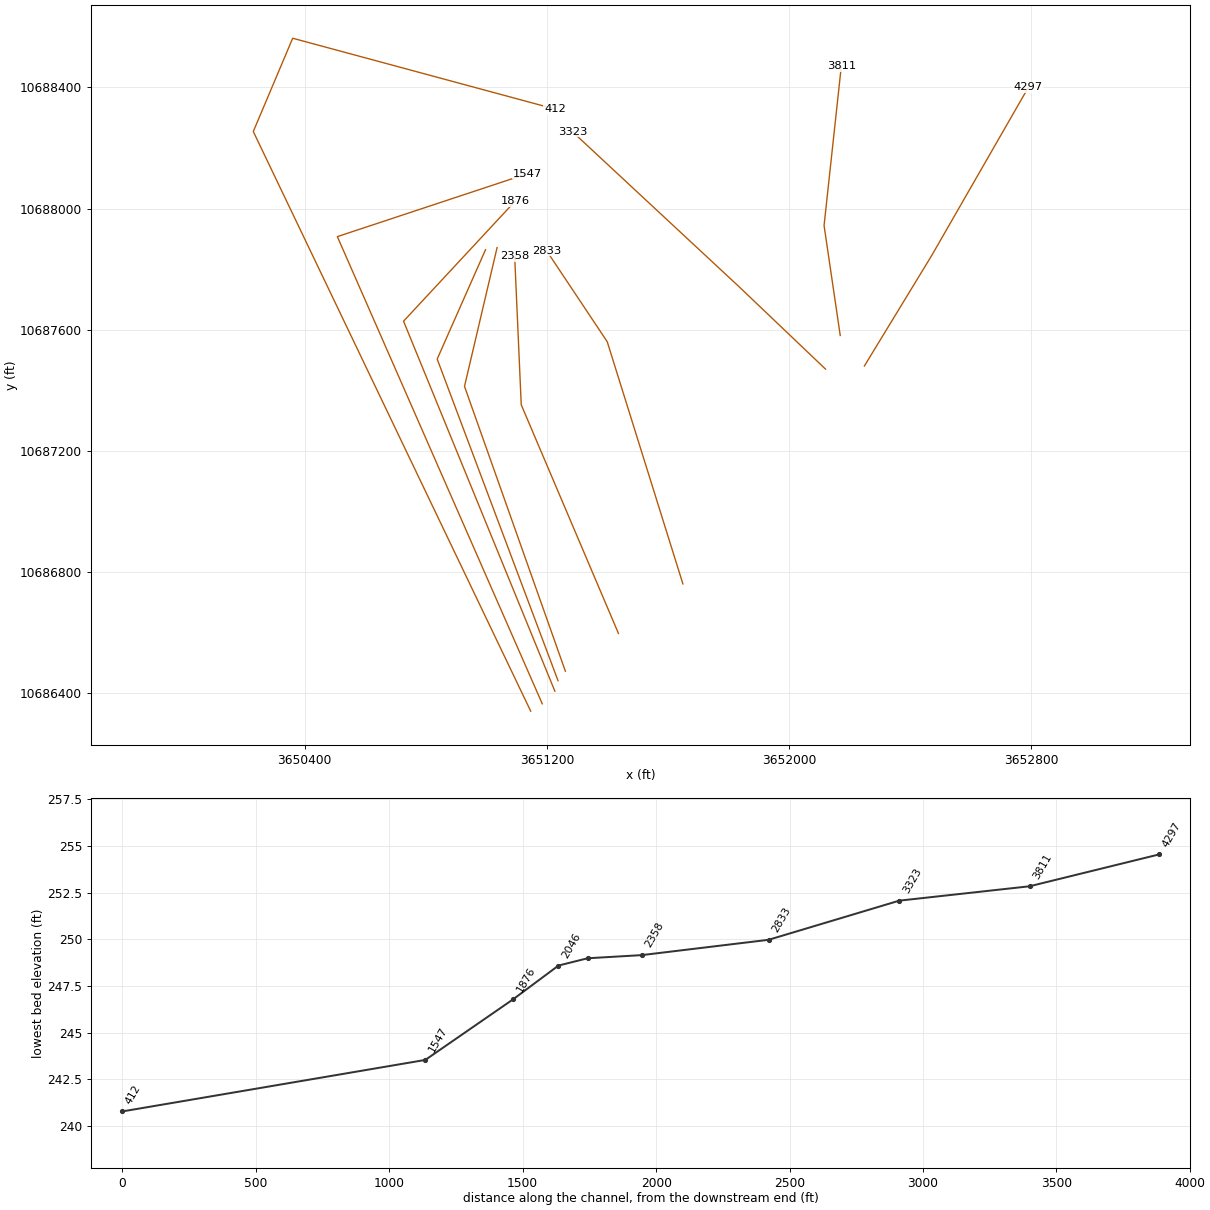
HEC-RAS study UNT 0299 IN LACR.prj: UNT 0299 IN LACR Base Level Engineering

--- UNT 0299 IN LACR.g01 (geometry) --- (continued)

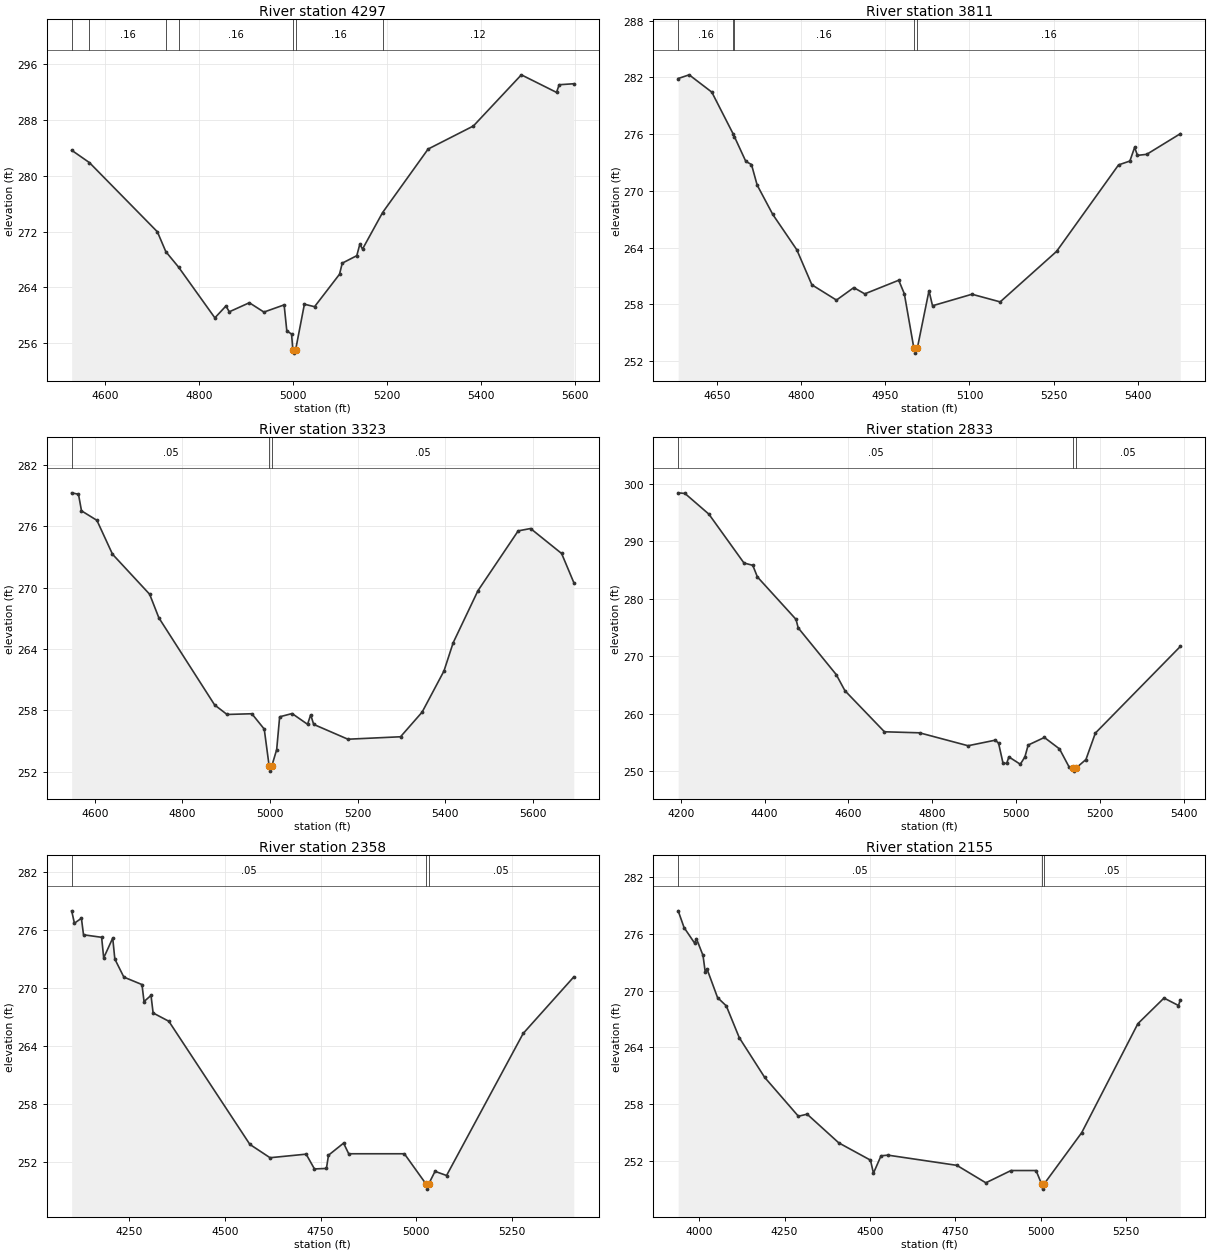
Type RM Length L Ch R = 1,4297,486,486,486
BEGIN DESCRIPTION:
UNT 0299 IN LACR 5.0
END DESCRIPTION:
XS GIS Cut Line= 3
      3652249.36     10687480.07      3652471.61     10687844.69
      3652791.07     10688400.28
#Sta/Elev= 30
  4529.0  283.66  4566.9  281.88  4711.3  271.96  4729.3  269.11  4756.4  266.89
  4833.6  259.61  4857.1  261.31  4864.3  260.48  4906.9  261.78  4937.9  260.44
  4980.9  261.47  4986.6  257.74  4996.7  257.29  4999.4  255.05  5002.2  254.55
  5005.4  255.05  5024.0  261.57  5045.6  261.21  5098.7  265.87  5104.5  267.46
  5135.4  268.53  5141.9  270.18  5147.6  269.48  5190.3  274.72  5287.1  283.83
  5383.4  287.14  5485.4  294.48  5560.2  291.96  5565.9  293.06  5596.9  293.20
#Mann=7,-1,0
  4529.0    0.05       0  4566.9    0.16       0  4729.3    0.12       0
  4756.4    0.16       0  4999.4    0.07       0  5005.4    0.16       0
  5190.3    0.12       0
Bank Sta=4999.4,5005.4
Exp/Cntr=0.3,0.1

Type RM Length L Ch R = 1,3811,488,488,488
BEGIN DESCRIPTION:
UNT 0299 IN LACR 4.0
END DESCRIPTION:
XS GIS Cut Line= 3
      3652169.53     10687580.78      3652116.11     10687944.19
      3652173.00     10688469.70
#Sta/Elev= 30
  4580.3  281.89  4599.9  282.28  4640.3  280.45  4678.4  276.03  4680.7  275.73
  4701.0  273.12  4711.1  272.79  4721.2  270.62  4749.1  267.51  4792.0  263.77
  4818.8  260.07  4862.7  258.45  4893.6  259.77  4913.2  259.11  4973.8  260.55
  4983.8  259.12  5000.9  253.34  5003.7  252.84  5006.9  253.34  5027.8  259.44
  5034.1  257.85  5104.5  259.07  5154.8  258.26  5255.4  263.60  5366.0  272.75
  5386.2  273.16  5394.7  274.61  5399.8  273.76  5416.3  273.87  5476.2  276.05
#Mann=5,-1,0
  4580.3    0.16       0  4678.4    0.12       0  4680.7    0.16       0
  5000.9    0.07       0  5006.9    0.16       0
Bank Sta=5000.9,5006.9
Exp/Cntr=0.3,0.1

Type RM Length L Ch R = 1,3323,490,490,490
BEGIN DESCRIPTION:
UNT 0299 IN LACR 3.0
END DESCRIPTION:
XS GIS Cut Line= 3
      3652120.91     10687469.70      3651833.96     10687743.01
      3651284.32     10688254.21
#Sta/Elev= 30
  4546.9  279.28  4562.5  279.14  4569.4  277.52  4604.6  276.59  4640.2  273.28
  4725.1  269.36  4746.1  267.06  4873.5  258.54  4901.8  257.61  4958.5  257.68
  4986.8  256.18  4998.0  252.57  5000.8  252.07  5004.0  252.57  5015.2  254.17
  5022.0  257.38  5050.4  257.70  5085.7  256.65  5092.9  257.58  5099.7  256.64
  5177.9  255.19  5298.1  255.43  5347.4  257.84  5397.3  261.86  5418.3  264.62
  5474.9  269.71  5566.8  275.56  5595.1  275.79  5666.0  273.35  5693.8  270.51
#Mann=3,-1,0
  4546.9    0.05       0  4998.0    0.03       0  5004.0    0.05       0
Bank Sta=4998,5004
Exp/Cntr=0.3,0.1

Type RM Length L Ch R = 1,2833,475,475,475
BEGIN DESCRIPTION:
UNT 0299 IN LACR 2.0
END DESCRIPTION:
XS GIS Cut Line= 3
      3651649.61     10686760.19      3651399.61     10687560.19
      3651199.61     10687860.19
#Sta/Elev= 30
  4193.6  298.42  4209.8  298.31  4266.9  294.71  4350.7  286.20  4371.7  285.80
  4382.7  283.78  4474.9  276.39  4480.1  274.91  4570.8  266.79  4591.7  263.97
  4686.0  256.82  4769.8  256.64  4885.6  254.39  4950.6  255.36  4958.4  254.85
  4968.9  251.41  4977.8  251.30  4983.0  252.45  5010.3  251.17  5021.3  252.44
  5029.1  254.51  5067.8  255.83  5103.9  253.84  5126.4  250.75  5136.9  250.47
  5139.7  249.97  5142.9  250.47  5167.0  251.99  5189.5  256.59  5392.3  271.67
#Mann=3,-1,0
  4193.6    0.05       0  5136.9    0.03       0  5142.9    0.05       0
Bank Sta=5136.9,5142.9
Exp/Cntr=0.3,0.1

Type RM Length L Ch R = 1,2358,203,203,203
BEGIN DESCRIPTION:
Mapping XS 944e3cfd
END DESCRIPTION:
XS GIS Cut Line= 3
      3651436.67     10686596.55      3651115.49     10687351.78
      3651093.78     10687842.21
#Sta/Elev= 30
  4099.7  277.95  4107.0  276.67  4125.2  277.18  4130.7  275.47  4178.0  275.21
  4183.4  273.08  4207.0  275.13  4212.5  272.96  4236.1  271.09  4283.4  270.32
  4288.8  268.56  4307.0  269.20  4312.5  267.38  4353.6  266.52  4565.2  253.78
  4617.9  252.40  4712.2  252.77  4733.9  251.24  4765.2  251.29  4770.6  252.66
  4810.0  253.91  4823.4  252.81  4968.8  252.81  5025.9  249.65  5028.7  249.15
  5031.9  249.65  5048.9  250.99  5079.0  250.56  5279.1  265.26  5411.3  271.11
#Mann=3,-1,0
  4099.7    0.05       0  5025.9    0.03       0  5031.9    0.05       0
Bank Sta=5025.9,5031.9
Exp/Cntr=0.3,0.1

Type RM Length L Ch R = 1,2155,109,109,109
BEGIN DESCRIPTION:
Mapping XS 291acd27
END DESCRIPTION:
XS GIS Cut Line= 3
      3651261.34     10686471.69      3650928.00     10687412.67
      3651035.65     10687871.02
#Sta/Elev= 30
  3938.8  278.46  3956.0  276.69  3986.9  275.04  3992.2  275.51  4011.5  273.73
  4017.8  272.01  4023.1  272.31  4054.0  269.27  4079.6  268.39  4117.6  265.02
  4191.8  260.82  4290.5  256.70  4316.1  256.92  4408.7  253.88  4501.4  252.05
  4510.1  250.67  4532.3  252.51  4552.5  252.58  4754.1  251.50  4839.0  249.65
  4912.6  250.95  4985.9  250.95  5002.5  249.48  5005.3  248.98  5008.5  249.48
  5119.4  254.96  5283.8  266.51  5360.2  269.22  5402.6  268.43  5407.9  269.03
#Mann=3,-1,0
  3938.8    0.05       0  5002.5    0.03       0  5008.5    0.05       0
Bank Sta=5002.5,5008.5
Exp/Cntr=0.3,0.1

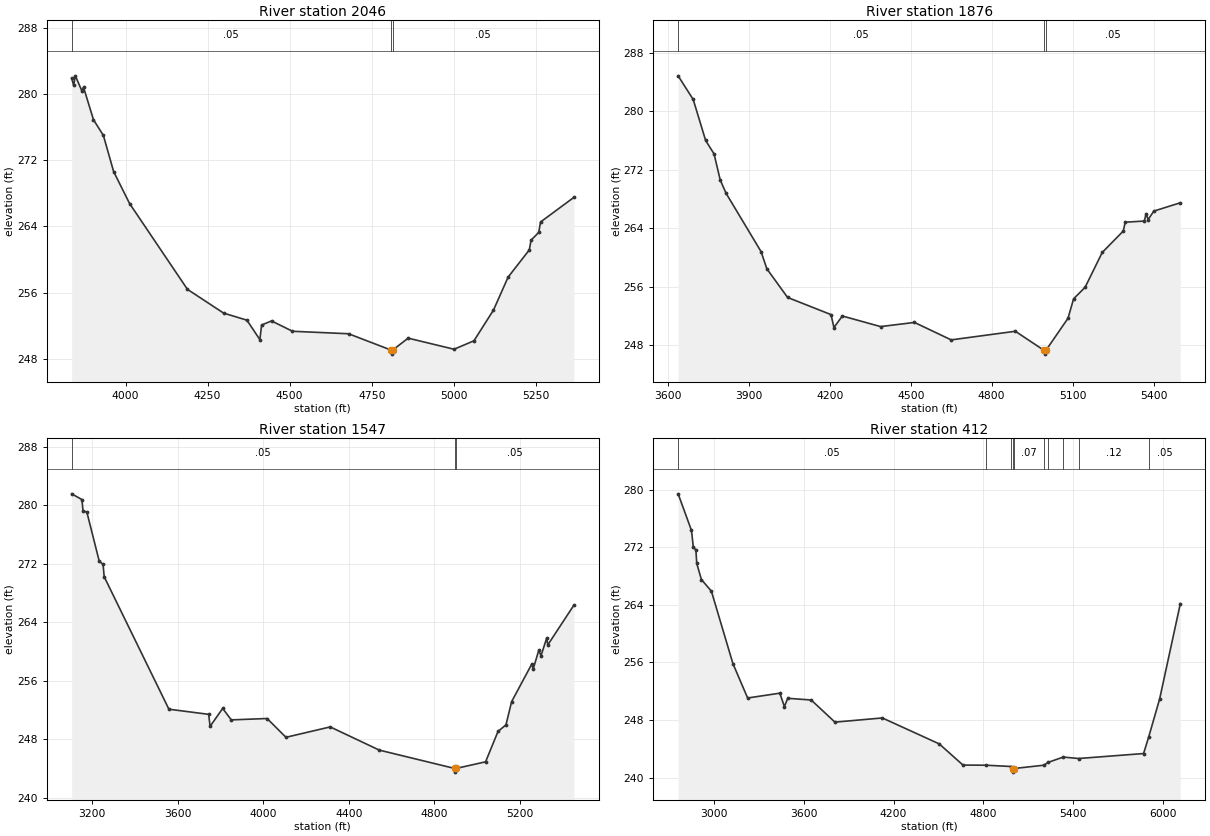
Type RM Length L Ch R = 1,2046,170,170,170
BEGIN DESCRIPTION:
Mapping XS e84a02d2
END DESCRIPTION:
XS GIS Cut Line= 3
      3651237.04     10686440.42      3650837.72     10687502.94
      3650997.43     10687864.02
#Sta/Elev= 30
  3835.9  281.92  3841.9  281.04  3847.2  282.19  3866.8  280.39  3872.1  280.81
  3902.4  276.89  3932.6  274.99  3963.8  270.63  4012.6  266.76  4188.7  256.41
  4299.0  253.54  4369.8  252.69  4409.3  250.34  4414.6  252.10  4444.8  252.60
  4508.7  251.35  4679.6  251.05  4808.2  249.09  4811.0  248.59  4814.2  249.09
  4861.0  250.52  5000.8  249.18  5061.5  250.20  5121.0  253.91  5165.6  257.89
  5230.1  261.17  5235.5  262.35  5258.8  263.28  5264.3  264.54  5365.8  267.51
#Mann=3,-1,0
  3835.9    0.05       0  4808.2    0.03       0  4814.2    0.05       0
Bank Sta=4808.2,4814.2
Exp/Cntr=0.3,0.1

Type RM Length L Ch R = 1,1876,329,329,329
BEGIN DESCRIPTION:
Mapping XS c8446046
END DESCRIPTION:
XS GIS Cut Line= 3
      3651226.61     10686405.74      3650726.61     10687627.94
      3651094.65     10688023.75
#Sta/Elev= 30
  3638.1  284.88  3693.9  281.65  3740.1  276.03  3771.3  274.19  3794.2  270.61
  3815.8  268.80  3945.4  260.82  3967.0  258.46  4043.8  254.54  4204.7  252.19
  4215.5  250.42  4246.7  252.00  4388.4  250.55  4513.8  251.12  4650.1  248.73
  4887.8  249.91  4994.8  247.28  4997.5  246.78  5000.8  247.28  5082.8  251.68
  5103.8  254.36  5146.3  255.93  5209.8  260.70  5288.0  263.64  5294.8  264.84
  5365.7  265.00  5372.5  266.01  5379.9  265.20  5400.9  266.36  5499.1  267.50
#Mann=3,-1,0
  3638.1    0.05       0  4994.8    0.03       0  5000.8    0.05       0
Bank Sta=4994.8,5000.8
Exp/Cntr=0.3,0.1

Type RM Length L Ch R = 1,1547,1135,1135,1135
BEGIN DESCRIPTION:
Mapping XS bfebfbe9
END DESCRIPTION:
XS GIS Cut Line= 3
      3651184.94     10686364.06      3650507.85     10687907.34
      3651135.19     10688115.01
#Sta/Elev= 30
  3105.0  281.57  3152.8  280.79  3158.2  279.27  3176.1  279.07  3233.8  272.37
  3251.7  271.93  3257.1  270.23  3559.4  252.13  3745.1  251.43  3751.7  249.78
  3810.6  252.24  3850.7  250.67  4018.1  250.86  4106.2  248.29  4312.9  249.71
  4542.2  246.54  4894.5  244.03  4897.2  243.53  4900.5  244.03  5038.8  244.94
  5097.0  249.10  5134.0  249.99  5160.4  253.16  5255.5  258.35  5260.8  257.58
  5287.2  260.17  5297.8  259.45  5324.2  261.84  5329.5  260.92  5451.1  266.34
#Mann=3,-1,0
  3105.0    0.05       0  4894.5    0.03       0  4900.5    0.05       0
Bank Sta=4894.5,4900.5
Exp/Cntr=0.3,0.1

Type RM Length L Ch R = 1,412,0,0,0
BEGIN DESCRIPTION:
UNT 0299 IN LACR 1.0
END DESCRIPTION:
XS GIS Cut Line= 4
      3651146.75     10686339.76      3650230.07     10688254.56
      3650360.28     10688562.72      3651226.50     10688328.84
#Sta/Elev= 30
  2760.8  279.40  2850.0  274.32  2862.5  272.00  2879.6  271.60  2885.2  269.73
  2916.5  267.50  2983.0  265.89  3127.1  255.82  3225.2  251.06  3440.2  251.73
  3470.8  249.86  3493.0  251.02  3649.8  250.78  3808.4  247.71  4125.0  248.29
  4505.1  244.69  4663.7  241.75  4817.3  241.73  4987.0  241.55  4998.0  241.27
  5000.7  240.77  5004.0  241.27  5203.5  241.73  5232.3  242.12  5333.3  242.86
  5435.6  242.66  5870.1  243.35  5904.2  245.64  5977.5  250.93  6115.5  264.15
#Mann=10,-1,0
  2760.8    0.05       0  4817.3    0.12       0  4987.0    0.07       0
  4998.0    0.07       0  5004.0    0.07       0  5203.5    0.07       0
  5232.3    0.12       0  5333.3    0.07       0  5435.6    0.12       0
  5904.2    0.05       0
Bank Sta=4998,5004
Exp/Cntr=0.3,0.1

Chan Stop Cuts=-1