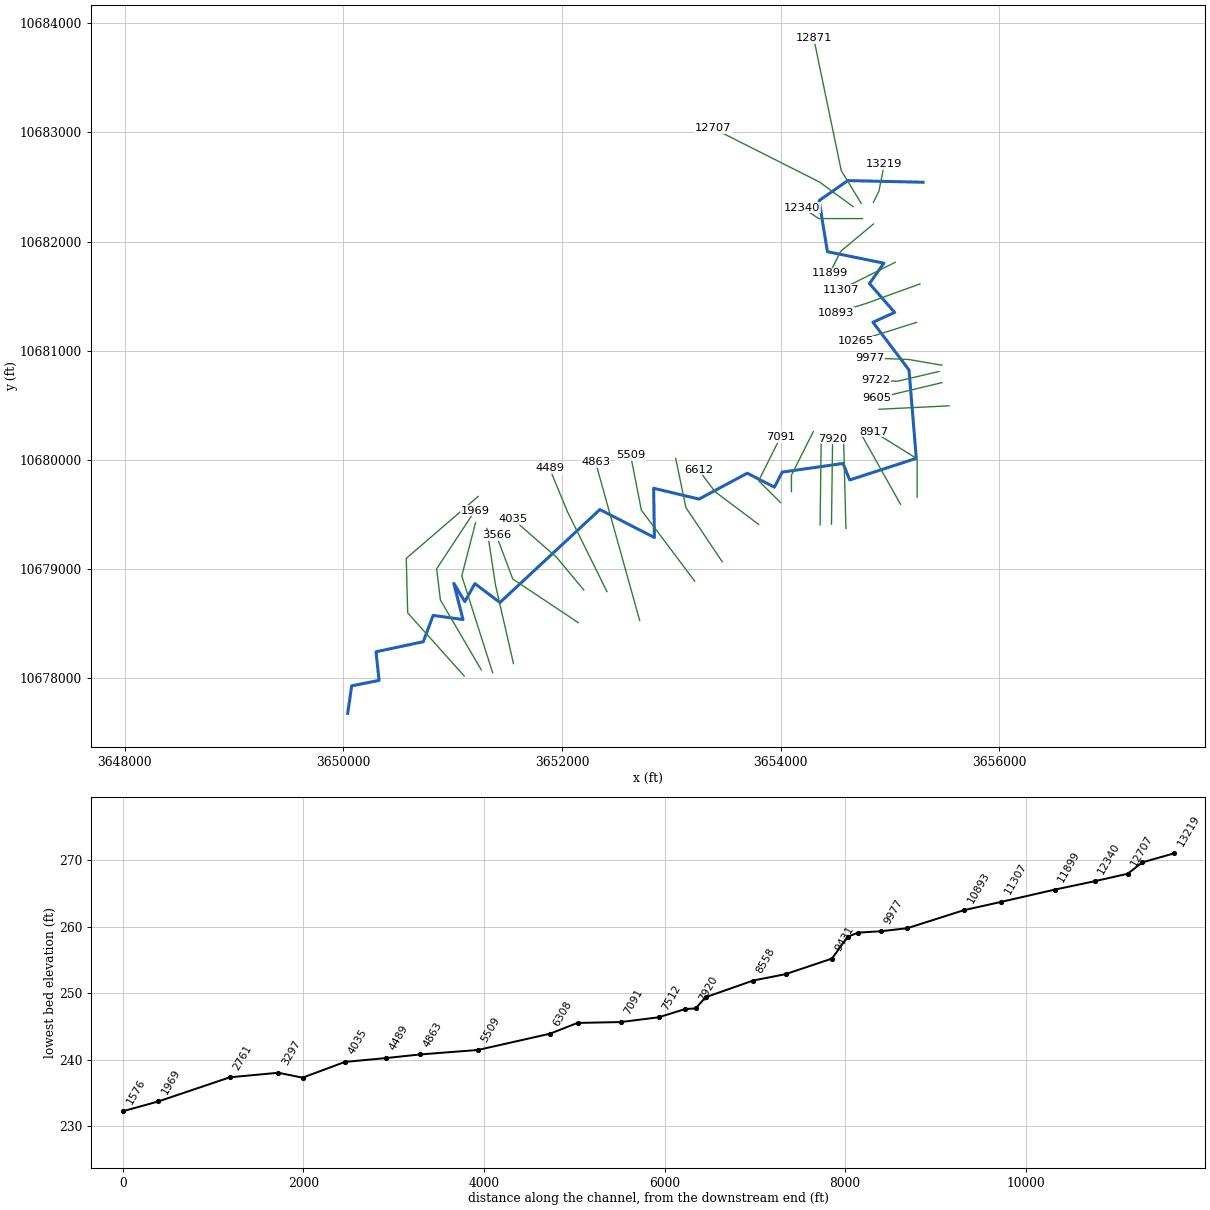
--- UNT 0302 IN LACR.prj (project) ---

Proj Title=UNT 0302 IN LACR Base Level Engineering
Current Plan=p01
Default Exp/Contr=0.3,0.1
English Units
Geom File=g01
Flow File=f01
Plan File=p01
Y Axis Title=Elevation
X Axis Title(PF)=Main Channel Distance
X Axis Title(XS)=Station
BEGIN DESCRIPTION:
UNT 0302 IN LACR
END DESCRIPTION:
DSS Export Rating Curves= 0
DSS Export Rating Curve Sorted= 0
DSS Export Volume Flow Curves= 0
DXF OffsetX= 0
DXF OffsetY= 0
DXF ScaleX= 1
DXF ScaleY= 10

--- UNT 0302 IN LACR.p01 (plan) ---

Plan Title=Multiple Run
Short Identifier=Multiple
Geom File=g01
Flow File=f01
Subcritical Flow
K Sum by GR= 0
Std Step Tol= 0.01
Critical Tol= 0.01
Num of Std Step Trials= 20
Max Error Tol= 0.3
Flow Tol Ratio= 0.001
Split Flow NTrial= 30
Split Flow Tol= 0.02
Split Flow Ratio= 0.02
Log Output Level= 0
Friction Slope Method= 1
Unsteady Friction Slope Method= 2
Unsteady Bridges Friction Slope Method= 1
Parabolic Critical Depth
Global Vel Dist=  1 , 1 , 1
Global Log Level= 0
CheckData=True
Encroach Param= -1, 0, 0, 0
BEGIN DESCRIPTION:
Multiple Run
END DESCRIPTION:

--- UNT 0302 IN LACR.f01 (steady flow) ---

Flow Title=Multiple
Program Version=4.10
Number of Profiles= 7
Profile Names=10-year,25-year,50-year,1pct_min,100-year,1pct_plu,500-year
River Rch & RM=UNT 0302 IN LACR,Reach-1         ,13219
     430     573     689     609     824    1114    1183
River Rch & RM=UNT 0302 IN LACR,Reach-1         ,12871
     562     759     921     820    1109    1500    1618
River Rch & RM=UNT 0302 IN LACR,Reach-1         ,8917
    1144    1600    1986    1806    2442    3302    3713
Boundary for River Rch & Prof#=UNT 0302 IN LACR,Reach-1         , 1
Up Type= 0
Dn Type= 3
Dn Slope=0.004
Boundary for River Rch & Prof#=UNT 0302 IN LACR,Reach-1         , 2
Up Type= 0
Dn Type= 3
Dn Slope=0.004
Boundary for River Rch & Prof#=UNT 0302 IN LACR,Reach-1         , 3
Up Type= 0
Dn Type= 3
Dn Slope=0.004
Boundary for River Rch & Prof#=UNT 0302 IN LACR,Reach-1         , 4
Up Type= 0
Dn Type= 3
Dn Slope=0.004
Boundary for River Rch & Prof#=UNT 0302 IN LACR,Reach-1         , 5
Up Type= 0
Dn Type= 3
Dn Slope=0.004
Boundary for River Rch & Prof#=UNT 0302 IN LACR,Reach-1         , 6
Up Type= 0
Dn Type= 3
Dn Slope=0.004
Boundary for River Rch & Prof#=UNT 0302 IN LACR,Reach-1         , 7
Up Type= 0
Dn Type= 3
Dn Slope=0.004
DSS Import GetInterval= 0
DSS Import GetPeak= 0
DSS Import FillOption= 0

--- UNT 0302 IN LACR.g01 (geometry) ---

Geom Title=Existing Conditions
Program Version=4.10

River Reach=UNT 0302 IN LACR,Reach-1
Reach XY= 30
      3655303.43     10682542.98      3654615.25       10682558.
      3654352.75       10682375.      3654428.75       10681907.
      3654945.25       10681802.      3654813.75       10681615.
        3655044.       10681351.      3654845.25       10681261.
      3655175.25       10680824.      3655242.25       10680015.
      3654632.75       10679817.        3654572.       10679968.
      3654015.25       10679889.        3653944.       10679751.
      3653695.25       10679879.        3653254.       10679642.
      3652838.75       10679741.      3652845.75       10679290.
       3652346.5       10679546.      3651432.25       10678695.
      3651203.25       10678868.        3651111.       10678703.
       3651010.5       10678870.      3651094.25       10678539.
      3650821.25       10678577.        3650731.       10678336.
       3650298.5       10678244.       3650326.5       10677982.
      3650075.75       10677932.       3650039.5       10677680.

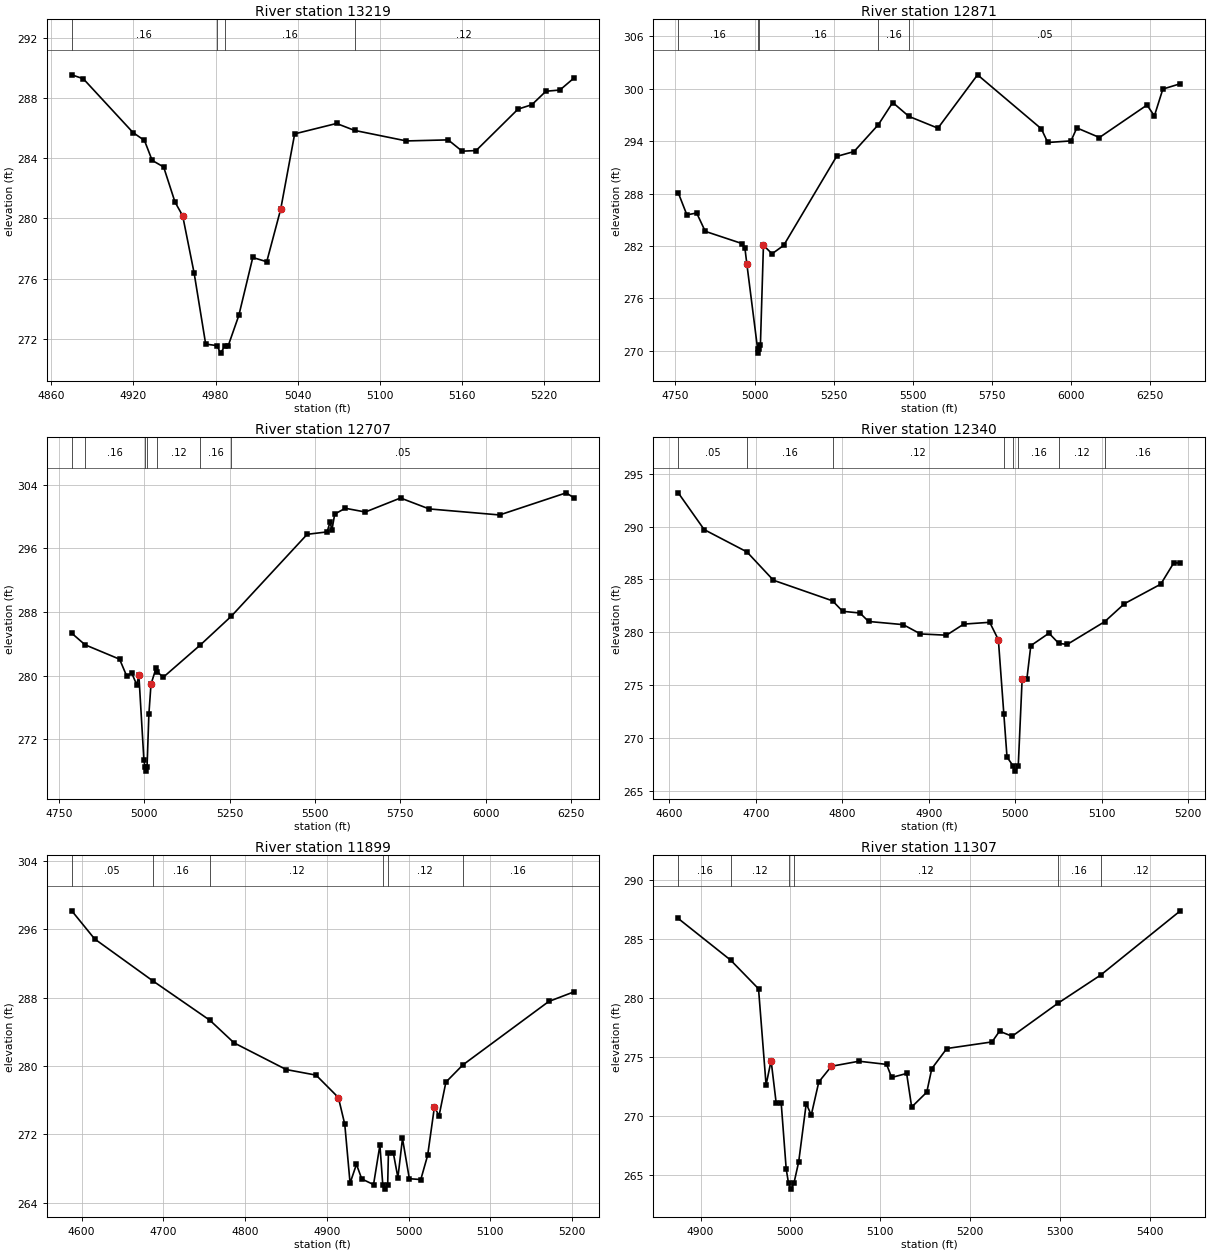
Type RM Length L Ch R = 1 ,13219   ,348,348,348
BEGIN DESCRIPTION:
UNT 0302 IN LACR 22.0
END DESCRIPTION:
XS GIS Cut Line= 3
      3654849.62     10682360.21      3654899.61     10682460.19
       3654949.6     10682710.16
#Sta/Elev= 30
    4875  289.54  4883.4  289.28  4919.7  285.71  4928.1  285.18  4933.7  283.86
  4942.1  283.42  4950.4  281.09    4956  280.18  4964.4  276.36  4972.8  271.66
    4981  271.56  4983.7  271.06    4987  271.56  4989.3  271.56    4997  273.56
  5007.2  277.41  5017.4  277.13  5027.6  280.62  5037.8  285.62  5068.4  286.31
  5081.5  285.85  5119.4  285.15  5149.9  285.22  5160.1  284.47  5170.3  284.51
  5200.9  287.26  5211.1  287.56  5221.3  288.45  5231.5  288.53  5241.7  289.32
#Mann= 4 ,-1 , 0
    4875     .16       0    4981     .07       0    4987     .16       0
  5081.5     .12       0
Bank Sta=4956,5027.6
XS Rating Curve= 0 ,0
Exp/Cntr=0.3,0.1

Type RM Length L Ch R = 1 ,12871   ,164,164,164
BEGIN DESCRIPTION:
Mapping XS e43d7107
END DESCRIPTION:
XS GIS Cut Line= 3
      3654737.69     10682350.02      3654555.38     10682649.54
      3654303.64     10683860.51
#Sta/Elev= 30
  4758.7  288.09    4786  285.56    4817  285.77  4844.1  283.67  4960.4  282.27
  4969.6  281.72  4975.8  279.89  5009.6  270.22  5012.4  269.72  5015.6  270.22
  5018.5  270.62  5028.1  282.07  5055.3   281.1  5092.1  282.06  5259.3  292.25
  5314.5  292.81  5391.4  295.89  5436.8  298.43    5488  296.84  5579.8  295.49
  5705.1   301.6  5906.7  295.42  5927.1  293.85  6000.6  294.03    6019  295.52
  6090.5  294.42  6240.9  298.14  6264.2  296.89    6291  299.97  6346.2  300.58
#Mann= 5 ,-1 , 0
  4758.7     .16       0  5009.6     .07       0  5015.6     .16       0
  5391.4     .16       0    5488     .05       0
Bank Sta=4975.8,5028.1
XS Rating Curve= 0 ,0
Exp/Cntr=0.3,0.1

Type RM Length L Ch R = 1 ,12707   ,367,367,367
BEGIN DESCRIPTION:
UNT 0302 IN LACR 21.0
END DESCRIPTION:
XS GIS Cut Line= 3
      3654663.85      10682319.7      3654355.72     10682545.37
      3653384.71     10683035.22
#Sta/Elev= 30
  4788.2  285.32  4827.1  283.87  4928.2  282.06  4949.1  279.93  4963.8   280.3
  4978.4  278.85  4984.6  280.04  4999.3  269.41  5002.5   268.5  5005.2     268
  5008.5   268.5  5013.9  275.16  5020.1  278.92  5034.8  280.92  5038.1  280.51
  5055.7  279.78  5164.3  283.84  5255.4  287.47  5477.2  297.75  5535.4  298.05
  5544.1  299.27  5549.7  298.31  5557.8  300.29  5588.7  301.02  5647.4  300.55
  5750.4  302.31    5834  300.94  6040.3  300.18  6235.4  302.96  6257.7  302.33
#Mann= 7 ,-1 , 0
  4788.2     .12       0  4827.1     .16       0  5002.5     .07       0
  5008.5     .16       0  5038.1     .12       0  5164.3     .16       0
  5255.4     .05       0
Bank Sta=4984.6,5020.1
XS Rating Curve= 0 ,0
Exp/Cntr=0.3,0.1

Type RM Length L Ch R = 1 ,12340   ,441,441,441
BEGIN DESCRIPTION:
UNT 0302 IN LACR 20.0
END DESCRIPTION:
XS GIS Cut Line= 3
       3654749.6     10682210.19      3654349.61     10682210.19
      3654199.58     10682310.21
#Sta/Elev= 30
  4610.4   293.2  4640.4  289.72  4689.8  287.61  4720.4  284.93  4788.8  282.98
  4800.4  281.99  4820.4  281.83  4830.4  281.03  4870.4  280.73  4890.4  279.85
  4920.4  279.73  4940.4  280.78  4970.4  280.95  4980.4   279.3  4986.7  272.31
  4990.4   268.2  4997.4  267.37  5000.1  266.87  5003.4  267.37  5007.9  275.62
  5013.4  275.62  5017.9  278.74  5038.9  279.92  5050.3  278.95    5060  278.86
  5103.3  281.01  5126.1  282.71  5168.1  284.56  5183.2  286.58  5190.7  286.55
#Mann= 8 ,-1 , 0
  4610.4     .05       0  4689.8     .16       0  4788.8     .12       0
  4986.7     .16       0  4997.4     .07       0  5003.4     .16       0
  5050.3     .12       0  5103.3     .16       0
Bank Sta=4980.4,5007.9
XS Rating Curve= 0 ,0
Exp/Cntr=0.3,0.1

Type RM Length L Ch R = 1 ,11899   ,592,592,592
BEGIN DESCRIPTION:
UNT 0302 IN LACR 19.0
END DESCRIPTION:
XS GIS Cut Line= 3
      3654849.62      10682160.2      3654549.61     10681910.19
      3654449.63     10681710.22
#Sta/Elev= 30
    4588  298.15    4616  294.86    4687  289.97  4757.1  285.34  4786.5  282.71
  4850.3  279.59  4886.8  278.94  4914.1  276.32  4921.9   273.2  4928.4  266.31
  4936.2  268.51  4942.7   266.8  4957.1  266.14  4964.9  270.76  4968.4  266.11
  4971.1  265.61  4974.4  266.11  4975.3  269.84  4981.3  269.84  4986.9  266.96
  4992.5  271.53  5000.9  266.83  5014.9  266.73  5023.3  269.57  5031.6  275.24
  5037.2  274.17  5045.6  278.12  5066.3  280.13  5171.4  287.55  5202.1  288.67
#Mann= 6 ,-1 , 0
    4588     .05       0    4687     .16       0  4757.1     .12       0
  4968.4     .07       0  4974.4     .12       0  5066.3     .16       0
Bank Sta=4914.1,5031.6
XS Rating Curve= 0 ,0
Exp/Cntr=0.3,0.1

Type RM Length L Ch R = 1 ,11307   ,414,414,414
BEGIN DESCRIPTION:
UNT 0302 IN LACR 18.0
END DESCRIPTION:
XS GIS Cut Line= 3
      3655049.58     10681810.18      3654949.61     10681760.19
       3654549.6     10681560.18
#Sta/Elev= 30
  4875.1  286.75  4933.5  283.21  4964.5  280.78  4972.9  272.62  4978.5  274.68
  4984.1  271.11  4989.7  271.11  4995.3  265.48  4997.9  264.27  5000.6  263.77
  5003.9  264.27  5009.2  266.08  5017.6  271.03  5023.2  270.06  5031.6  272.87
  5045.6   274.2  5076.3  274.63  5107.1  274.36  5112.7  273.25  5129.4  273.59
    5135  270.74  5151.8     272  5157.4     274  5174.1  275.71  5224.5  276.27
  5232.8  277.18  5246.8  276.75  5297.8  279.55  5345.5  281.95  5434.1   287.4
#Mann= 6 ,-1 , 0
  4875.1     .16       0  4933.5     .12       0  4997.9     .07       0
  5003.9     .12       0  5297.8     .16       0  5345.5     .12       0
Bank Sta=4978.5,5045.6
XS Rating Curve= 0 ,0
Exp/Cntr=0.3,0.1

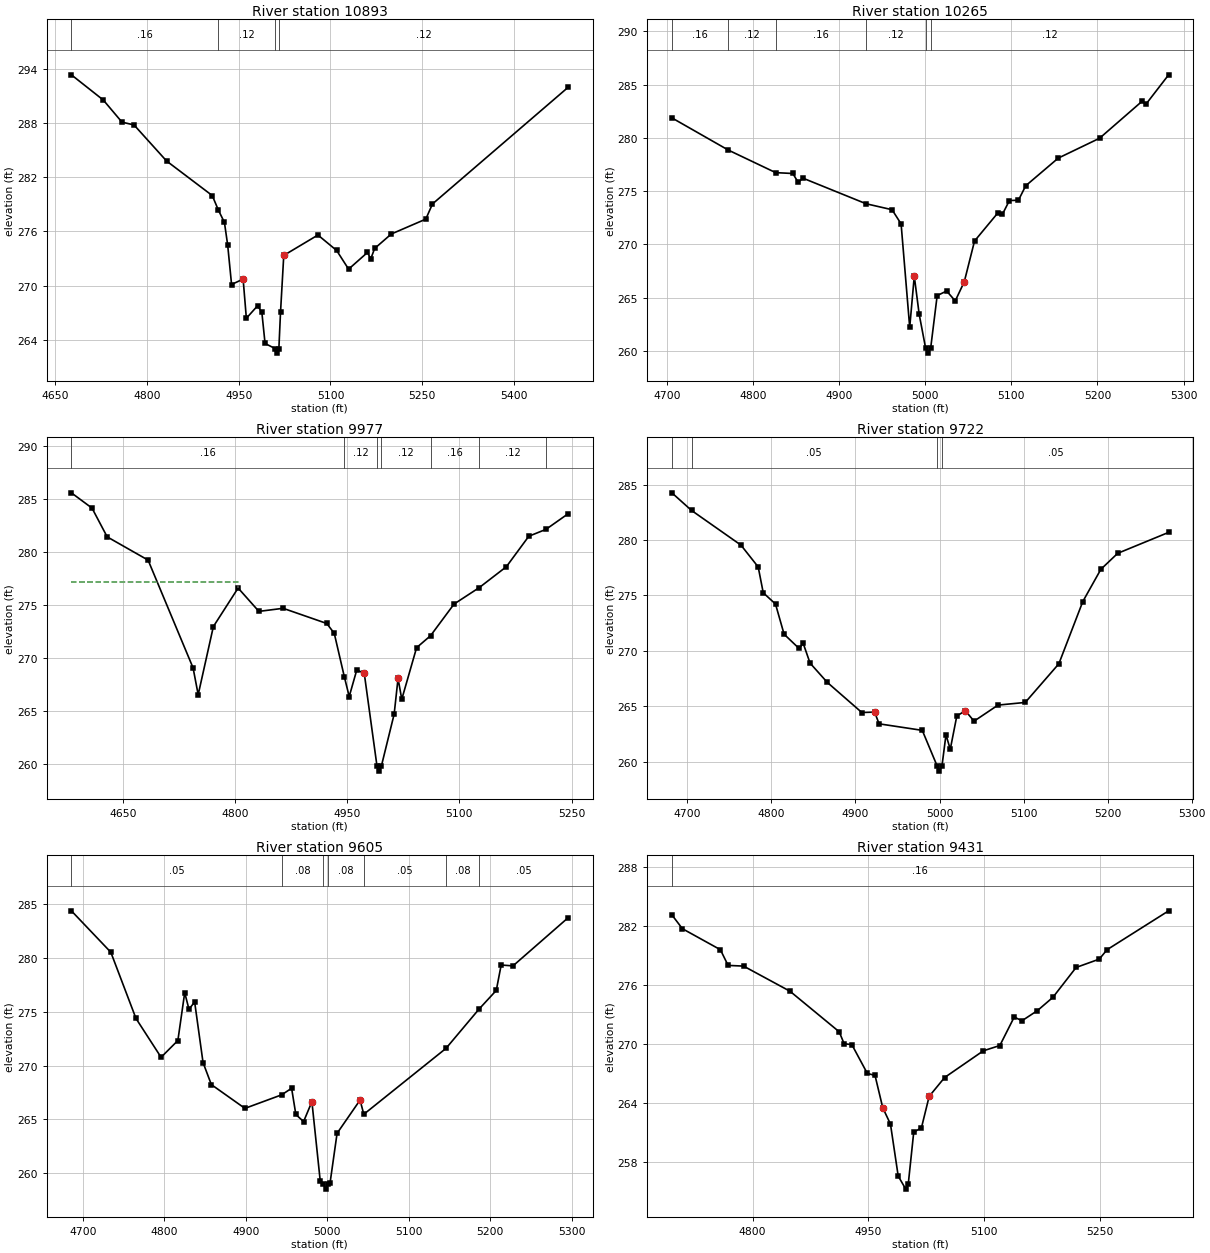
Type RM Length L Ch R = 1 ,10893   ,628,628,628
BEGIN DESCRIPTION:
UNT 0302 IN LACR 17.0
END DESCRIPTION:
XS GIS Cut Line= 3
       3655275.9     10681612.23      3654783.38     10681433.16
      3654507.65     10681347.46
#Sta/Elev= 30
  4676.1  293.34  4728.3  290.55  4758.9   288.1  4778.6  287.79  4831.8   283.8
  4906.6  279.97  4916.8  278.33  4926.5     277  4931.8  274.51  4938.2  270.12
  4957.1  270.72  4962.4  266.38  4980.7  267.76  4987.7  267.07    4993  263.59
  5009.6  263.02  5012.4  262.52  5015.6  263.02  5018.3  267.05  5023.6  273.34
  5079.5   275.6  5110.1  273.89  5129.7  271.82  5160.6  273.67  5165.9  272.95
  5172.3  274.11  5199.5  275.71    5256  277.36  5266.9  279.04  5488.9  291.96
#Mann= 4 ,-1 , 0
  4676.1     .16       0  4916.8     .12       0  5009.6     .07       0
  5015.6     .12       0
Bank Sta=4957.1,5023.6
XS Rating Curve= 0 ,0
Exp/Cntr=0.3,0.1

Type RM Length L Ch R = 1 ,10265   ,288,288,288
BEGIN DESCRIPTION:
UNT 0302 IN LACR 16.0
END DESCRIPTION:
XS GIS Cut Line= 2
      3655243.64     10681259.52      3654693.12      10681086.4
#Sta/Elev= 30
  4705.6  281.88  4771.1  278.86  4826.2  276.74  4846.1  276.66  4852.4  275.82
  4857.6  276.23  4931.2  273.82  4961.4  273.26  4971.9  271.93  4981.9  262.22
  4987.2  267.02  4992.9  263.45  5000.3   260.3  5003.1   259.8  5006.3   260.3
  5013.8   265.2  5024.8  265.63  5034.8   264.7  5045.3   266.5  5057.2  270.32
  5084.4  272.97  5089.6  272.83  5097.7  274.12  5108.2  274.15  5116.7  275.51
  5154.4   278.1  5202.5  279.97  5251.6  283.42  5256.8  283.21  5282.7  285.92
#Mann= 6 ,-1 , 0
  4705.6     .16       0  4771.1     .12       0  4826.2     .16       0
  4931.2     .12       0  5000.3     .07       0  5006.3     .12       0
Bank Sta=4987.2,5045.3
XS Rating Curve= 0 ,0
Exp/Cntr=0.3,0.1

Type RM Length L Ch R = 1 ,9977    ,255,255,255
BEGIN DESCRIPTION:
Mapping XS 91d8dbda
END DESCRIPTION:
XS GIS Cut Line= 3
       3655476.8     10680868.12       3655171.2     10680920.21
      3654817.08      10680934.1
#Sta/Elev= 30
  4581.1  285.57  4608.7  284.13    4629  281.42  4683.7  279.23  4743.9  269.07
  4750.7  266.55    4771  272.97  4804.1   276.6  4831.9   274.4  4864.3  274.69
  4922.7  273.26  4932.7  272.33  4946.3   268.2  4952.7  266.38  4962.8  268.88
  4972.8  268.57  4989.8  259.85  4992.5  259.35  4995.8  259.85  5012.8  264.72
    5018  268.08    5023  266.12  5042.8  270.98  5061.5  272.11  5092.9  275.09
  5126.6  276.64  5162.9  278.61  5192.9  281.48  5215.9  282.13  5245.5   283.6
#Mann= 7 ,-1 , 0
  4581.1     .16       0  4946.3     .12       0  4989.8     .07       0
  4995.8     .12       0  5061.5     .16       0  5126.6     .12       0
  5215.9     .05       0
#XS Ineff= 2 , 0
         4804.15  277.18
Permanent Ineff=
       F       F
Bank Sta=4972.8,5018
XS Rating Curve= 0 ,0
Exp/Cntr=0.3,0.1

Type RM Length L Ch R = 1 ,9722    ,117,117,117
BEGIN DESCRIPTION:
UNT 0302 IN LACR 15.0
END DESCRIPTION:
XS GIS Cut Line= 3
      3655449.63     10680810.19      3655069.19     10680721.01
      3654869.11     10680729.24
#Sta/Elev= 30
  4681.6  284.26    4705  282.67  4763.8  279.54  4784.3  277.57  4790.3  275.24
  4804.9  274.22  4815.1   271.5  4832.8  270.22  4837.9  270.66    4846  268.89
  4866.5  267.15  4907.6  264.43  4922.8  264.47  4928.1  263.41  4979.5  262.82
    4997  259.64  4999.8  259.14    5003  259.64  5007.7  262.42  5012.8  261.11
  5020.6  264.12  5030.8  264.59  5041.1  263.65  5069.6   265.1    5102  265.34
    5142  268.83  5170.5  274.45    5192  277.36    5212   278.8  5272.6  280.69
#Mann= 4 ,-1 , 0
  4681.6     .16       0    4705     .05       0    4997     .04       0
    5003     .05       0
Bank Sta=4922.8,5030.8
XS Rating Curve= 0 ,0
Exp/Cntr=0.3,0.1

Type RM Length L Ch R = 1 ,9605    ,174,174,174
BEGIN DESCRIPTION:
Mapping XS 18b6eee8
END DESCRIPTION:
XS GIS Cut Line= 2
      3655476.72      10680708.4      3654883.82     10680566.24
#Sta/Elev= 30
  4686.1   284.4  4734.5  280.55  4765.4  274.39  4796.2  270.78  4816.8  272.34
  4825.2  276.79  4830.4  275.25  4837.4  275.92  4847.7  270.29  4857.9  268.24
  4899.1  266.03  4944.2  267.29  4956.4   267.9  4961.6  265.46  4971.1   264.8
  4981.3  266.65  4991.6  259.23  4995.4  259.02  4998.2  258.52  5001.4  259.02
  5003.6   259.1  5012.2  263.71  5040.4   266.8    5045  265.48  5145.9  271.61
  5186.3  275.25  5207.6     277  5213.6  279.36  5228.1  279.28  5295.8  283.76
#Mann= 7 ,-1 , 0
  4686.1     .05       0  4944.2     .08       0  4995.4     .07       0
  5001.4     .08       0    5045     .05       0  5145.9     .08       0
  5186.3     .05       0
Bank Sta=4981.3,5040.4
XS Rating Curve= 0 ,0
Exp/Cntr=0.3,0.1

Type RM Length L Ch R = 1 ,9431    ,514,514,514
BEGIN DESCRIPTION:
UNT 0302 IN LACR 14.0
END DESCRIPTION:
XS GIS Cut Line= 2
       3655542.3     10680495.65      3654899.96      10680464.4
#Sta/Elev= 30
  4695.5  283.17  4709.1  281.76  4758.3  279.62  4768.3  278.02  4788.3  277.95
  4848.4  275.39  4912.1  271.26  4918.5  270.04  4928.5  269.95  4948.5  267.02
  4958.5  266.81  4968.5  263.52  4978.5  261.85  4988.5  256.56  4998.3  255.23
  5001.5  255.73  5008.6  261.03  5018.6  261.48  5028.6  264.68  5048.6   266.6
  5098.7  269.32  5120.1  269.86  5138.7  272.76  5148.7  272.38  5168.8  273.42
  5188.8  274.77  5218.8  277.81  5248.8  278.66  5258.9  279.62  5338.6  283.58
#Mann= 1 ,-1 , 0
  4695.5     .16       0
Bank Sta=4968.5,5028.6
XS Rating Curve= 0 ,0
Exp/Cntr=0.3,0.1

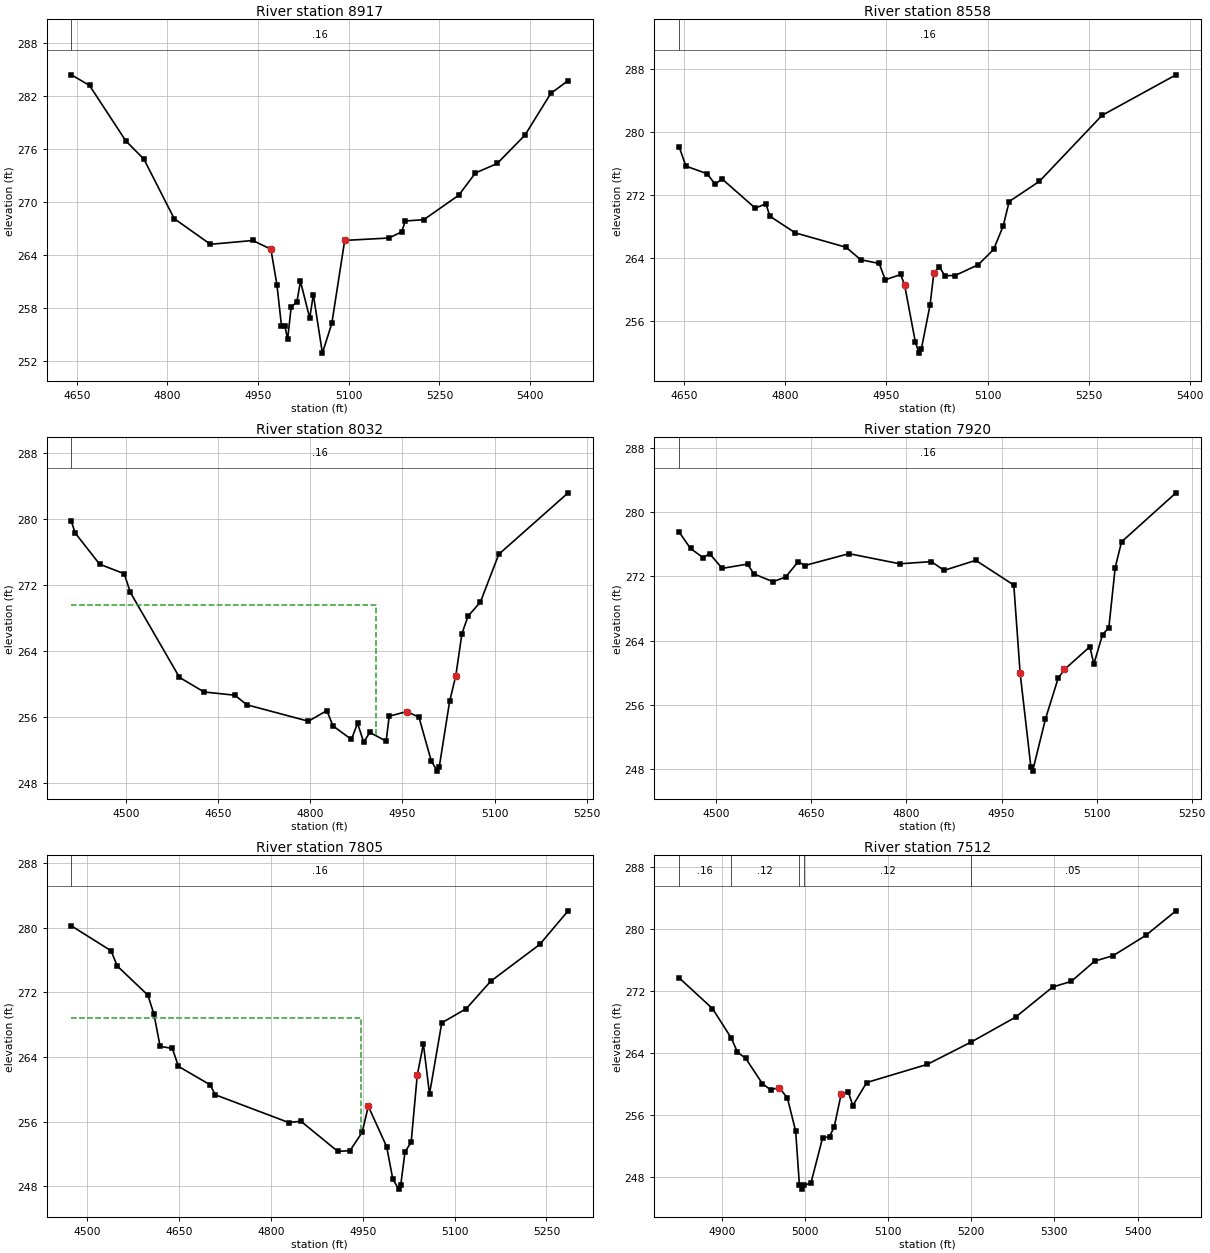
Type RM Length L Ch R = 1 ,8917    ,359,359,359
BEGIN DESCRIPTION:
UNT 0302 IN LACR 13.0
END DESCRIPTION:
XS GIS Cut Line= 3
      3655249.61     10679660.14      3655249.61     10680010.19
      3654849.65     10680260.16
#Sta/Elev= 30
  4641.1  284.37  4671.1  283.17  4731.1   276.9  4761.1  274.83  4811.1  268.11
  4871.1   265.2  4941.1  265.63  4971.1  264.65  4981.1  260.62  4988.6  256.01
  4994.1  256.01  4998.8  254.47  5004.7  258.12  5014.1  258.67    5020  261.02
  5035.4  256.85  5041.3  259.52  5056.3  252.89  5071.9  256.25  5093.2  265.64
  5166.3  265.91  5187.5  266.61  5193.4  267.84    5224  267.98  5281.8  270.75
  5309.5  273.27  5345.5  274.34  5391.5  277.56    5434  282.26  5462.8  283.72
#Mann= 1 ,-1 , 0
  4641.1     .16       0
Bank Sta=4971.1,5093.2
XS Rating Curve= 0 ,0
Exp/Cntr=0.3,0.1

Type RM Length L Ch R = 1 ,8558    ,526,526,526
BEGIN DESCRIPTION:
UNT 0302 IN LACR 12.0
END DESCRIPTION:
XS GIS Cut Line= 2
      3655097.91     10679593.98        3654738.     10680235.75
#Sta/Elev= 30
    4643  278.14  4652.8  275.71  4684.5  274.73  4696.2  273.39  4706.4  274.08
  4755.5  270.37  4771.5  270.91  4777.2  269.34  4814.8  267.22  4890.1  265.39
  4911.8   263.8  4939.2  263.33  4948.2  261.25  4971.1  261.93  4976.9  260.55
  4992.8  253.32  4998.3  251.93  5001.6  252.43  5014.5  258.03  5020.2  262.15
  5028.5  262.89  5036.2  261.78  5051.4  261.79  5085.8  263.16  5108.7  265.11
  5122.9   268.1  5131.7   271.2  5176.5  273.77  5269.2  282.15  5378.8  287.31
#Mann= 1 ,-1 , 0
    4643     .16       0
Bank Sta=4976.9,5020.2
XS Rating Curve= 0 ,0
Exp/Cntr=0.3,0.1

Type RM Length L Ch R = 1 ,8032    ,112,112,112
BEGIN DESCRIPTION:
UNT 0302 IN LACR 11.0
END DESCRIPTION:
XS GIS Cut Line= 2
      3654597.85     10679374.14      3654577.02     10680183.17
#Sta/Elev= 30
  4410.6  279.74  4416.7  278.34  4456.7  274.54  4496.7  273.39  4506.7  271.11
  4586.7   260.8  4626.7  259.03  4676.7  258.64  4696.7  257.47  4796.8  255.48
  4826.8  256.77  4836.8  254.91  4866.8  253.27  4876.8  255.23  4886.8  252.94
  4896.8  254.12  4923.4  253.06  4928.4  256.09  4956.8  256.65  4976.8  255.98
  4996.8  250.69  5006.6  249.42  5009.9  249.92  5026.9  257.92  5036.9  261.01
  5046.9  266.13  5056.9  268.24  5076.9  269.94  5106.9  275.75  5219.9  283.21
#Mann= 1 ,-1 , 0
  4410.6     .16       0
#XS Ineff= 2 , 0
          4907.2  269.59
Permanent Ineff=
       F       F
Bank Sta=4956.8,5036.9
XS Rating Curve= 0 ,0
Exp/Cntr=0.3,0.1

Type RM Length L Ch R = 1 ,7920    ,115,115,115
BEGIN DESCRIPTION:
Mapping XS bfb2acf2
END DESCRIPTION:
XS GIS Cut Line= 2
      3654465.91     10679412.35      3654476.31     10680196.08
#Sta/Elev= 30
  4441.4   277.5  4459.2  275.47  4479.2  274.32  4489.2  274.83  4509.2  272.99
  4549.2  273.52  4559.2   272.3  4589.2  271.33  4609.3  271.91  4629.3  273.84
  4639.3  273.34  4709.3  274.82  4789.3  273.56  4839.3  273.83  4859.3  272.74
  4909.3  273.99  4969.3  270.91  4979.3  259.94  4996.3  248.23    4999  247.73
  5019.3  254.24  5039.3  259.31  5049.3   260.4  5089.3  263.23  5095.6  261.08
  5109.3  264.73  5119.3  265.62  5129.3  273.09  5139.3  276.29  5225.2   282.4
#Mann= 1 ,-1 , 0
  4441.4     .16       0
Bank Sta=4979.3,5049.3
XS Rating Curve= 0 ,0
Exp/Cntr=0.3,0.1

Type RM Length L Ch R = 1 ,7805    ,293,293,293
BEGIN DESCRIPTION:
Mapping XS 83065e4a
END DESCRIPTION:
XS GIS Cut Line= 2
      3654361.74     10679405.32      3654372.14     10680216.55
#Sta/Elev= 30
  4474.1  280.22    4539  277.13    4549  275.25    4599  271.65    4609  269.28
    4619  265.31    4639  265.05    4649  262.83  4700.9  260.54    4709  259.32
    4829  255.88    4849  256.04    4909  252.32    4929  252.39    4949  254.67
    4959   257.9    4989  252.89    4999  248.89  5008.8  247.64    5012  248.14
    5019  252.27    5029  253.43    5039  261.75    5049   265.6    5059  259.41
    5079  268.22    5119  269.97    5159  273.37    5239  277.92  5285.4  282.08
#Mann= 1 ,-1 , 0
  4474.1     .16       0
#XS Ineff= 2 , 0
         4946.99  268.83
Permanent Ineff=
       F       F
Bank Sta=4959,5039
XS Rating Curve= 0 ,0
Exp/Cntr=0.3,0.1

Type RM Length L Ch R = 1 ,7512    ,421,421,421
BEGIN DESCRIPTION:
UNT 0302 IN LACR 10.0
END DESCRIPTION:
XS GIS Cut Line= 3
      3654099.61     10679710.22      3654099.61     10679860.19
      3654299.62     10680260.21
#Sta/Elev= 30
    4849  273.68    4889  269.72  4911.5  265.93    4919   264.1    4929  263.28
    4949  260.02    4959  259.22    4969  259.52    4979  258.19    4989  253.88
  4993.5   246.9  4996.2   246.4  4999.5   246.9  5007.4   247.2  5021.3     253
  5029.7  253.19  5035.3  254.43  5043.7  258.68  5052.1  258.98  5057.7   257.2
  5074.4  260.17  5147.1  262.51  5199.3  265.36  5253.3  268.61    5298  272.51
  5320.4  273.24  5348.4  275.85  5370.7  276.56  5409.8  279.17  5446.2  282.35
#Mann= 5 ,-1 , 0
    4849     .16       0  4911.5     .12       0  4993.5     .07       0
  4999.5     .12       0  5199.3     .05       0
Bank Sta=4969,5043.7
XS Rating Curve= 0 ,0
Exp/Cntr=0.3,0.1

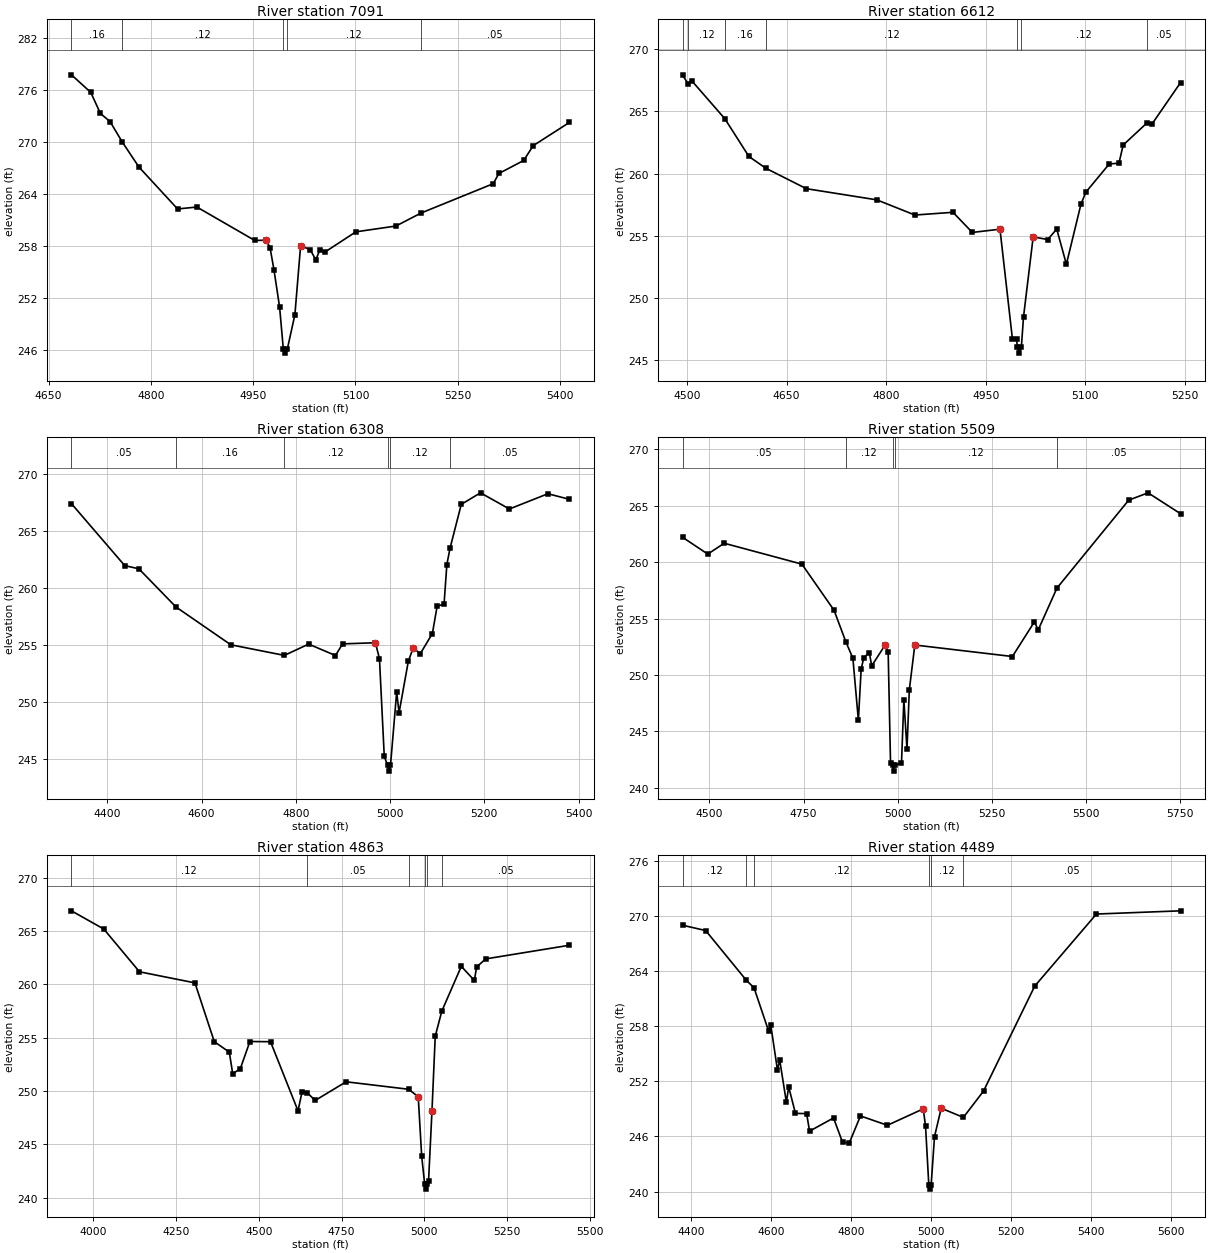
Type RM Length L Ch R = 1 ,7091    ,479,479,479
BEGIN DESCRIPTION:
UNT 0302 IN LACR 9.0
END DESCRIPTION:
XS GIS Cut Line= 3
      3653999.64     10679610.16      3653799.61     10679810.19
      3653999.61     10680210.19
#Sta/Elev= 30
  4683.6  277.78  4711.9  275.76  4726.1  273.32  4740.2  272.39  4757.9  270.06
  4782.6  267.14  4839.2  262.31  4867.5  262.53  4952.3  258.68  4969.3   258.7
  4974.9  257.79  4980.5   255.3  4988.8  250.98  4994.2  246.18    4997  245.68
  5000.2  246.18  5011.2  250.11  5019.6  258.09  5033.6  257.61  5041.9  256.45
  5047.5  257.54  5055.9  257.37  5100.6  259.67  5159.3  260.34  5196.2  261.84
  5301.9  265.22  5310.3   266.4  5346.6   267.9  5360.6  269.61  5413.7  272.29
#Mann= 5 ,-1 , 0
  4683.6     .16       0  4757.9     .12       0  4994.2     .07       0
  5000.2     .12       0  5196.2     .05       0
Bank Sta=4969.3,5019.6
XS Rating Curve= 0 ,0
Exp/Cntr=0.3,0.1

Type RM Length L Ch R = 1 ,6612    ,304,304,304
BEGIN DESCRIPTION:
UNT 0302 IN LACR 8.0
END DESCRIPTION:
XS GIS Cut Line= 3
      3653799.62     10679410.18      3653399.61     10679710.19
      3653249.62     10679910.18
#Sta/Elev= 30
  4493.3  267.94  4501.6  267.21  4506.9  267.48    4557  264.41  4593.3  261.37
  4618.9  260.42  4679.8  258.78    4786  257.88  4843.3  256.66  4900.6  256.88
  4929.8  255.26  4971.4  255.52  4990.2  246.66  4996.4  246.66  4997.6  246.05
  5000.4  245.55  5003.6  246.05  5006.9  248.49  5021.4   254.9  5043.3  254.69
  5056.9  255.53  5071.4   252.7  5093.3  257.52  5100.6  258.49    5136  260.77
  5150.6  260.83  5156.9  262.29  5193.2  264.09  5200.6     264  5243.3  267.31
#Mann= 7 ,-1 , 0
  4493.3     .16       0  4501.6     .12       0    4557     .16       0
  4618.9     .12       0  4997.6     .07       0  5003.6     .12       0
  5193.2     .05       0
Bank Sta=4971.4,5021.4
XS Rating Curve= 0 ,0
Exp/Cntr=0.3,0.1

Type RM Length L Ch R = 1 ,6308    ,799,799,799
BEGIN DESCRIPTION:
UNT 0302 IN LACR 7.0
END DESCRIPTION:
XS GIS Cut Line= 3
      3653465.95     10679068.84      3653133.62     10679564.67
      3653040.63     10680014.96
#Sta/Elev= 30
  4323.9  267.41    4437  261.97    4467  261.69  4545.7  258.34  4662.1  255.02
  4775.7  254.09  4827.2  255.08  4884.2  254.08  4899.2   255.1  4968.9   255.2
  4977.5   253.8  4987.7  245.22  4994.9  244.43  4997.7  243.93  5000.9  244.43
    5014  250.86  5019.1  249.05  5038.8  253.59    5049  254.73  5064.3  254.25
  5089.8  256.01    5100  258.44  5114.5  258.56  5120.5  262.06  5127.2  263.49
  5151.1  267.35  5191.9  268.36  5253.2  266.94  5334.9  268.28  5380.6  267.79
#Mann= 6 ,-1 , 0
  4323.9     .05       0  4545.7     .16       0  4775.7     .12       0
  4994.9     .07       0  5000.9     .12       0  5127.2     .05       0
Bank Sta=4968.9,5049
XS Rating Curve= 0 ,0
Exp/Cntr=0.3,0.1

Type RM Length L Ch R = 1 ,5509    ,646,646,646
BEGIN DESCRIPTION:
UNT 0302 IN LACR 6.0
END DESCRIPTION:
XS GIS Cut Line= 3
      3653214.25     10678890.83      3652726.32     10679540.79
      3652628.29     10680041.05
#Sta/Elev= 30
  4428.5  262.21  4495.5  260.72  4539.2  261.68  4745.5  259.83  4830.9  255.74
  4862.5  252.92  4880.9  251.49  4895.5  245.99  4902.9  250.53    4910  251.55
  4924.6  251.98  4930.9  250.81  4966.3  252.65  4974.6  252.03  4980.9   242.2
  4986.2  241.98  4988.9  241.48  4992.2  241.98    5010  242.19  5016.3   247.8
  5024.6  243.42  5030.8  248.69  5045.4  252.66  5304.5  251.64  5362.9  254.71
  5373.1     254  5422.7   257.7  5613.4   265.5  5664.8  266.15    5751   264.3
#Mann= 5 ,-1 , 0
  4428.5     .05       0  4862.5     .12       0  4986.2     .07       0
  4992.2     .12       0  5422.7     .05       0
Bank Sta=4966.3,5045.4
XS Rating Curve= 0 ,0
Exp/Cntr=0.3,0.1

Type RM Length L Ch R = 1 ,4863    ,374,374,374
BEGIN DESCRIPTION:
UNT 0302 IN LACR 5.0
END DESCRIPTION:
XS GIS Cut Line= 2
      3652710.75     10678530.65       3652307.1      10679980.3
#Sta/Elev= 30
  3933.6  266.91  4031.4   265.2  4139.2  261.19  4306.8  260.15  4365.2  254.64
  4410.6  253.65    4421  251.62    4444  252.11  4472.9  254.65  4535.2  254.63
  4618.2  248.15  4630.7  249.95  4645.9  249.85  4670.1  249.12  4763.6  250.87
  4952.3  250.17  4981.5  249.47  4991.9  243.91  5000.9   241.3  5003.7   240.8
  5006.9   241.3  5012.7  241.55  5023.1  248.17  5032.9  255.15  5052.9  257.51
  5111.7   261.7  5151.1  260.38    5158  261.64  5185.4   262.4  5438.4  263.68
#Mann= 6 ,-1 , 0
  3933.6     .12       0  4645.9     .05       0  4952.3     .12       0
  5000.9     .07       0  5006.9     .12       0  5052.9     .05       0
Bank Sta=4981.5,5023.1
XS Rating Curve= 0 ,0
Exp/Cntr=0.3,0.1

Type RM Length L Ch R = 1 ,4489    ,454,454,454
BEGIN DESCRIPTION:
UNT 0302 IN LACR 4.0
END DESCRIPTION:
XS GIS Cut Line= 3
      3652411.27      10678795.4      3652051.04     10679524.54
      3651886.11     10679923.84
#Sta/Elev= 30
    4378  269.03  4435.9  268.45  4537.7  263.02  4556.8  262.21    4593  257.53
  4598.5   258.2  4615.4  253.24    4621  254.34  4637.8  249.71  4643.4  251.42
  4660.3  248.52  4688.3  248.49  4695.7  246.58  4755.6  248.02  4778.1  245.37
  4794.9  245.28    4823  248.24  4890.3  247.22    4980  249.01  4985.7  247.12
  4993.8  240.76  4996.6  240.26  4999.8  240.76  5008.1  245.98  5024.9  249.08
  5080.3  248.08  5130.7  250.95  5258.7  262.39    5413  270.25  5623.3   270.6
#Mann= 6 ,-1 , 0
    4378     .12       0  4537.7     .16       0  4556.8     .12       0
  4993.8     .07       0  4999.8     .12       0  5080.3     .05       0
Bank Sta=4980,5024.9
XS Rating Curve= 0 ,0
Exp/Cntr=0.3,0.1

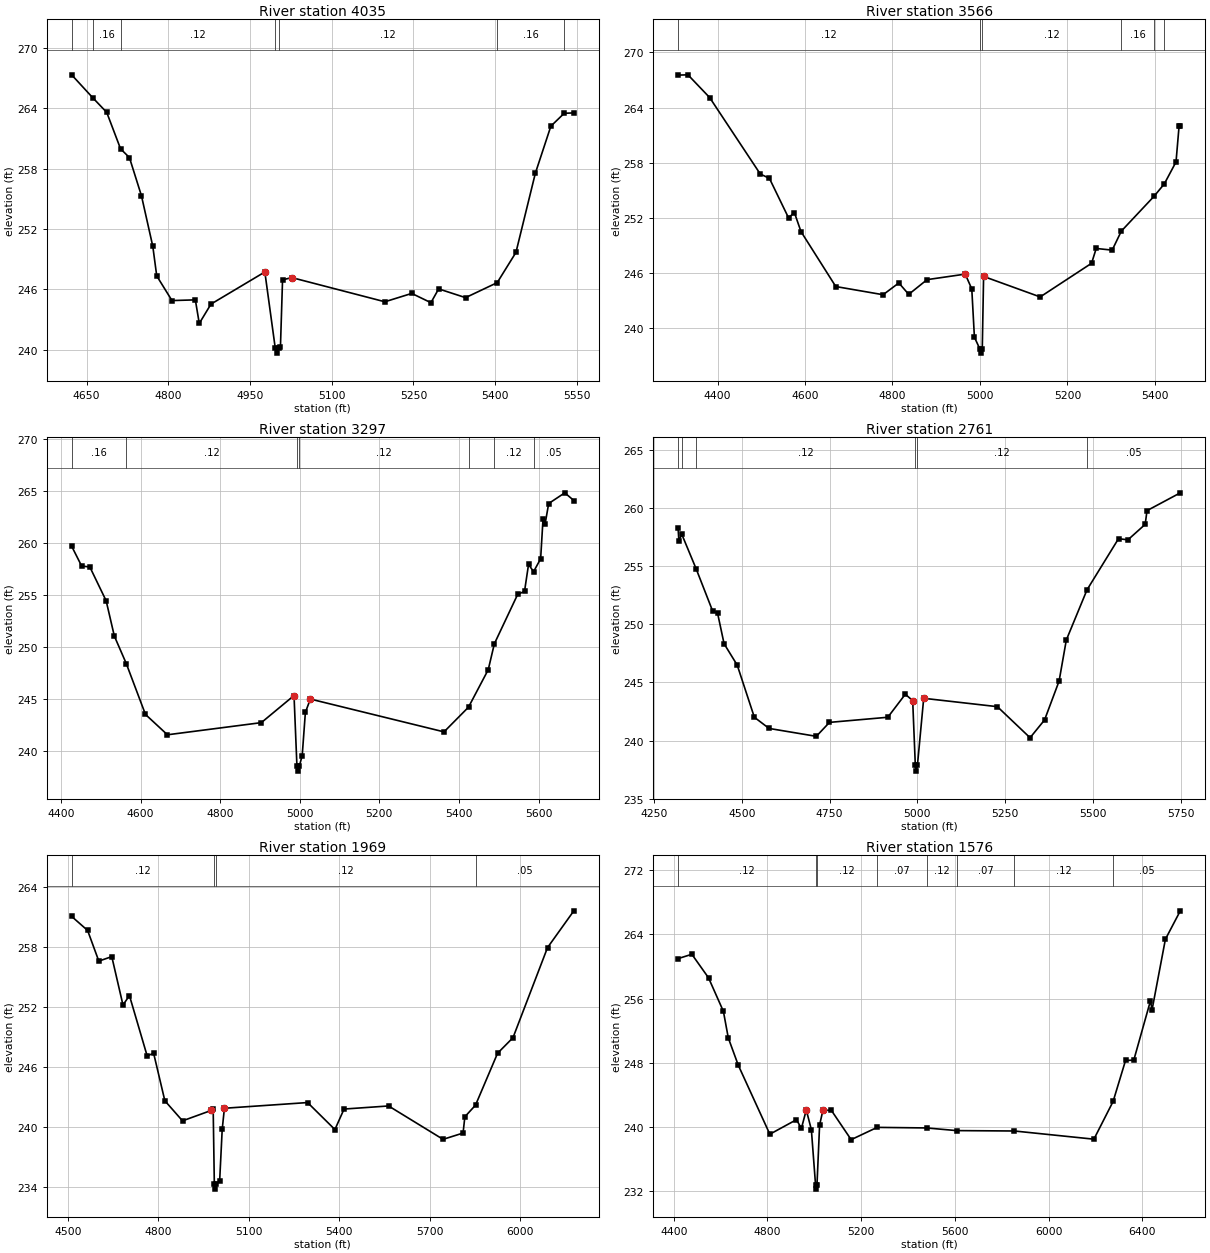
Type RM Length L Ch R = 1 ,4035    ,469,469,469
BEGIN DESCRIPTION:
UNT 0302 IN LACR 3.0
END DESCRIPTION:
XS GIS Cut Line= 3
       3652199.6      10678810.2      3651949.61     10679110.19
      3651549.61     10679460.19
#Sta/Elev= 30
  4622.5  267.32  4661.3  265.04  4686.9  263.59  4712.3  259.97  4728.6   259.1
  4750.7   255.3  4771.5  250.28  4778.7  247.35  4806.7   244.9  4849.6  244.97
  4856.8  242.63  4878.3  244.55  4977.2  247.74  4996.3  240.18  4999.1  239.68
  5002.3  240.18  5005.8  240.24  5009.7  246.96  5026.8  247.18  5197.6  244.78
  5246.9  245.61  5282.1  244.69  5296.3  246.06  5345.7  245.19  5403.8  246.68
  5438.2  249.68  5473.8  257.54  5502.3  262.22  5526.8   263.5  5544.5  263.54
#Mann= 7 ,-1 , 0
  4622.5     .12       0  4661.3     .16       0  4712.3     .12       0
  4996.3     .07       0  5002.3     .12       0  5403.8     .16       0
  5526.8     .05       0
Bank Sta=4977.2,5026.8
XS Rating Curve= 0 ,0
Exp/Cntr=0.3,0.1

Type RM Length L Ch R = 1 ,3566    ,269,269,269
BEGIN DESCRIPTION:
UNT 0302 IN LACR 2.0
END DESCRIPTION:
XS GIS Cut Line= 3
      3652149.58     10678510.21      3651549.61     10678910.19
       3651399.6     10679310.21
#Sta/Elev= 30
  4309.9  267.54  4332.4  267.57    4382   265.1  4497.7  256.79  4518.7  256.31
  4562.3  252.03  4575.8  252.59  4590.8  250.53  4670.4  244.55  4778.6  243.66
  4814.6  244.94  4837.2   243.7  4879.2   245.3  4966.4   245.9  4981.4  244.29
  4987.4  239.04  4999.4  237.81  5002.2  237.31  5005.4  237.81  5008.4  245.65
  5137.8  243.42  5255.3  247.08  5265.9  248.69  5302.4  248.51  5323.4  250.58
  5398.1  254.36  5421.6  255.71  5448.4   258.1  5455.5  262.06  5458.2  262.06
#Mann= 6 ,-1 , 0
  4309.9     .12       0  4999.4     .07       0  5005.4     .12       0
  5323.4     .16       0  5398.1     .12       0  5421.6     .05       0
Bank Sta=4966.4,5008.4
XS Rating Curve= 0 ,0
Exp/Cntr=0.3,0.1

Type RM Length L Ch R = 1 ,3297    ,536,536,536
BEGIN DESCRIPTION:
Mapping XS bffc56a4
END DESCRIPTION:
XS GIS Cut Line= 3
      3651556.24     10678135.67      3651391.32     10678856.14
      3651313.19     10679372.66
#Sta/Elev= 30
    4427  259.71  4452.1   257.8  4472.7  257.71  4513.7  254.45  4534.2  251.06
  4564.2  248.41  4612.4  243.51  4667.6  241.55  4903.5  242.72  4985.6  245.33
  4992.9  238.55  4995.6  238.05  4998.9  238.55  5006.1  239.52  5014.1   243.7
  5026.6  244.99  5362.4  241.83  5423.9  244.21  5473.5  247.82  5488.8  250.31
  5547.4  255.07  5564.6  255.36  5574.7  257.95  5587.4  257.26  5605.1   258.5
  5611.1  262.34  5616.2  261.83  5625.3  263.82  5665.8  264.85  5688.5  264.11
#Mann= 7 ,-1 , 0
    4427     .16       0  4564.2     .12       0  4992.9     .07       0
  4998.9     .12       0  5423.9     .16       0  5488.8     .12       0
  5587.4     .05       0
Bank Sta=4985.6,5026.6
XS Rating Curve= 0 ,0
Exp/Cntr=0.3,0.1

Type RM Length L Ch R = 1 ,2761    ,792,792,792
BEGIN DESCRIPTION:
Mapping XS 72c1778f
END DESCRIPTION:
XS GIS Cut Line= 3
      3651365.27     10678053.18      3651083.16      10678938.6
      3651209.02      10679424.7
#Sta/Elev= 30
    4318  258.23  4320.1  257.19  4328.7  257.71  4369.9  254.72  4416.8   251.1
  4430.3  250.97    4449  248.32  4486.5  246.48  4535.3     242  4577.2  241.04
  4711.9  240.36  4749.4  241.56  4915.7     242  4965.6  243.98  4986.6  243.43
  4994.1  237.87  4996.8  237.37  5000.1  237.87    5018  243.63    5228  242.91
  5321.2  240.24  5362.5  241.77  5403.9  245.11  5424.5  248.64  5483.6  252.96
  5573.3  257.35  5600.1  257.25  5649.3  258.58  5654.5  259.76  5749.4  261.29
#Mann= 6 ,-1 , 0
    4318     .12       0  4328.7     .16       0  4369.9     .12       0
  4994.1     .07       0  5000.1     .12       0  5483.6     .05       0
Bank Sta=4986.6,5018
XS Rating Curve= 0 ,0
Exp/Cntr=0.3,0.1

Type RM Length L Ch R = 1 ,1969    ,393,393,393
BEGIN DESCRIPTION:
Mapping XS adbb456b
END DESCRIPTION:
XS GIS Cut Line= 4
      3651261.13     10678079.19      3650887.84     10678717.25
      3650853.12     10679003.71      3651203.85      10679536.3
#Sta/Elev= 30
  4512.9  261.02  4565.8  259.62    4603  256.55    4646     257  4683.1  252.16
  4704.6   253.1  4763.3  247.07  4784.8  247.33    4822  242.58  4880.6  240.57
  4976.5  241.62  4982.3  241.73  4986.1  234.24  4988.8  233.74  4992.1  234.24
  5003.8   234.6  5012.2  239.71  5019.5  241.83  5295.4   242.4    5386   239.7
  5416.3  241.75    5564  242.06  5744.7  238.72    5811  239.35    5817  240.98
  5852.3  242.14  5925.4  247.33  5976.6  248.89  6091.1   257.9  6178.4  261.58
#Mann= 4 ,-1 , 0
  4512.9     .12       0  4986.1     .07       0  4992.1     .12       0
  5852.3     .05       0
Bank Sta=4976.5,5019.5
XS Rating Curve= 0 ,0
Exp/Cntr=0.3,0.1

Type RM Length L Ch R = 1 ,1576    ,0,0,0
BEGIN DESCRIPTION:
UNT 0302 IN LACR 1.0
END DESCRIPTION:
XS GIS Cut Line= 4
      3651104.86      10678022.8      3650588.36     10678600.06
      3650575.34     10679099.19       3651233.3     10679666.25
#Sta/Elev= 30
  4418.8  260.97  4477.4  261.51  4548.5  258.58    4612   254.4  4632.9  251.09
  4675.5  247.69  4810.1   239.1  4923.8  240.91  4944.7  239.82  4965.6  242.12
  4987.3  239.66  5005.2  232.76    5008  232.26  5011.2  232.76  5022.4  240.24
  5036.7   242.1  5072.6  242.07    5157  238.42    5268  239.95  5479.1  239.88
  5606.5  239.55  5853.6   239.5  6192.7  238.48  6274.6  243.18  6327.7  248.29
  6362.8  248.32  6434.1  255.73  6440.7  254.58  6497.7  263.38  6561.3  266.92
#Mann= 8 ,-1 , 0
  4418.8     .12       0  5005.2     .07       0  5011.2     .12       0
    5268     .07       0  5479.1     .12       0  5606.5     .07       0
  5853.6     .12       0  6274.6     .05       0
Bank Sta=4965.6,5036.7
XS Rating Curve= 0 ,0
Exp/Cntr=0.3,0.1

Chan Stop Cuts=-1
Use User Specified Reach Order=0
Composite Channel Slope=5