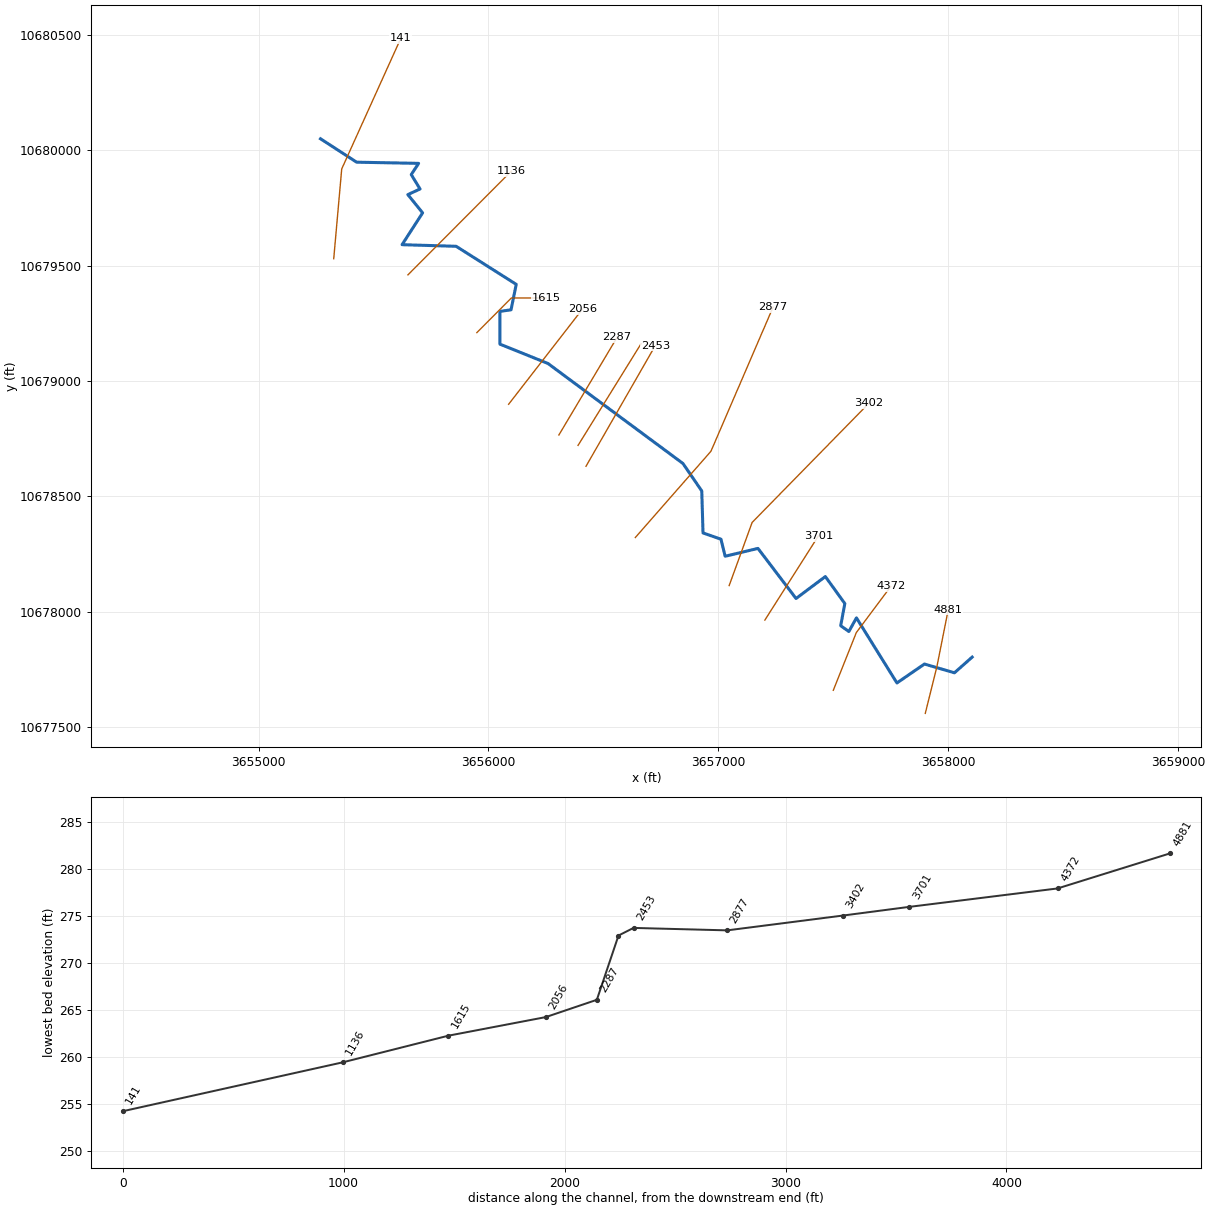
--- UNT 0303 IN LACR.prj (project) ---

Proj Title=UNT 0303 IN LACR Base Level Engineering
Current Plan=p01
Default Exp/Contr=0.3,0.1
English Units
Geom File=g01
Flow File=f01
Plan File=p01
Y Axis Title=Elevation
X Axis Title(PF)=Main Channel Distance
X Axis Title(XS)=Station
BEGIN DESCRIPTION:
UNT 0303 IN LACR
END DESCRIPTION:
DSS Export Rating Curves= 0
DSS Export Rating Curve Sorted= 0
DSS Export Volume Flow Curves= 0
DXF OffsetX= 0
DXF OffsetY= 0
DXF ScaleX= 1
DXF ScaleY= 10

--- UNT 0303 IN LACR.p01 (plan) ---

Plan Title=Multiple Run
Short Identifier=Multiple
Geom File=g01
Flow File=f01
Subcritical Flow
K Sum by GR= 0
Std Step Tol= 0.01
Critical Tol= 0.01
Num of Std Step Trials= 20
Max Error Tol= 0.3
Flow Tol Ratio= 0.001
Split Flow NTrial= 30
Split Flow Tol= 0.02
Split Flow Ratio= 0.02
Log Output Level= 0
Friction Slope Method= 1
Unsteady Friction Slope Method= 2
Unsteady Bridges Friction Slope Method= 1
Parabolic Critical Depth
Global Vel Dist=  1 , 1 , 1
Global Log Level= 0
CheckData=True
Encroach Param= -1, 0, 0, 0
BEGIN DESCRIPTION:
Multiple Run
END DESCRIPTION:

--- UNT 0303 IN LACR.f01 (steady flow) ---

Flow Title=Multiple
Number of Profiles=7
Profile Names=10-year,25-year,50-year,1pct_min,100-year,1pct_plu,500-year
River Rch & RM= UNT 0303 IN LACR,Reach-1,4881
     522     703     851     757    1024    1385    1490
Boundary for River Rch & Prof#=UNT 0303 IN LACR,Reach-1,1
Up Type=0
Dn Type=3
Dn Slope=0.005
Boundary for River Rch & Prof#=UNT 0303 IN LACR,Reach-1,2
Up Type=0
Dn Type=3
Dn Slope=0.005
Boundary for River Rch & Prof#=UNT 0303 IN LACR,Reach-1,3
Up Type=0
Dn Type=3
Dn Slope=0.005
Boundary for River Rch & Prof#=UNT 0303 IN LACR,Reach-1,4
Up Type=0
Dn Type=3
Dn Slope=0.005
Boundary for River Rch & Prof#=UNT 0303 IN LACR,Reach-1,5
Up Type=0
Dn Type=3
Dn Slope=0.005
Boundary for River Rch & Prof#=UNT 0303 IN LACR,Reach-1,6
Up Type=0
Dn Type=3
Dn Slope=0.005
Boundary for River Rch & Prof#=UNT 0303 IN LACR,Reach-1,7
Up Type=0
Dn Type=3
Dn Slope=0.005

--- UNT 0303 IN LACR.g01 (geometry) ---

Geom Title=Existing Conditions
Program Version=4.10

River Reach=UNT 0303 IN LACR,Reach-1
Reach XY= 30
       3658103.5       10677804.       3658026.5       10677736.
        3657896.       10677774.      3657776.25       10677692.
      3657600.25       10677974.      3657567.25       10677915.
      3657531.75       10677940.      3657549.75       10678036.
        3657465.       10678153.       3657337.5       10678058.
        3657172.       10678275.      3657029.25       10678241.
        3657011.       10678315.        3656933.       10678342.
       3656927.5       10678524.      3656845.75       10678643.
      3656258.72     10679076.28      3656049.61     10679160.19
      3656049.61     10679301.97      3656098.13     10679308.92
       3656120.7     10679419.16      3655859.41     10679584.09
      3655624.17     10679591.04      3655713.58     10679729.06
      3655649.34     10679808.05       3655702.3     10679832.36
       3655664.1     10679894.86      3655696.22     10679943.47
      3655426.65      10679948.5       3655269.5       10680050.

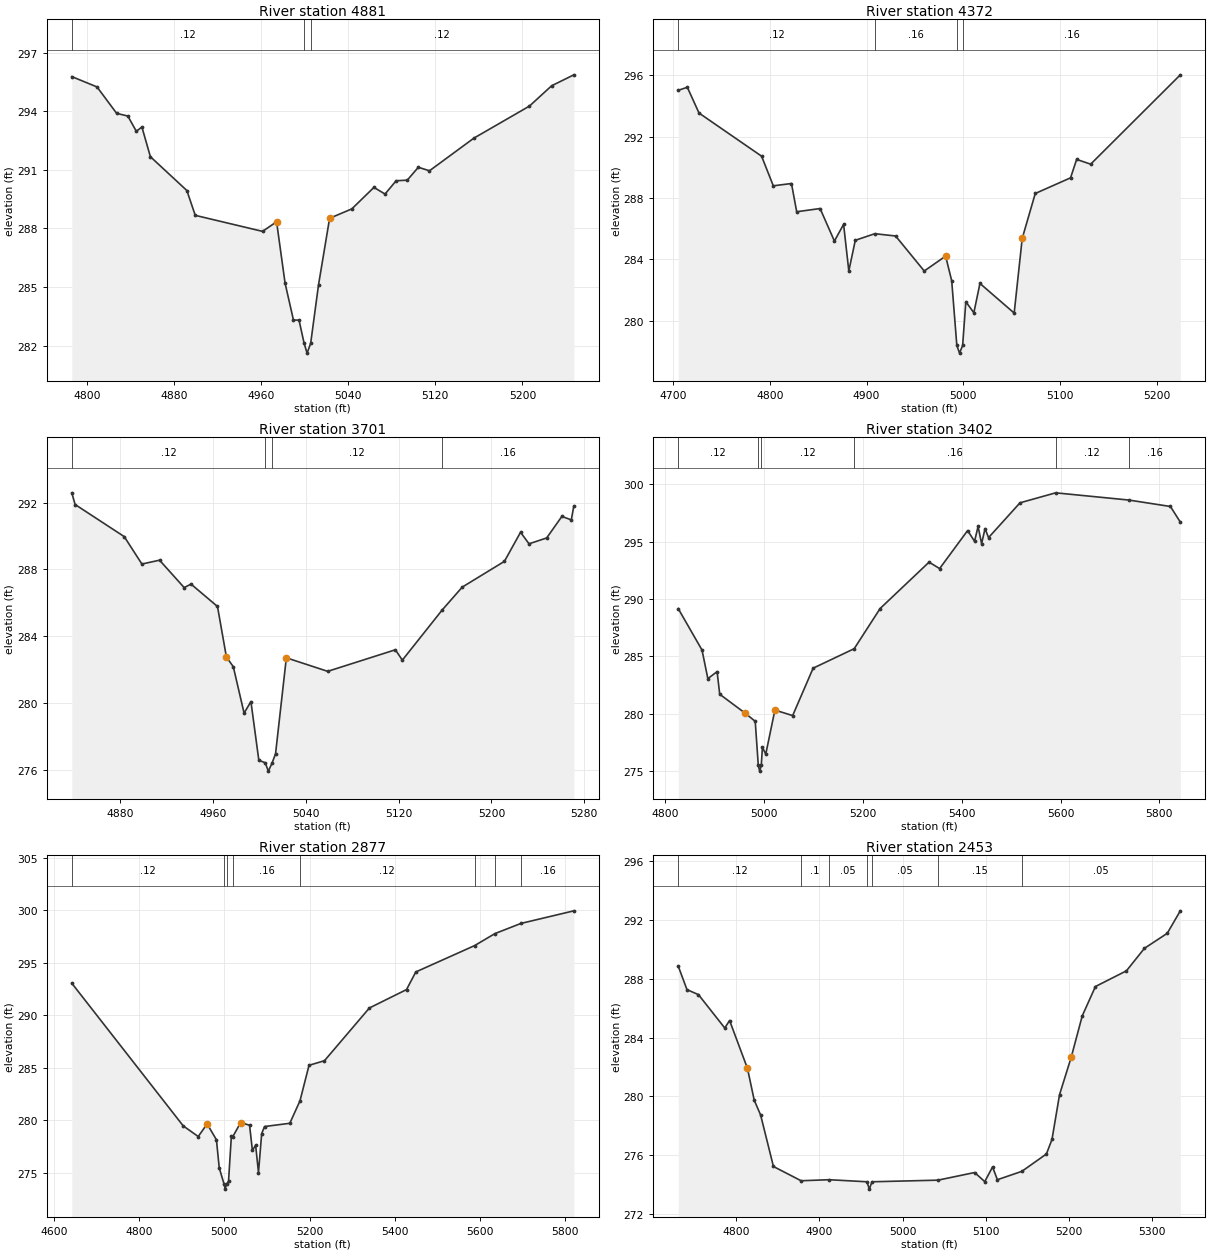
Type RM Length L Ch R = 1 ,4881    ,509,509,509
BEGIN DESCRIPTION:
UNT 0303 IN LACR 10.0
END DESCRIPTION:
XS GIS Cut Line= 3
      3657899.61     10677560.18      3657949.61     10677760.19
      3657999.61     10678010.18
#Sta/Elev= 30
  4786.1  295.77  4809.3  295.24  4827.3  293.89  4837.6  293.75  4845.4  292.97
  4850.5  293.19  4858.3  291.67  4891.8  289.94  4899.5  288.67  4961.3  287.85
  4974.2  288.34    4982   285.2  4989.7  283.31  4994.8  283.31  4999.5  282.12
  5002.2  281.62  5005.5  282.12  5012.7  285.11  5022.9  288.52  5043.3     289
  5063.6   290.1  5073.8  289.76    5084  290.44  5094.2  290.47  5104.4  291.13
  5114.6  290.95  5155.4  292.62  5206.4  294.26  5226.8   295.3  5247.2  295.86
#Mann= 3 ,-1 , 0
  4786.1     .12       0  4999.5     .07       0  5005.5     .12       0
Bank Sta=4974.2,5022.9
XS Rating Curve= 0 ,0
Exp/Cntr=0.3,0.1

Type RM Length L Ch R = 1 ,4372    ,671,671,671
BEGIN DESCRIPTION:
UNT 0303 IN LACR 9.0
END DESCRIPTION:
XS GIS Cut Line= 3
      3657499.61      10677660.2      3657599.61     10677910.19
      3657749.58     10678110.15
#Sta/Elev= 30
  4705.3  295.01  4714.7  295.21  4726.8  293.53  4791.5  290.72  4803.6  288.79
  4822.4  288.94  4827.8   287.1    4852  287.31  4866.8  285.19  4876.3  286.28
  4881.7  283.24  4888.4  285.24  4908.6  285.67  4930.1  285.52  4959.7  283.24
  4981.8  284.21  4988.1   282.6  4993.4  278.39  4996.2  277.89  4999.4  278.39
  5002.7  281.24    5011  280.52  5017.3  282.43  5052.7   280.5    5061  285.36
  5074.5  288.29    5111  289.31  5117.3  290.51  5131.8   290.2  5224.5  296.02
#Mann= 4 ,-1 , 0
  4705.3     .12       0  4908.6     .16       0  4993.4     .07       0
  4999.4     .16       0
Bank Sta=4981.8,5061
XS Rating Curve= 0 ,0
Exp/Cntr=0.3,0.1

Type RM Length L Ch R = 1 ,3701    ,299,299,299
BEGIN DESCRIPTION:
UNT 0303 IN LACR 8.0
END DESCRIPTION:
XS GIS Cut Line= 2
      3657202.02      10677964.4      3657434.61     10678328.91
#Sta/Elev= 30
  4838.6  292.58  4841.5  291.88  4883.8  289.96    4899  288.32  4914.2  288.55
  4935.4  286.91  4941.3  287.12  4964.1  285.78  4971.8  282.75  4977.7  282.18
    4987   279.4  4992.9  280.09  4999.7  276.58  5005.2  276.43  5007.9  275.93
  5011.2  276.43  5014.1  276.97  5023.4  282.71    5059   281.9  5117.3  283.19
  5123.3  282.57  5157.6  285.57  5174.9  286.94  5211.2  288.48  5225.1  290.22
  5232.4  289.53  5247.6  289.88  5260.7  291.17  5268.8  290.96    5271   291.8
#Mann= 4 ,-1 , 0
  4838.6     .12       0  5005.2     .07       0  5011.2     .12       0
  5157.6     .16       0
Bank Sta=4971.8,5023.4
XS Rating Curve= 0 ,0
Exp/Cntr=0.3,0.1

Type RM Length L Ch R = 1 ,3402    ,525,525,525
BEGIN DESCRIPTION:
UNT 0303 IN LACR 7.0
END DESCRIPTION:
XS GIS Cut Line= 3
       3657046.7     10678113.95      3657146.52     10678387.39
      3657654.33     10678903.88
#Sta/Elev= 30
  4826.9  289.17    4875  285.56  4886.8  283.07  4905.5  283.68  4910.8  281.71
  4961.3  280.09  4982.6  279.35  4988.8  275.51  4991.6  275.01  4994.8  275.51
  4997.2  277.08  5003.9  276.49  5022.4  280.33  5058.3  279.85  5099.7  283.98
  5182.8  285.68  5235.2  289.18  5334.2  293.22  5355.5  292.66  5412.1  295.97
  5426.2  295.04  5433.3  296.33  5440.4  294.83  5447.4  296.14  5454.5  295.36
  5518.1  298.39  5590.2  299.26  5738.3  298.63  5822.3  298.07  5842.3  296.71
#Mann= 6 ,-1 , 0
  4826.9     .12       0  4988.8     .07       0  4994.8     .12       0
  5182.8     .16       0  5590.2     .12       0  5738.3     .16       0
Bank Sta=4961.3,5022.4
XS Rating Curve= 0 ,0
Exp/Cntr=0.3,0.1

Type RM Length L Ch R = 1 ,2877    ,424,424,424
BEGIN DESCRIPTION:
UNT 0303 IN LACR 6.0
END DESCRIPTION:
XS GIS Cut Line= 3
      3656638.69     10678322.26      3656967.55     10678696.06
      3657237.68     10679320.57
#Sta/Elev= 30
  4641.8  293.04  4903.4  279.45  4938.6  278.44  4959.5  279.64  4981.3  278.13
  4987.9  275.45  4999.1  273.93  5001.9  273.43  5005.1  273.93  5009.7  274.18
  5016.4   278.5  5019.9  278.44  5038.2  279.77  5059.1  279.51  5065.7  277.12
  5073.3  277.61    5080  275.01  5087.5  278.72  5094.2  279.39  5153.5   279.7
  5177.4  281.84  5198.6  285.22  5234.9  285.66  5340.3  290.68  5427.4  292.43
  5449.2  294.11  5587.3  296.62  5634.8  297.76  5695.9  298.73  5820.1  299.93
#Mann= 8 ,-1 , 0
  4641.8     .12       0  4999.1     .07       0  5005.1     .12       0
  5019.9     .16       0  5177.4     .12       0  5587.3     .16       0
  5634.8     .12       0  5695.9     .16       0
Bank Sta=4959.5,5038.2
XS Rating Curve= 0 ,0
Exp/Cntr=0.3,0.1

Type RM Length L Ch R = 1 ,2453    ,68,68,68
BEGIN DESCRIPTION:
UNT 0303 IN LACR 5.0
END DESCRIPTION:
XS GIS Cut Line= 2
      3656424.24     10678631.06      3656725.42      10679153.8
#Sta/Elev= 30
  4730.4  288.86  4740.9  287.26  4754.7  286.92  4786.3  284.65  4792.1  285.16
  4813.6   281.9  4821.7  279.74  4829.4  278.73  4844.8  275.23    4878  274.26
  4911.8  274.33  4957.2  274.19    4960  273.69  4963.2  274.19  5042.5   274.3
  5086.6  274.82  5098.7   274.2  5108.1   275.2  5113.9  274.33  5143.3   274.9
  5172.8  276.08  5179.5  277.07  5188.6  280.12  5202.6  282.66  5215.9  285.48
  5231.7  287.47    5269  288.54  5290.6  290.07    5318  291.09  5333.7  292.62
#Mann= 7 ,-1 , 0
  4730.4     .12       0    4878      .1       0  4911.8     .05       0
  4957.2    .035       0  4963.2     .05       0  5042.5     .15       0
  5143.3     .05       0
Bank Sta=4813.6,5202.6
XS Rating Curve= 0 ,0
Exp/Cntr=0.3,0.1

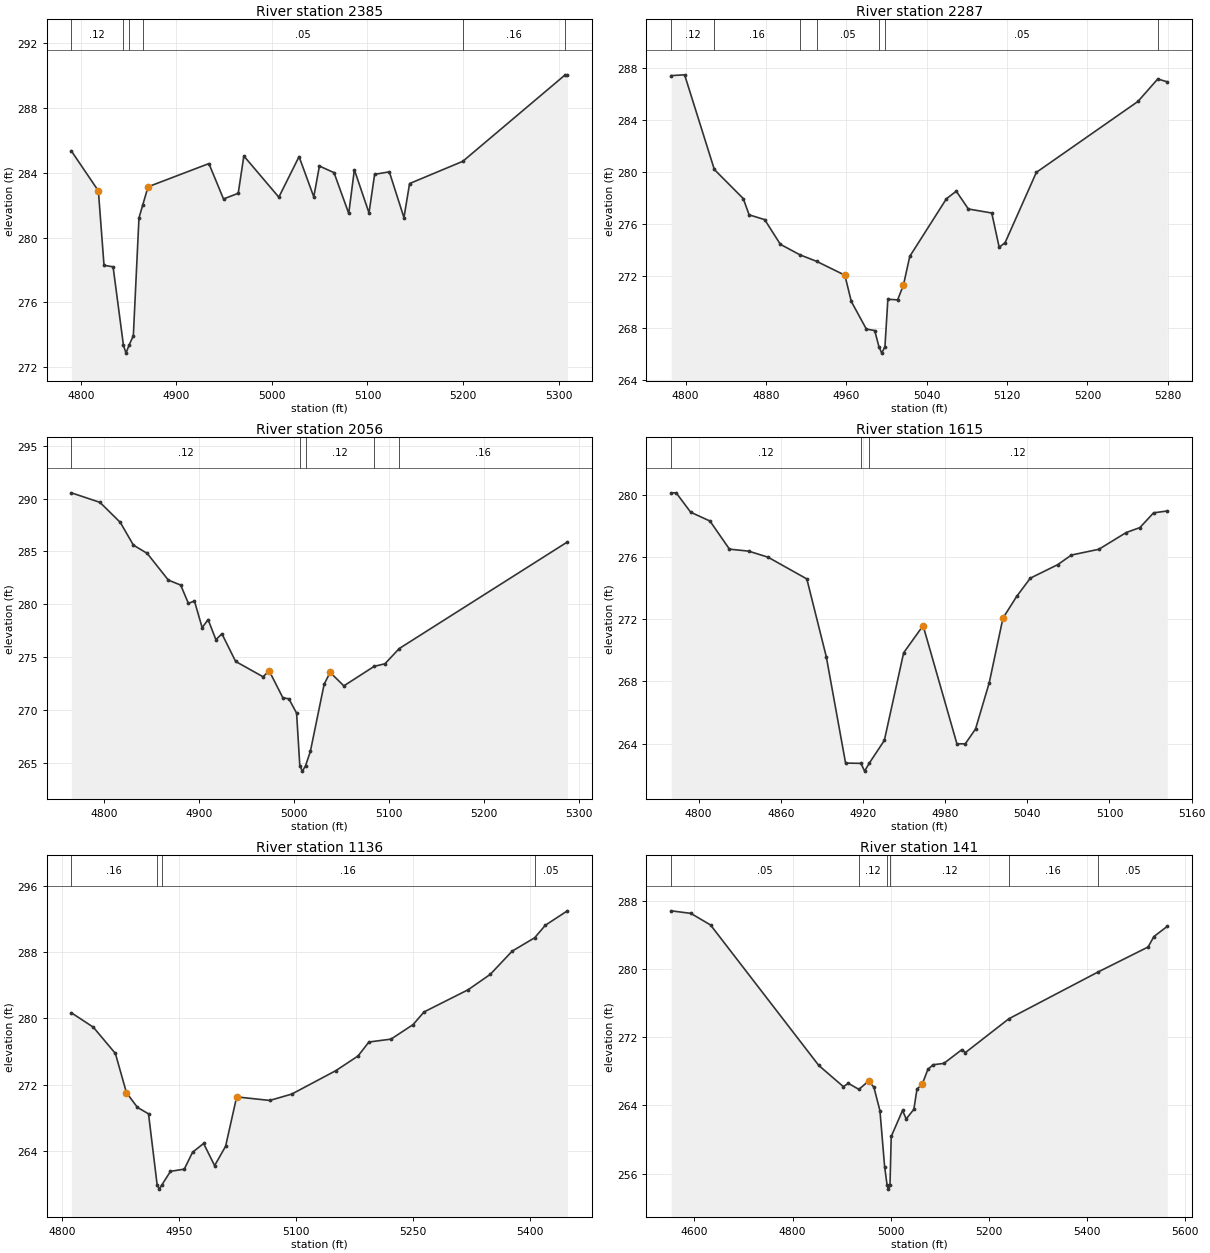
Type RM Length L Ch R = 1 ,2385    ,98,98,98
BEGIN DESCRIPTION:
Mapping XS 2f5e48d7
END DESCRIPTION:
XS GIS Cut Line= 2
      3656389.53     10678721.37      3656663.83     10679162.31
#Sta/Elev= 30
    4790  285.34  4818.3  282.88  4824.2  278.29  4833.7   278.2  4844.5  273.38
  4847.2  272.88  4850.5  273.38  4854.9  273.95  4860.8  281.21  4864.8  282.02
  4870.3  283.13    4934  284.56  4949.3  282.38  4964.7  282.73  4970.6  285.03
  5007.2  282.49  5028.4  284.99  5043.8  282.51  5049.7  284.41    5065     284
  5080.4  281.49  5086.3  284.18  5101.6  281.52  5107.5   283.9  5122.9  284.05
  5138.2  281.23  5144.1  283.33  5199.8   284.7    5307  290.03  5309.3  290.03
#Mann= 6 ,-1 , 0
    4790     .12       0  4844.5     .03       0  4850.5     .12       0
  4864.8     .05       0  5199.8     .16       0    5307     .05       0
Bank Sta=4818.3,4870.3
XS Rating Curve= 0 ,0
Exp/Cntr=0.3,0.1

Type RM Length L Ch R = 1 ,2287    ,231,231,231
BEGIN DESCRIPTION:
Mapping XS bb875db4
END DESCRIPTION:
XS GIS Cut Line= 2
      3656306.17     10678766.45      3656559.67      10679190.1
#Sta/Elev= 30
  4785.8  287.41  4799.1  287.47  4828.7  280.18  4857.5  277.94  4863.3  276.69
  4878.8  276.32  4894.4  274.42  4913.9  273.61  4930.7   273.1  4958.6  272.04
    4965  270.02    4980  267.89  4988.3  267.78  4992.5  266.54  4995.3  266.04
  4998.5  266.54  5001.4  270.19  5011.1  270.14  5016.9  271.28  5023.2  273.49
  5059.7  277.93  5069.5  278.51  5081.5  277.14  5104.8  276.83  5112.2  274.19
  5118.1  274.55  5149.2  279.96  5250.3  285.42    5270  287.15  5279.5  286.93
#Mann= 7 ,-1 , 0
  4785.8     .12       0  4828.7     .16       0  4913.9     .12       0
  4930.7     .05       0  4992.5     .03       0  4998.5     .05       0
    5270     .12       0
Bank Sta=4958.6,5016.9
XS Rating Curve= 0 ,0
Exp/Cntr=0.3,0.1

Type RM Length L Ch R = 1 ,2056    ,441,441,441
BEGIN DESCRIPTION:
UNT 0303 IN LACR 4.0
END DESCRIPTION:
XS GIS Cut Line= 2
      3656087.52     10678899.57      3656408.66     10679311.85
#Sta/Elev= 30
  4765.6  290.54  4795.7  289.64  4817.1  287.75    4831  285.59  4845.5  284.81
  4867.8  282.28  4880.8  281.81  4888.9  280.08  4895.3   280.3  4903.4  277.78
  4909.7  278.54  4917.9  276.64  4924.2   277.2  4938.7  274.58  4967.6  273.13
    4974   273.7  4988.4  271.15  4994.8  271.04  5002.9  269.69  5006.3   264.7
    5009   264.2  5012.3   264.7  5017.4  266.06  5031.9  272.41  5038.2  273.55
  5052.7  272.27  5084.7  274.12    5096  274.36    5111   275.8  5288.2  285.89
#Mann= 5 ,-1 , 0
  4765.6     .12       0  5006.3     .07       0  5012.3     .12       0
  5084.7     .05       0    5111     .16       0
Bank Sta=4974,5038.2
XS Rating Curve= 0 ,0
Exp/Cntr=0.3,0.1

Type RM Length L Ch R = 1 ,1615    ,479,479,479
BEGIN DESCRIPTION:
UNT 0303 IN LACR 3.0
END DESCRIPTION:
XS GIS Cut Line= 3
      3655949.59     10679210.17      3656099.61     10679360.19
      3656249.65     10679360.19
#Sta/Elev= 30
    4780  280.16  4783.6  280.16  4794.2  278.91  4808.3  278.34  4822.5  276.53
  4836.6   276.4  4850.7  276.01    4879  274.61  4893.2   269.6  4907.3  262.74
  4918.5  262.72  4921.2  262.22  4924.5  262.72  4935.6   264.2  4949.7  269.85
  4963.9   271.6  4988.6  263.98  4994.7  263.98  5002.2  264.94  5012.2  267.92
  5022.2  272.08  5032.2  273.48  5042.2  274.66  5062.2  275.53  5072.2  276.15
  5092.2  276.52  5112.2   277.6  5122.2  277.92  5132.2  278.87  5142.2  278.99
#Mann= 3 ,-1 , 0
    4780     .12       0  4918.5     .07       0  4924.5     .12       0
Bank Sta=4963.9,5022.2
XS Rating Curve= 0 ,0
Exp/Cntr=0.3,0.1

Type RM Length L Ch R = 1 ,1136    ,995,995,995
BEGIN DESCRIPTION:
UNT 0303 IN LACR 2.0
END DESCRIPTION:
XS GIS Cut Line= 3
      3655649.64     10679460.22      3655749.61     10679560.19
      3656099.64     10679910.22
#Sta/Elev= 30
  4811.7  280.66  4839.9  278.92  4868.2  275.75  4882.4  271.02  4896.5  269.24
  4910.7  268.47  4921.8  259.88  4924.5  259.38  4927.8  259.88  4938.9  261.53
  4956.6  261.79  4967.2  263.83  4981.4  264.89  4995.5  262.22  5009.6  264.55
  5023.8  270.51  5066.2  270.08  5094.5  270.85  5151.1  273.68  5179.4  275.44
  5193.5  277.13  5221.8  277.48  5250.1  279.23  5264.2  280.76  5320.8  283.44
  5349.1  285.29  5377.3   288.1  5406.1  289.71  5419.8  291.22  5448.1  292.96
#Mann= 4 ,-1 , 0
  4811.7     .16       0  4921.8     .07       0  4927.8     .16       0
  5406.1     .05       0
Bank Sta=4882.4,5023.8
XS Rating Curve= 0 ,0
Exp/Cntr=0.3,0.1

Type RM Length L Ch R = 1 ,141     ,0,0,0
BEGIN DESCRIPTION:
UNT 0303 IN LACR 1.0
END DESCRIPTION:
XS GIS Cut Line= 3
      3655327.02     10679530.35      3655361.74     10679919.26
      3655618.68     10680485.21
#Sta/Elev= 30
  4552.6  286.85  4592.6  286.55  4632.8  285.19  4853.6   268.7  4903.8  266.21
  4913.9   266.6  4935.4  265.89  4955.3  266.87    4966  266.15  4978.4  263.38
    4988  256.78  4992.9  254.68  4995.7  254.18  4998.9  254.68  5001.4  260.36
  5024.5  263.42  5031.9  262.42  5047.6  263.55  5053.9  265.91  5064.9  266.54
  5076.2  268.24  5086.8  268.78  5108.8  268.94  5145.4  270.55  5152.7  270.21
  5241.4  274.18  5422.4  279.64  5525.6  282.61  5537.1  283.82  5564.6  285.03
#Mann= 6 ,-1 , 0
  4552.6     .05       0  4935.4     .12       0  4992.9     .07       0
  4998.9     .12       0  5241.4     .16       0  5422.4     .05       0
Bank Sta=4955.3,5064.9
XS Rating Curve= 0 ,0
Exp/Cntr=0.3,0.1

Chan Stop Cuts=-1
Use User Specified Reach Order=0
Composite Channel Slope=5