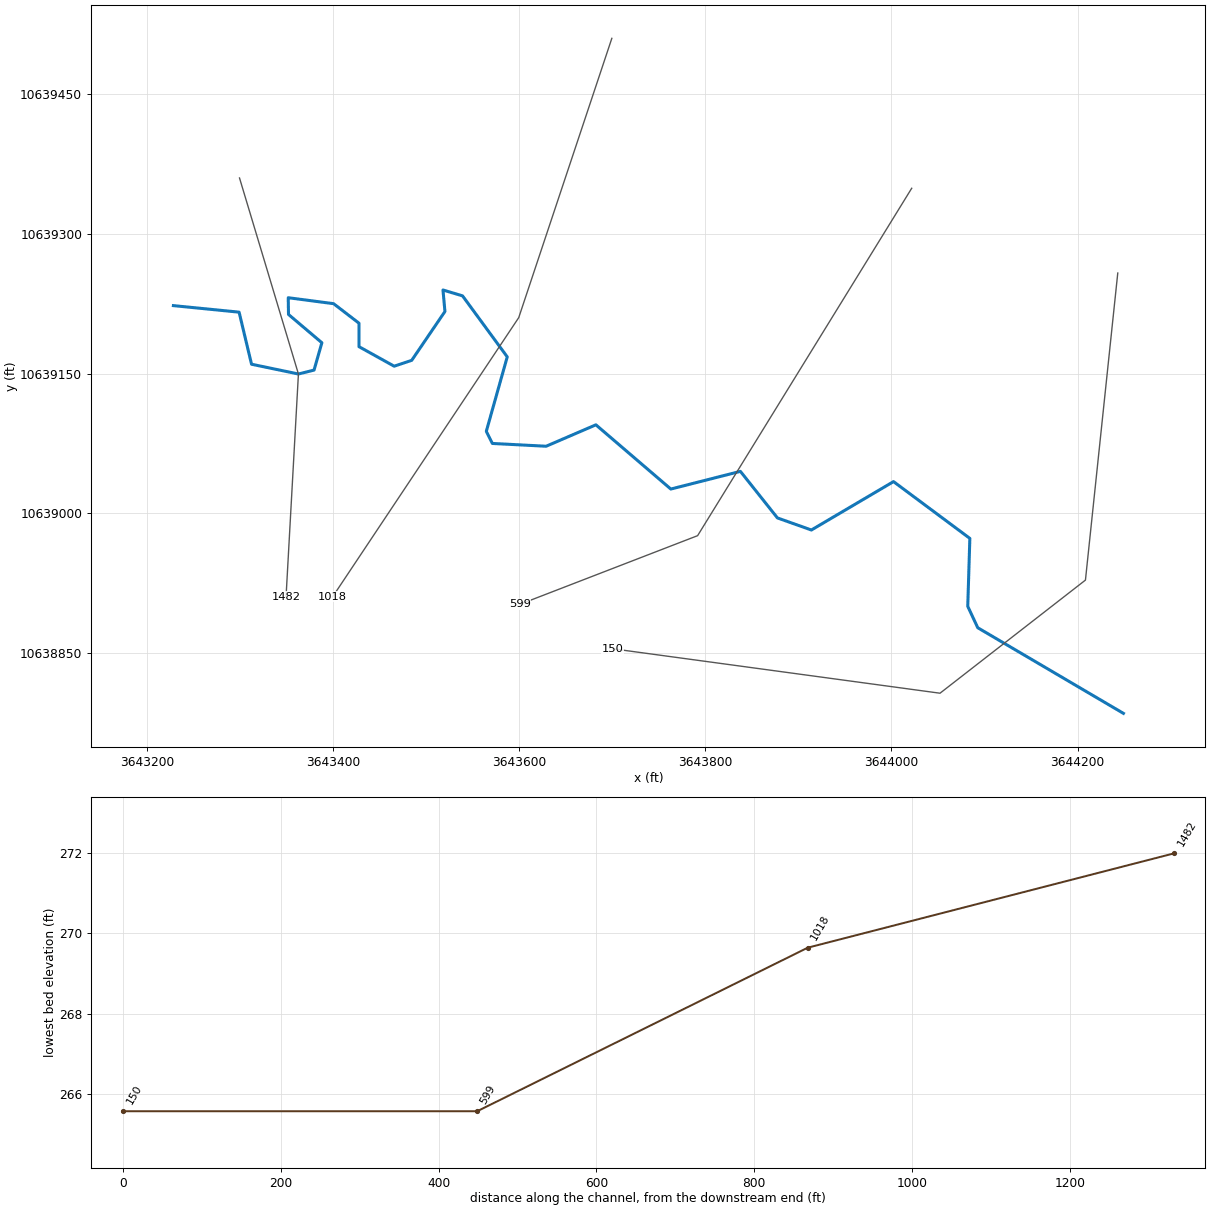
--- UNT 0321 IN LACR.prj (project) ---

Proj Title=UNT 0321 IN LACR Base Level Engineering
Current Plan=p01
Default Exp/Contr=0.3,0.1
English Units
Geom File=g01
Flow File=f01
Plan File=p01
BEGIN DESCRIPTION:
UNT 0321 IN LACR
END DESCRIPTION:

--- UNT 0321 IN LACR.p01 (plan) ---

Plan Title=Multiple Run
Short Identifier=Multiple
Geom File=g01
Flow File=f01
Subcritical Flow
K Sum by GR= 0
Std Step Tol= 0.01
Critical Tol= 0.01
Num of Std Step Trials= 20
Max Error Tol= 0.3
Flow Tol Ratio= 0.001
Split Flow NTrial= 30
Split Flow Tol= 0.02
Split Flow Ratio= 0.02
Log Output Level= 0
Friction Slope Method= 1
Unsteady Friction Slope Method= 2
Unsteady Bridges Friction Slope Method= 1
Parabolic Critical Depth
Global Vel Dist=  1 , 1 , 1
Global Log Level= 0
CheckData=True
Encroach Param= -1, 0, 0, 0
BEGIN DESCRIPTION:
Multiple Run
END DESCRIPTION:

--- UNT 0321 IN LACR.f01 (steady flow) ---

Flow Title=Multiple
Number of Profiles=7
Profile Names=10-year,25-year,50-year,1pct_min,100-year,1pct_plu,500-year
River Rch & RM= UNT 0321 IN LACR,Reach-1,1482
    1233    1737    2167    1976    2673    3614    4054
Boundary for River Rch & Prof#=UNT 0321 IN LACR,Reach-1,1
Up Type=0
Dn Type=3
Dn Slope=0.005
Boundary for River Rch & Prof#=UNT 0321 IN LACR,Reach-1,2
Up Type=0
Dn Type=3
Dn Slope=0.005
Boundary for River Rch & Prof#=UNT 0321 IN LACR,Reach-1,3
Up Type=0
Dn Type=3
Dn Slope=0.005
Boundary for River Rch & Prof#=UNT 0321 IN LACR,Reach-1,4
Up Type=0
Dn Type=3
Dn Slope=0.005
Boundary for River Rch & Prof#=UNT 0321 IN LACR,Reach-1,5
Up Type=0
Dn Type=3
Dn Slope=0.005
Boundary for River Rch & Prof#=UNT 0321 IN LACR,Reach-1,6
Up Type=0
Dn Type=3
Dn Slope=0.005
Boundary for River Rch & Prof#=UNT 0321 IN LACR,Reach-1,7
Up Type=0
Dn Type=3
Dn Slope=0.005

--- UNT 0321 IN LACR.g01 (geometry) ---

Geom Title=Existing Conditions

River Reach=UNT 0321 IN LACR,Reach-1
Reach XY= 30
      3643228.59     10639223.07      3643299.16     10639216.05
      3643312.54     10639160.10      3643362.91     10639149.61
      3643379.70     10639153.81      3643388.10     10639183.19
      3643352.24     10639213.59      3643351.97     10639231.56
      3643400.69     10639225.16      3643427.97     10639204.18
      3643427.97     10639178.99      3643465.75     10639158.00
      3643484.64     10639164.30      3643520.32     10639216.77
      3643518.22     10639239.86      3643539.21     10639233.56
      3643587.25     10639168.00      3643564.75     10639088.00
      3643571.25     10639075.00      3643629.00     10639072.00
      3643682.50     10639095.00      3643763.00     10639026.00
      3643837.75     10639045.00      3643877.50     10638995.00
      3643914.00     10638982.00      3644002.25     10639034.00
      3644084.25     10638973.00      3644082.00     10638900.00
      3644092.75     10638877.00      3644249.25     10638785.00

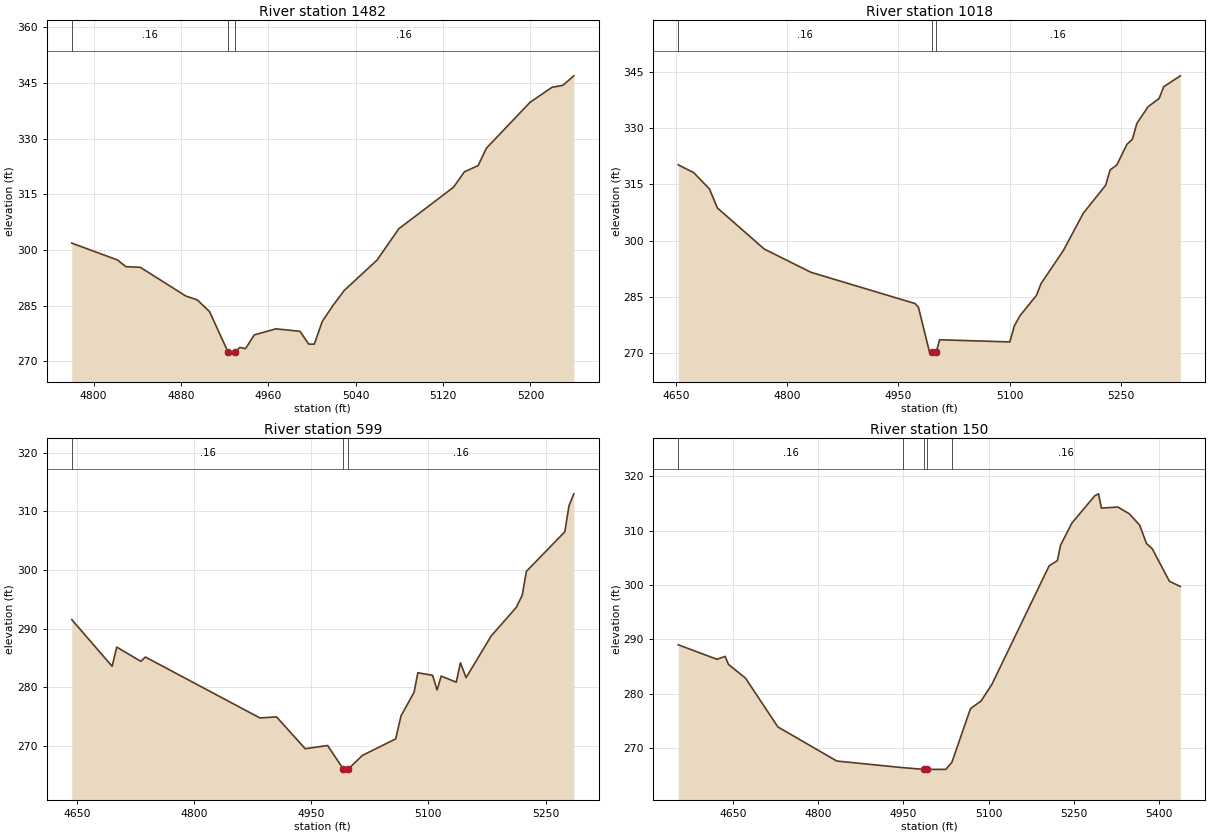
Type RM Length L Ch R = 1,1482,464,464,464
BEGIN DESCRIPTION:
UNT 0321 IN LACR 3.0
END DESCRIPTION:
XS GIS Cut Line= 3
      3643299.61     10639360.20      3643362.91     10639149.61
      3643349.61     10638910.18
#Sta/Elev= 30
  4780.1  301.88  4821.9  297.34  4829.7  295.53  4842.8  295.37  4884.5  287.63
  4895.0  286.59  4906.2  283.46  4923.3  272.48  4926.0  271.98  4929.3  272.48
  4934.0  273.79  4939.2  273.46  4947.2  277.15  4967.0  278.79  4989.0  278.13
  4997.1  274.67  5002.2  274.67  5009.4  280.76  5019.4  285.14  5029.5  289.11
  5059.5  297.27  5079.5  305.73  5129.6  316.92  5139.6  321.07  5152.2  322.76
  5159.7  327.43  5199.7  339.80  5219.8  343.84  5229.8  344.37  5239.8  346.93
#Mann=3,-1,0
  4780.1    0.16       0  4923.3    0.07       0  4929.3    0.16       0
Bank Sta=4923.3,4929.3
Exp/Cntr=0.3,0.1

Type RM Length L Ch R = 1,1018,419,419,419
BEGIN DESCRIPTION:
UNT 0321 IN LACR 2.0
END DESCRIPTION:
XS GIS Cut Line= 3
      3643699.62     10639510.23      3643599.61     10639210.19
      3643399.62     10638910.21
#Sta/Elev= 30
  4653.3  320.23  4674.4  318.10  4695.5  313.74  4706.0  308.71  4769.3  297.71
  4832.5  291.48  4972.6  283.15  4977.1  282.16  4992.1  270.14  4995.1  270.14
  4997.9  269.64  5001.1  270.14  5005.6  273.48  5100.3  272.90  5106.3  277.14
  5113.8  279.87  5136.3  285.37  5142.3  288.48  5172.4  297.31  5199.4  307.31
  5229.5  314.78  5235.5  318.86  5244.5  320.18  5258.0  325.65  5265.5  327.06
  5271.5  331.26  5286.6  335.74  5301.6  337.96  5307.6  341.06  5330.1  344.00
#Mann=3,-1,0
  4653.3    0.16       0  4995.1    0.07       0  5001.1    0.16       0
Bank Sta=4995.1,5001.1
Exp/Cntr=0.3,0.1

Type RM Length L Ch R = 1,599,449,449,449
BEGIN DESCRIPTION:
Mapping XS d9e806d1
END DESCRIPTION:
XS GIS Cut Line= 3
      3644021.79     10639349.16      3643791.78     10638975.93
      3643600.84     10638902.16
#Sta/Elev= 30
  4643.2  291.56  4694.9  283.61  4700.8  286.88  4731.6  284.46  4737.5  285.19
  4884.2  274.81  4905.5  274.99  4942.2  269.57  4970.9  270.11  4991.2  266.08
  4994.0  265.58  4997.2  266.08  5015.5  268.43  5058.1  271.24  5064.9  275.15
  5081.6  279.16  5086.5  282.51  5105.4  282.07  5111.1  279.57  5116.4  281.94
  5135.7  280.90  5141.0  284.20  5148.3  281.68  5180.4  288.77  5212.6  293.65
  5220.2  295.72  5225.5  299.78  5274.7  306.52  5280.1  310.96  5286.3  312.99
#Mann=3,-1,0
  4643.2    0.16       0  4991.2    0.07       0  4997.2    0.16       0
Bank Sta=4991.2,4997.2
Exp/Cntr=0.3,0.1

Type RM Length L Ch R = 1,150,0,0,0
BEGIN DESCRIPTION:
UNT 0321 IN LACR 1.0
END DESCRIPTION:
XS GIS Cut Line= 4
      3644243.17     10639258.08      3644208.44     10638928.19
      3644052.19     10638806.66      3643700.59     10638854.41
#Sta/Elev= 30
  4553.2  289.00  4621.5  286.33  4635.8  286.87  4641.6  285.40  4671.7  282.87
  4728.8  273.89  4832.6  267.62  4948.5  266.41  4986.3  266.08  4989.1  265.58
  4992.3  266.08  5024.6  266.08  5035.3  267.39  5068.1  277.27  5086.7  278.66
  5105.7  281.71  5206.6  303.52  5221.1  304.48  5226.8  307.33  5246.9  311.42
  5287.3  316.43  5293.6  316.76  5298.7  314.14  5327.7  314.33  5347.9  313.09
  5366.1  311.00  5378.1  307.63  5388.2  306.67  5418.5  300.68  5437.7  299.72
#Mann=5,-1,0
  4553.2    0.16       0  4948.5    0.05       0  4986.3   0.035       0
  4992.3    0.05       0  5035.3    0.16       0
Bank Sta=4986.3,4992.3
Exp/Cntr=0.3,0.1

Chan Stop Cuts=-1