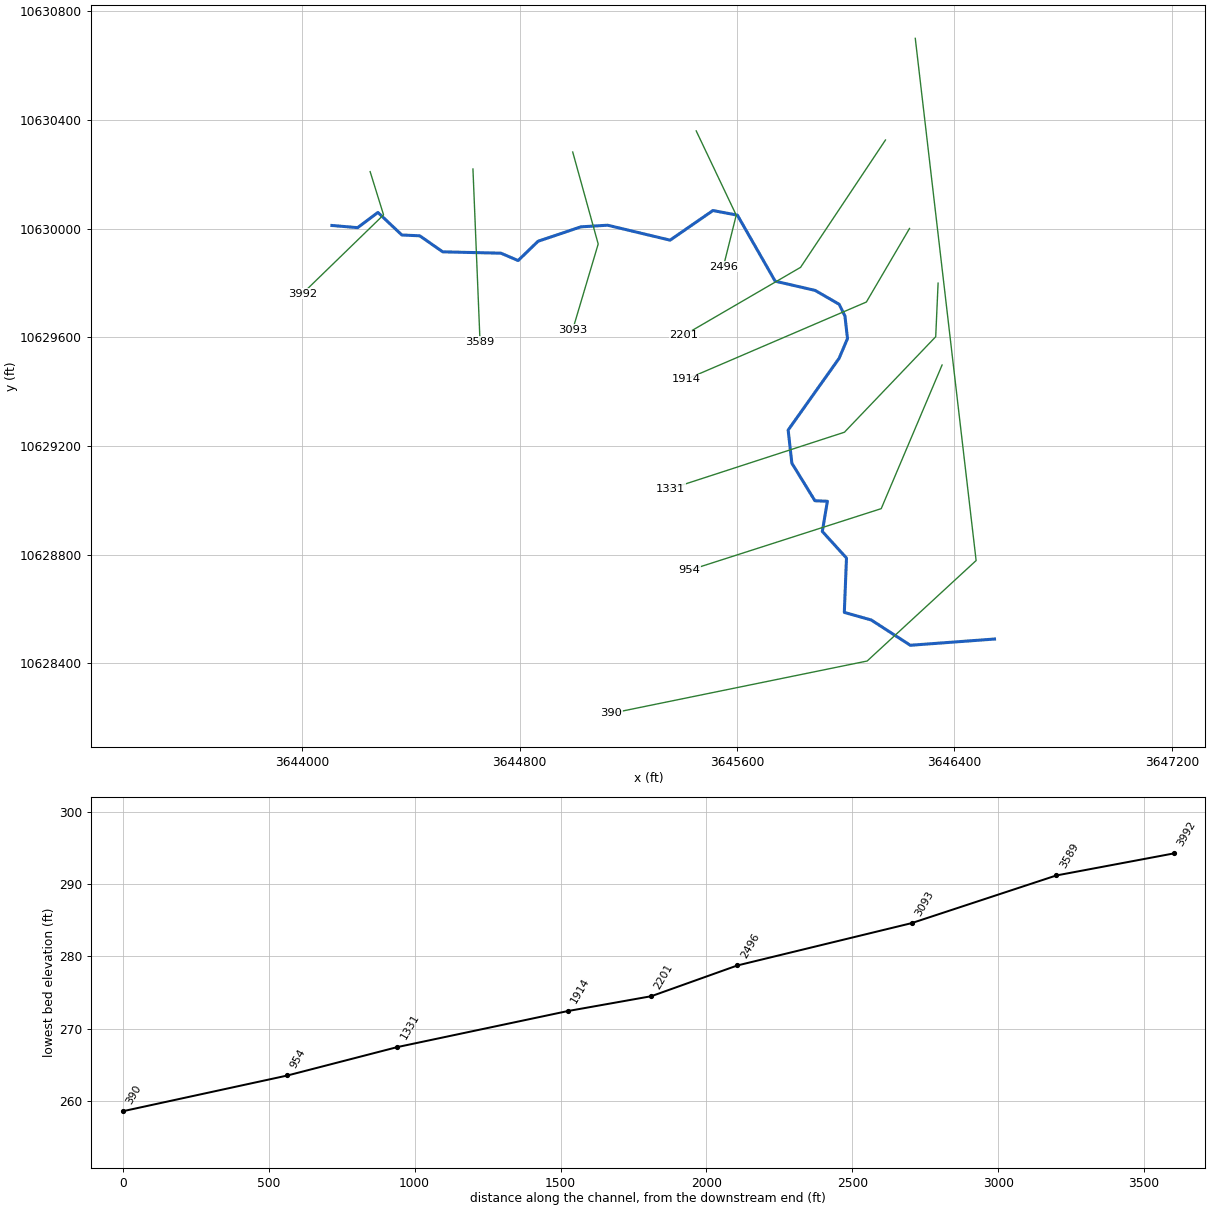
--- UNT 0326 IN LACR.prj (project) ---

Proj Title=UNT 0326 IN LACR Base Level Engineering
Current Plan=p01
Default Exp/Contr=0.3,0.1
English Units
Geom File=g01
Flow File=f01
Plan File=p01
Y Axis Title=Elevation
X Axis Title(PF)=Main Channel Distance
X Axis Title(XS)=Station
BEGIN DESCRIPTION:
UNT 0326 IN LACR
END DESCRIPTION:
DSS Export Rating Curves= 0
DSS Export Rating Curve Sorted= 0
DSS Export Volume Flow Curves= 0
DXF OffsetX= 0
DXF OffsetY= 0
DXF ScaleX= 1
DXF ScaleY= 10

--- UNT 0326 IN LACR.p01 (plan) ---

Plan Title=Multiple Run
Short Identifier=Multiple
Geom File=g01
Flow File=f01
Subcritical Flow
K Sum by GR= 0
Std Step Tol= 0.01
Critical Tol= 0.01
Num of Std Step Trials= 20
Max Error Tol= 0.3
Flow Tol Ratio= 0.001
Split Flow NTrial= 30
Split Flow Tol= 0.02
Split Flow Ratio= 0.02
Log Output Level= 0
Friction Slope Method= 1
Unsteady Friction Slope Method= 2
Unsteady Bridges Friction Slope Method= 1
Parabolic Critical Depth
Global Vel Dist=  1 , 1 , 1
Global Log Level= 0
CheckData=True
Encroach Param= -1, 0, 0, 0
BEGIN DESCRIPTION:
Multiple Run
END DESCRIPTION:

--- UNT 0326 IN LACR.f01 (steady flow) ---

Flow Title=Multiple
Number of Profiles=7
Profile Names=10-year,25-year,50-year,1pct_min,100-year,1pct_plu,500-year
River Rch & RM= UNT 0326 IN LACR,Reach-1,3992
     922    1290    1603    1462    1977    2673    3007
Boundary for River Rch & Prof#=UNT 0326 IN LACR,Reach-1,1
Up Type=0
Dn Type=3
Dn Slope=0.005
Boundary for River Rch & Prof#=UNT 0326 IN LACR,Reach-1,2
Up Type=0
Dn Type=3
Dn Slope=0.005
Boundary for River Rch & Prof#=UNT 0326 IN LACR,Reach-1,3
Up Type=0
Dn Type=3
Dn Slope=0.005
Boundary for River Rch & Prof#=UNT 0326 IN LACR,Reach-1,4
Up Type=0
Dn Type=3
Dn Slope=0.005
Boundary for River Rch & Prof#=UNT 0326 IN LACR,Reach-1,5
Up Type=0
Dn Type=3
Dn Slope=0.005
Boundary for River Rch & Prof#=UNT 0326 IN LACR,Reach-1,6
Up Type=0
Dn Type=3
Dn Slope=0.005
Boundary for River Rch & Prof#=UNT 0326 IN LACR,Reach-1,7
Up Type=0
Dn Type=3
Dn Slope=0.005

--- UNT 0326 IN LACR.g01 (geometry) ---

Geom Title=Existing Conditions
Program Version=4.10

River Reach=UNT 0326 IN LACR,Reach-1
Reach XY= 30
        3644109.       10630012.      3644203.75       10630004.
      3644278.25       10630060.      3644366.25       10629977.
      3644432.25       10629974.      3644516.75       10629915.
      3644730.75       10629910.      3644794.25       10629883.
      3644867.75       10629954.      3645025.25       10630007.
       3645123.5       10630013.       3645353.5       10629958.
      3645511.25       10630067.      3645601.25       10630050.
      3645740.25       10629807.       3645887.5       10629773.
      3645975.75       10629722.        3645997.       10629679.
       3646006.5       10629596.       3645975.5       10629523.
        3645788.       10629259.      3645801.75       10629137.
       3645886.5       10628999.       3645932.5       10628997.
      3645913.75       10628886.      3646002.75       10628788.
      3645994.75       10628588.        3646094.       10628560.
      3646237.75       10628467.       3646547.5       10628490.

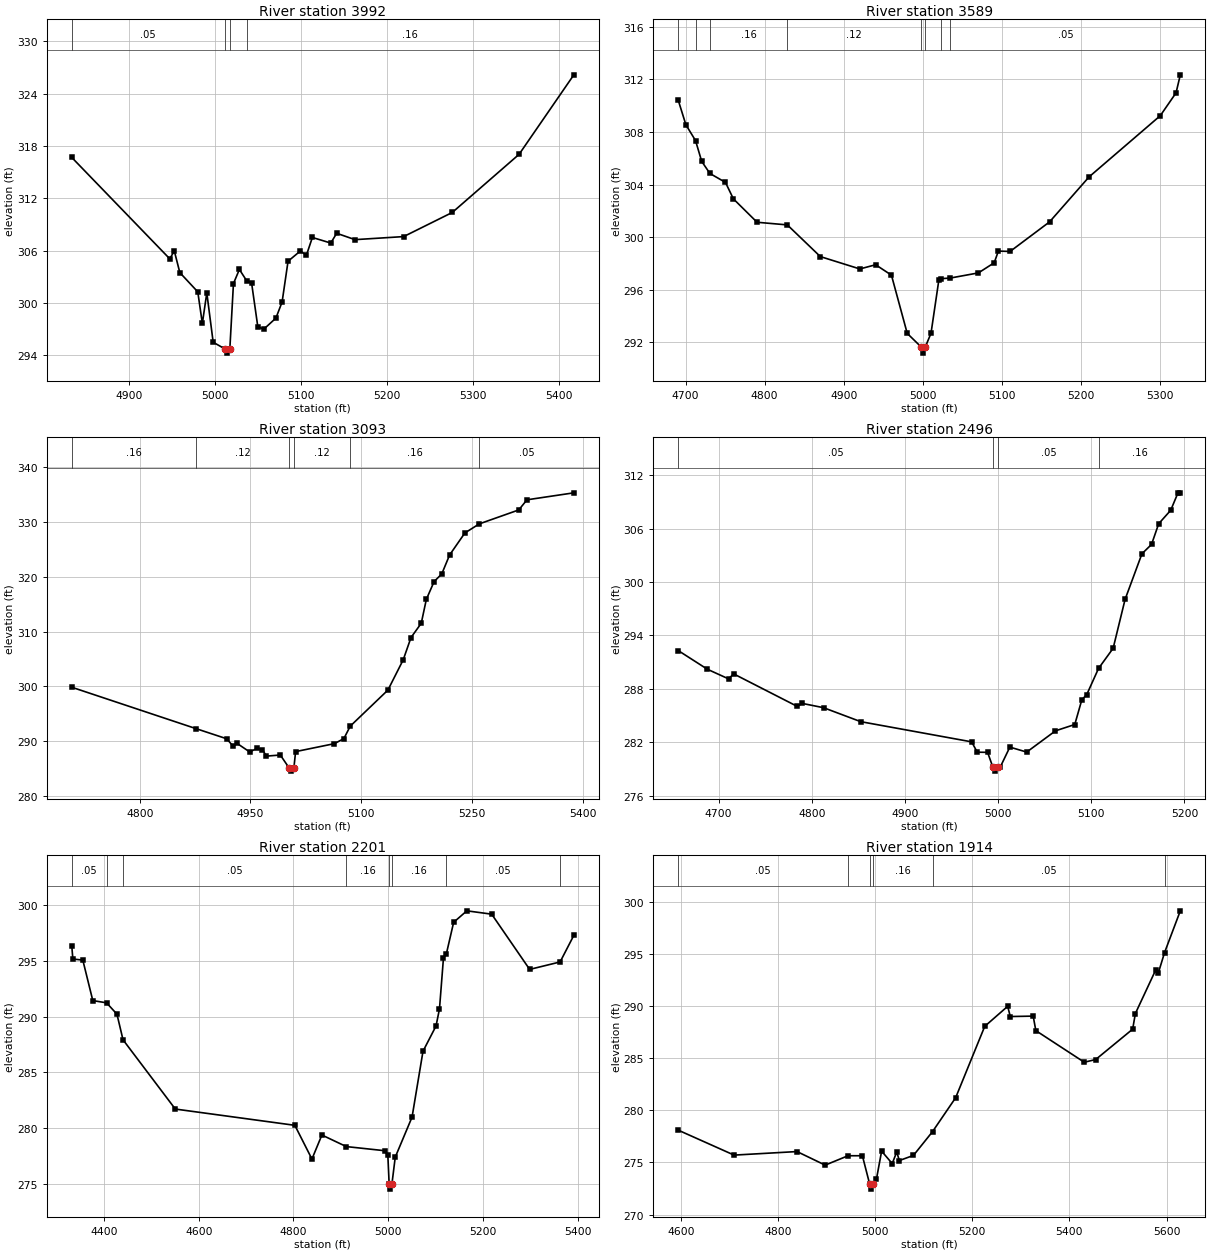
Type RM Length L Ch R = 1 ,3992    ,403,403,403
BEGIN DESCRIPTION:
UNT 0326 IN LACR 5.0
END DESCRIPTION:
XS GIS Cut Line= 3
       3644249.6     10630210.21        3644299.       10630051.
      3643999.59     10629760.17
#Sta/Elev= 30
  4833.3  316.69  4947.3  305.06  4952.6  305.96    4959  303.48  4979.9  301.27
  4985.2  297.64  4990.4  301.16  4997.8  295.49  5011.2  294.74    5014  294.24
  5017.2  294.74  5021.4  302.22  5028.3  303.84  5036.6  302.57  5042.5  302.29
  5049.7  297.29  5056.6  296.98  5070.8  298.26    5078  300.11  5084.9  304.78
  5099.1  305.95  5106.3  305.48  5113.2  307.51  5134.6  306.87  5141.5  307.99
  5162.8  307.26  5219.4  307.61    5276  310.38  5353.7  317.05  5417.4  326.17
#Mann= 4 ,-1 , 0
  4833.3     .05       0  5011.2     .03       0  5017.2     .05       0
  5036.6     .16       0
Bank Sta=5011.2,5017.2
XS Rating Curve= 0 ,0
Exp/Cntr=0.3,0.1

Type RM Length L Ch R = 1 ,3589    ,496,496,496
BEGIN DESCRIPTION:
UNT 0326 IN LACR 4.0
END DESCRIPTION:
XS GIS Cut Line= 2
        3644628.     10630219.89      3644654.03     10629584.83
#Sta/Elev= 30
  4690.6  310.42  4700.3  308.55  4712.5  307.35  4720.3  305.77  4730.7  304.85
  4750.4  304.17  4760.4  302.92  4790.4  301.14  4828.7  300.94  4870.5  298.53
  4920.5  297.59  4940.5  297.91  4960.5  297.12  4980.5  292.69  4997.6  291.69
  5000.3  291.19  5003.6  291.69  5010.6   292.7  5020.6  296.78  5023.3  296.85
  5035.1   296.9  5070.6  297.29  5090.6  298.06  5095.9  298.95  5110.7  298.92
  5160.7  301.17  5210.7  304.59  5300.8  309.24  5320.8  310.98  5326.2  312.35
#Mann= 8 ,-1 , 0
  4690.6     .16       0  4712.5     .05       0  4730.7     .16       0
  4828.7     .12       0  4997.6     .07       0  5003.6     .12       0
  5023.3     .16       0  5035.1     .05       0
Bank Sta=4997.6,5003.6
XS Rating Curve= 0 ,0
Exp/Cntr=0.3,0.1

Type RM Length L Ch R = 1 ,3093    ,597,597,597
BEGIN DESCRIPTION:
UNT 0326 IN LACR 3.0
END DESCRIPTION:
XS GIS Cut Line= 3
      3644995.17     10630282.41      3645088.94     10629943.82
      3644995.18      10629628.7
#Sta/Elev= 30
    4708  299.86  4876.1  292.34  4917.8  290.49  4926.9  289.09    4932  289.64
    4949  288.09  4959.3  288.76  4966.3  288.53  4971.5  287.33  4990.5  287.53
  5002.8   285.1  5005.6   284.6  5008.8   285.1  5011.2  288.15  5063.8   289.6
  5076.6  290.52  5085.2  292.78  5136.2  299.34    5157  304.86  5167.5   308.9
  5181.4   311.5  5188.3  315.85  5198.8  319.08  5209.2  320.48  5219.8  323.92
  5240.5  327.93    5260  329.58  5313.5  332.12  5324.6  333.96  5388.1  335.23
#Mann= 6 ,-1 , 0
    4708     .16       0  4876.1     .12       0  5002.8     .07       0
  5008.8     .12       0  5085.2     .16       0    5260     .05       0
Bank Sta=5002.8,5008.8
XS Rating Curve= 0 ,0
Exp/Cntr=0.3,0.1

Type RM Length L Ch R = 1 ,2496    ,295,295,295
BEGIN DESCRIPTION:
UNT 0326 IN LACR 2.0
END DESCRIPTION:
XS GIS Cut Line= 3
      3645449.62     10630360.17        3645597.       10630050.
      3645549.62     10629860.23
#Sta/Elev= 30
  4656.6   292.3  4687.9   290.2  4710.6  289.12  4716.1  289.68  4784.3  286.03
  4789.8  286.36  4812.6  285.88  4852.5  284.31  4971.6  282.04  4977.6  280.88
  4988.7  280.86  4994.2  279.25    4997  278.75  5000.2  279.25  5002.5  279.25
  5012.6  281.45  5030.7  280.89  5061.6  283.28  5082.3  283.99  5089.9  286.78
  5095.1  287.34  5107.8  290.29  5123.5  292.56  5136.3  298.05  5154.4  303.18
  5164.7  304.23  5172.4  306.56  5185.3  308.07  5193.1  310.03  5195.6  310.03
#Mann= 4 ,-1 , 0
  4656.6     .05       0  4994.2     .04       0  5000.2     .05       0
  5107.8     .16       0
Bank Sta=4994.2,5000.2
XS Rating Curve= 0 ,0
Exp/Cntr=0.3,0.1

Type RM Length L Ch R = 1 ,2201    ,287,287,287
BEGIN DESCRIPTION:
Mapping XS 07a239bd
END DESCRIPTION:
XS GIS Cut Line= 3
      3646146.21     10630326.61      3645833.73     10629857.89
      3645404.35     10629608.07
#Sta/Elev= 30
  4331.9  296.34  4334.2  295.16  4355.2  295.07  4376.3  291.43  4405.3  291.23
  4427.3  290.21  4440.1  287.91  4550.5  281.69  4802.9  280.23    4839   277.2
    4860  279.36  4911.6  278.32  4992.6  277.95  4999.2  277.58    5002     275
  5004.7   274.5    5008     275  5014.9  277.37  5050.4  280.97  5073.5  286.88
    5101  289.15  5108.3  290.68  5116.7  295.26  5122.7   295.6  5138.2  298.46
  5166.1  299.49  5218.5  299.19  5298.7  294.23    5363   294.9    5392  297.29
#Mann= 8 ,-1 , 0
  4331.9     .05       0  4405.3     .08       0  4440.1     .05       0
  4911.6     .16       0    5002     .07       0    5008     .16       0
  5122.7     .05       0    5363     .08       0
Bank Sta=5002,5008
XS Rating Curve= 0 ,0
Exp/Cntr=0.3,0.1

Type RM Length L Ch R = 1 ,1914    ,583,583,583
BEGIN DESCRIPTION:
Mapping XS f57fa4cd
END DESCRIPTION:
XS GIS Cut Line= 3
      3646234.75     10630001.08      3646075.92     10629730.28
      3645414.58     10629446.48
#Sta/Elev= 30
  4594.8  278.09  4709.8   275.7  4839.3  276.04  4897.3  274.74  4944.4  275.64
  4973.9  275.64  4988.8  272.94  4991.5  272.44  4994.8  272.94  5002.9  273.41
  5013.5  276.08  5035.3  274.89  5044.6     276    5050  275.18    5079  275.67
  5118.3  277.95  5165.9   281.2  5225.8  288.04    5273  289.96  5278.4  288.98
  5325.5  289.02    5331  287.63  5430.7   284.6  5454.2  284.86  5530.3  287.77
  5535.9  289.27  5577.5  293.42  5582.9  293.12  5595.9   295.1  5628.4  299.11
#Mann= 6 ,-1 , 0
  4594.8     .05       0  4944.4     .16       0  4988.8     .07       0
  4994.8     .16       0  5118.3     .05       0  5595.9     .08       0
Bank Sta=4988.8,4994.8
XS Rating Curve= 0 ,0
Exp/Cntr=0.3,0.1

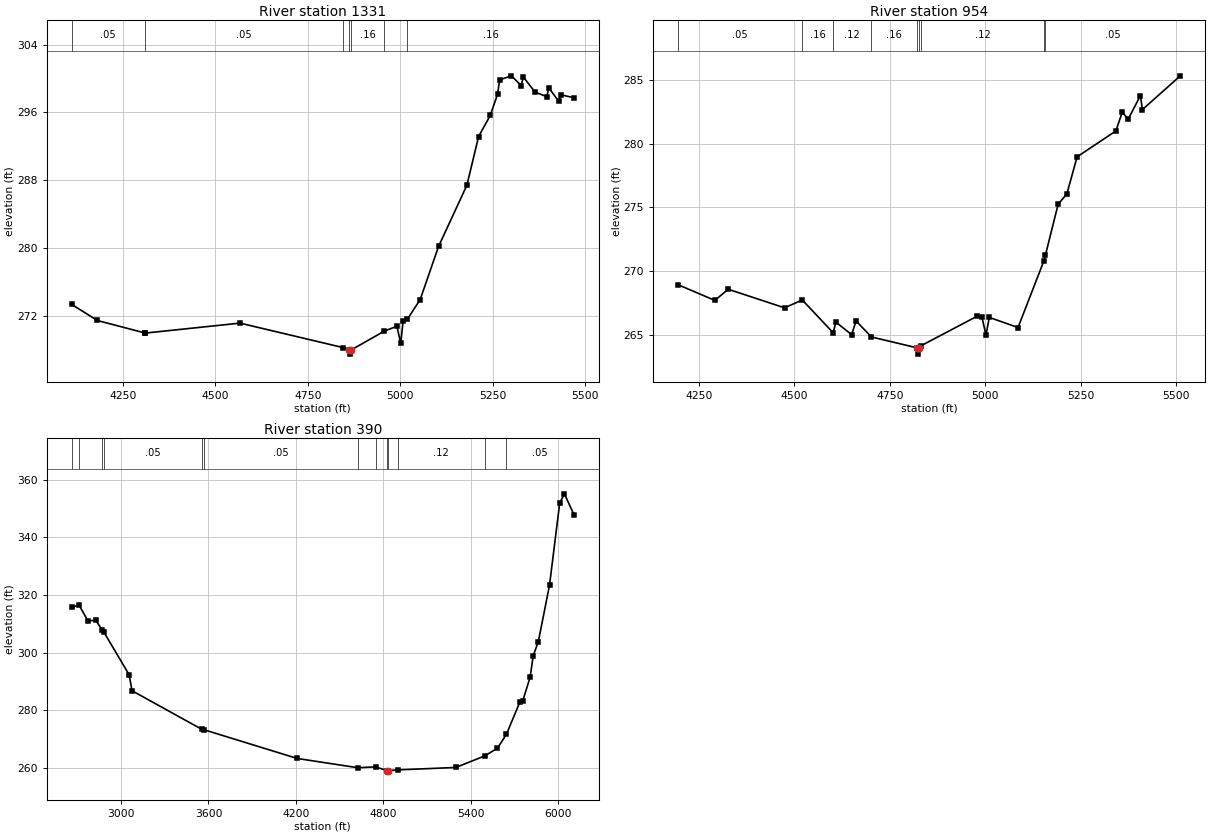
Type RM Length L Ch R = 1 ,1331    ,377,377,377
BEGIN DESCRIPTION:
Mapping XS dcd2f8cd
END DESCRIPTION:
XS GIS Cut Line= 4
     3646339.886    10629799.802     3646331.125    10629602.678
     3645995.187    10629251.115     3645354.562    10629042.782
#Sta/Elev= 30
4111.838273.3345 4180.95271.4412  4309.3269.9711  4309.3  269.95  4566.7  271.13
  4845.4  268.24  4861.5  267.97  4864.3  267.47  4867.5  267.97  4956.9  270.19
  4990.7  270.76  5001.2  268.76  5007.6   271.4  5019.2   271.6  5053.8  273.92
  5103.5   280.2    5180  287.41  5211.6  293.16  5243.1  295.65  5263.2   298.2
  5268.4  299.86  5300.4  300.33    5327  299.17  5332.3  300.21  5364.2  298.41
  5396.2  297.87  5401.4  298.92  5428.1  297.32  5433.4   298.1  5469.2  297.74
#Mann= 7 ,-1 , 0
4111.838     .05       0  4309.3     .05       0  4845.4     .16       0
  4861.5     .07       0  4867.5     .16       0  4956.9     .12       0
  5019.2     .16       0
Bank Sta=4861.5,4867.5
XS Rating Curve= 0 ,0
Exp/Cntr=0.3,0.1

Type RM Length L Ch R = 1 ,954     ,564,564,564
BEGIN DESCRIPTION:
Mapping XS 6716b2d6
END DESCRIPTION:
XS GIS Cut Line= 3
      3646354.55     10629498.48       3646130.6     10628969.87
      3645424.88      10628743.3
#Sta/Elev= 30
  4195.6  268.96  4291.5  267.74  4326.6  268.61  4474.1  267.16  4520.7  267.77
  4601.5  265.21  4608.7  266.04  4649.9  265.06  4661.5  266.13  4701.9  264.88
  4820.3  264.04    4823  263.54  4826.3  264.04  4831.3  264.19  4978.4   266.5
  4991.3  266.43  5001.8  265.03  5010.5  266.41  5085.8  265.62  5153.7  270.84
  5157.4  271.26  5190.9  275.26  5213.7  276.06  5240.6  278.96  5342.1  280.98
  5358.9  282.46  5374.3  281.89  5406.4  283.75  5411.6  282.65  5510.9  285.29
#Mann= 9 ,-1 , 0
  4195.6     .05       0  4520.7     .16       0  4601.5     .12       0
  4701.9     .16       0  4820.3     .07       0  4826.3     .16       0
  4831.3     .12       0  5153.7     .16       0  5157.4     .05       0
Bank Sta=4820.3,4826.3
XS Rating Curve= 0 ,0
Exp/Cntr=0.3,0.1

Type RM Length L Ch R = 1 ,390     ,0,0,0
BEGIN DESCRIPTION:
UNT 0326 IN LACR 1.0
END DESCRIPTION:
XS GIS Cut Line= 4
       3646255.9     10630700.76      3646479.85     10628778.88
      3646078.81     10628409.09       3645136.1     10628216.38
#Sta/Elev= 30
  2662.8  315.72  2711.8   316.6  2774.1  311.04    2827  311.28  2870.5  308.02
  2881.1  307.33    3056  292.38  3076.1  286.82  3556.1  273.41    3572  273.26
  4207.8  263.35  4623.5  260.13  4745.5  260.42  4827.2   259.1    4830   258.6
  4833.2   259.1  4898.2  259.38  5295.5  260.22  5494.1  264.21  5581.3   266.9
  5642.8  271.68  5734.4  282.82  5754.8   283.3  5805.8  291.58  5826.2  298.91
  5861.8  303.88  5938.5  323.45  6008.2  351.93  6040.6  355.13  6105.4  347.95
#Mann= 13 ,-1 , 0
  2662.8     .16       0  2711.8     .05       0  2870.5     .08       0
  2881.1     .05       0  3556.1     .12       0    3572     .05       0
  4623.5     .12       0  4745.5     .05       0  4827.2     .07       0
  4833.2     .05       0  4898.2     .12       0  5494.1     .16       0
  5642.8     .05       0
Bank Sta=4827.2,4833.2
XS Rating Curve= 0 ,0
Exp/Cntr=0.3,0.1

Chan Stop Cuts=-1
Use User Specified Reach Order=0
Composite Channel Slope=5