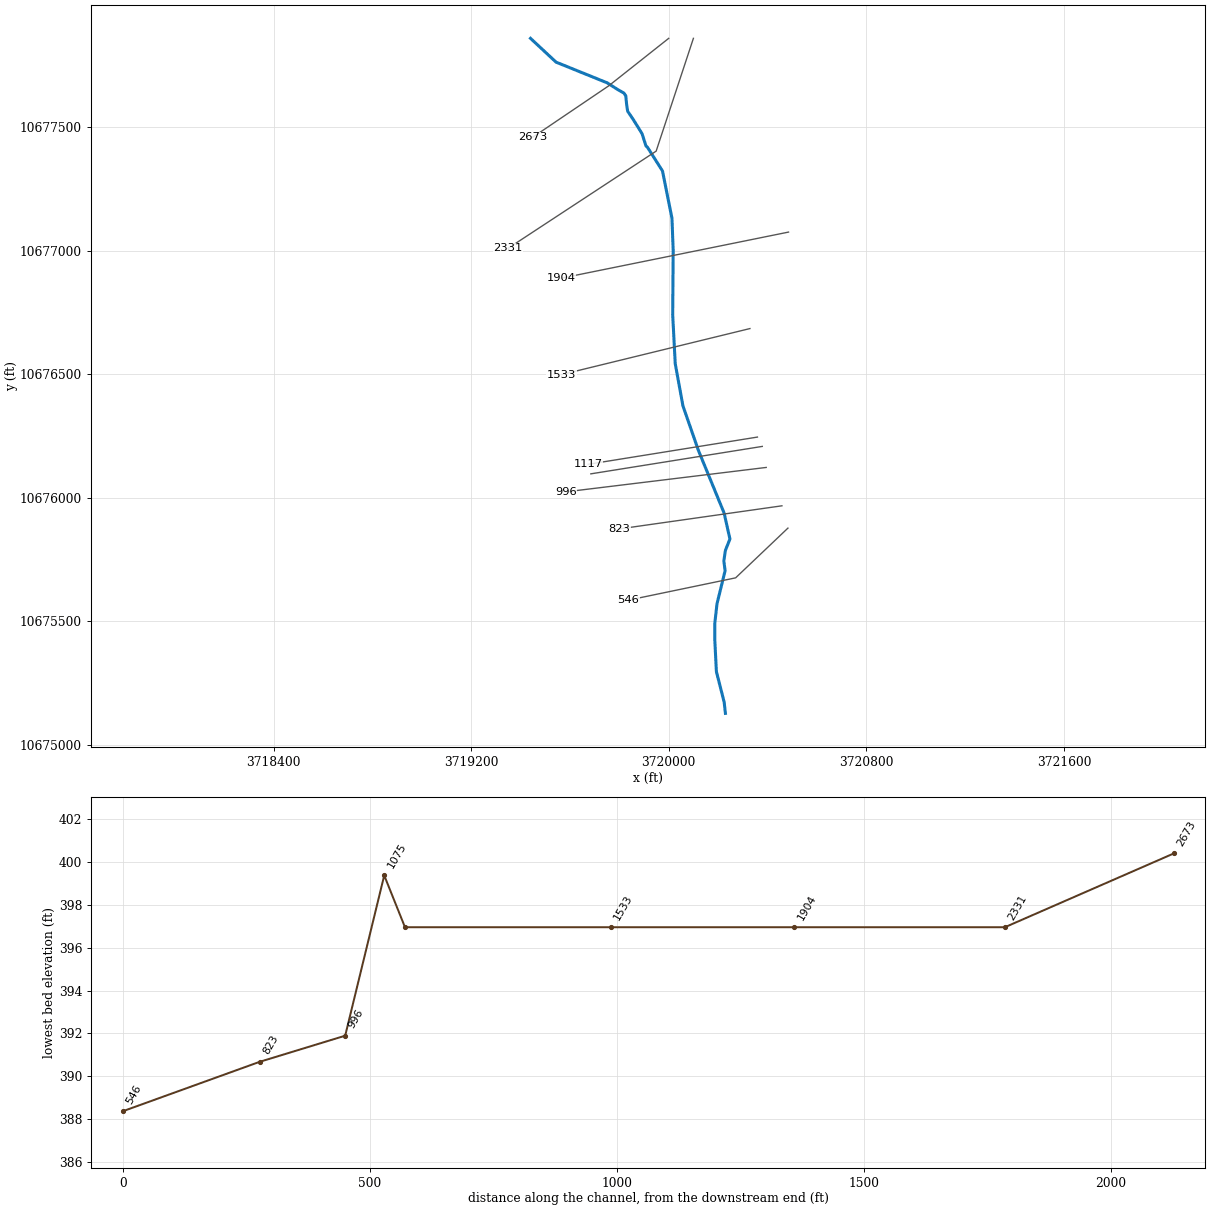
--- UNT 03268 IN LACR.prj (project) ---

Proj Title=UNT 03268 IN LACR Base Level Engineering
Current Plan=p01
Default Exp/Contr=0.3,0.1
English Units
Geom File=g01
Flow File=f01
Plan File=p01
BEGIN DESCRIPTION:
UNT 03268 IN LACR
END DESCRIPTION:

--- UNT 03268 IN LACR.p01 (plan) ---

Plan Title=Multiple Run
Short Identifier=Multiple
Geom File=g01
Flow File=f01
Subcritical Flow
K Sum by GR= 0
Std Step Tol= 0.01
Critical Tol= 0.01
Num of Std Step Trials= 20
Max Error Tol= 0.3
Flow Tol Ratio= 0.001
Split Flow NTrial= 30
Split Flow Tol= 0.02
Split Flow Ratio= 0.02
Log Output Level= 0
Friction Slope Method= 1
Unsteady Friction Slope Method= 2
Unsteady Bridges Friction Slope Method= 1
Parabolic Critical Depth
Global Vel Dist=  1 , 1 , 1
Global Log Level= 0
CheckData=True
Encroach Param= -1, 0, 0, 0
BEGIN DESCRIPTION:
Multiple Run
END DESCRIPTION:

--- UNT 03268 IN LACR.f01 (steady flow) ---

Flow Title=Multiple
Number of Profiles=7
Profile Names=10-year,25-year,50-year,1pct_min,100-year,1pct_plu,500-year
River Rch & RM= UNT 03268 IN LAC,Reach-1,2673
     153     189     216     182     246     333     321
Boundary for River Rch & Prof#=UNT 03268 IN LAC,Reach-1,1
Up Type=0
Dn Type=3
Dn Slope=0.005
Boundary for River Rch & Prof#=UNT 03268 IN LAC,Reach-1,2
Up Type=0
Dn Type=3
Dn Slope=0.005
Boundary for River Rch & Prof#=UNT 03268 IN LAC,Reach-1,3
Up Type=0
Dn Type=3
Dn Slope=0.005
Boundary for River Rch & Prof#=UNT 03268 IN LAC,Reach-1,4
Up Type=0
Dn Type=3
Dn Slope=0.005
Boundary for River Rch & Prof#=UNT 03268 IN LAC,Reach-1,5
Up Type=0
Dn Type=3
Dn Slope=0.005
Boundary for River Rch & Prof#=UNT 03268 IN LAC,Reach-1,6
Up Type=0
Dn Type=3
Dn Slope=0.005
Boundary for River Rch & Prof#=UNT 03268 IN LAC,Reach-1,7
Up Type=0
Dn Type=3
Dn Slope=0.005

--- UNT 03268 IN LACR.g01 (geometry) ---

Geom Title=Existing Conditions

River Reach=UNT 03268 IN LAC,Reach-1
Reach XY= 30
      3719440.10     10677860.13      3719543.52     10677763.81
      3719750.12     10677680.23      3719793.87     10677652.45
      3719818.18     10677638.56      3719825.82     10677627.45
      3719829.29     10677592.04      3719833.46     10677564.95
      3719856.37     10677530.93      3719891.79     10677473.98
      3719907.34     10677424.97      3719913.75     10677419.00
      3719974.50     10677323.00      3720012.75     10677132.00
      3720017.75     10677002.00      3720015.75     10676741.00
      3720026.00     10676543.00      3720057.25     10676372.00
      3720119.75     10676192.00      3720224.00     10675938.00
      3720247.50     10675833.00      3720229.25     10675787.00
      3720222.75     10675744.00      3720228.00     10675705.00
      3720195.25     10675571.00      3720186.25     10675492.00
      3720186.25     10675423.00      3720192.75     10675296.00
      3720224.00     10675173.00      3720229.25     10675127.00

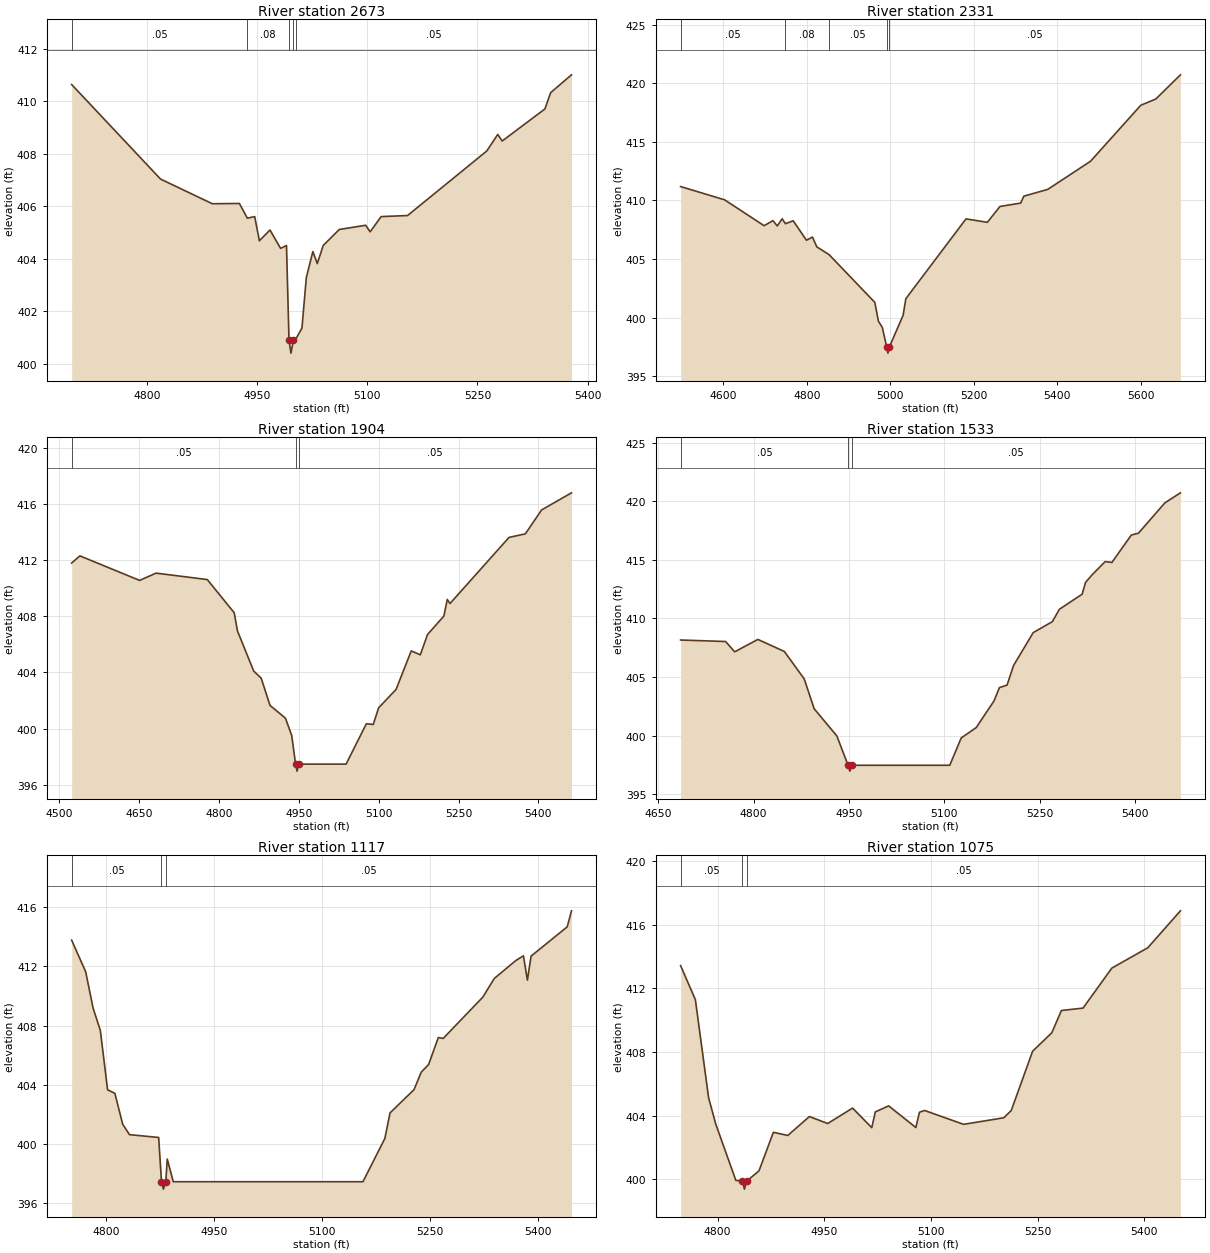
Type RM Length L Ch R = 1,2673,342,342,342
BEGIN DESCRIPTION:
UNT 03268 IN LACR 6.0
END DESCRIPTION:
XS GIS Cut Line= 3
      3719999.59     10677860.18      3719756.07     10677667.42
      3719449.63     10677460.20
#Sta/Elev= 30
  4697.5  410.64  4818.5  407.04  4889.0  406.10  4925.9  406.11  4936.7  405.55
  4946.7  405.61  4953.1  404.69  4967.5  405.10  4981.9  404.40  4990.0  404.51
  4993.4  400.91  4996.1  400.41  4999.4  400.91  5003.5  400.99  5011.0  401.36
  5017.0  403.29  5025.9  404.28  5031.9  403.82  5040.0  404.51  5061.9  405.12
  5097.8  405.28  5103.9  405.03  5118.8  405.61  5154.8  405.65  5262.7  408.11
  5277.6  408.74  5283.7  408.49  5341.8  409.71  5349.6  410.33  5378.0  411.01
#Mann=5,-1,0
  4697.5    0.05       0  4936.7    0.08       0  4993.4    0.07       0
  4999.4    0.08       0  5003.5    0.05       0
Bank Sta=4993.4,4999.4
Exp/Cntr=0.3,0.1

Type RM Length L Ch R = 1,2331,427,427,427
BEGIN DESCRIPTION:
UNT 03268 IN LACR 5.0
END DESCRIPTION:
XS GIS Cut Line= 3
      3720099.62     10677860.23      3719948.78     10677403.53
      3719349.62     10677010.20
#Sta/Elev= 30
  4497.7  411.18  4603.1  410.05  4697.8  407.84  4718.9  408.27  4729.4  407.82
  4741.1  408.43  4748.9  408.01  4767.5  408.26  4799.3  406.60  4813.7  406.87
  4824.2  406.03  4853.5  405.37  4963.2  401.29  4971.7  399.69  4981.2  399.14
  4991.7  397.46  4994.5  396.96  4997.7  397.46  5030.9  400.19  5037.5  401.61
  5181.6  408.42  5232.8  408.13  5263.0  409.48  5312.6  409.77  5320.2  410.36
  5377.5  410.94  5480.0  413.34  5600.4  418.12  5636.6  418.66  5695.4  420.72
#Mann=5,-1,0
  4497.7    0.05       0  4748.9    0.08       0  4853.5    0.05       0
  4991.7    0.03       0  4997.7    0.05       0
Bank Sta=4991.7,4997.7
Exp/Cntr=0.3,0.1

Type RM Length L Ch R = 1,1904,371,371,371
BEGIN DESCRIPTION:
UNT 03268 IN LACR 4.0
END DESCRIPTION:
XS GIS Cut Line= 2
      3720484.78     10677075.73      3719564.61     10676889.09
#Sta/Elev= 30
  4523.3  411.81  4538.8  412.32  4651.0  410.57  4681.8  411.09  4778.1  410.63
  4828.7  408.26  4834.7  406.97  4865.3  404.10  4879.4  403.59  4895.9  401.65
  4924.9  400.74  4936.7  399.50  4943.9  397.46  4946.7  396.96  4949.9  397.46
  5038.8  397.46  5076.9  400.34  5089.8  400.29  5100.0  401.48  5132.7  402.79
  5161.2  405.54  5178.2  405.26  5191.8  406.71  5222.4  408.02  5228.9  409.21
  5234.0  408.92  5344.9  413.64  5375.5  413.89  5406.1  415.60  5462.2  416.82
#Mann=3,-1,0
  4523.3    0.05       0  4943.9    0.03       0  4949.9    0.05       0
Bank Sta=4943.9,4949.9
Exp/Cntr=0.3,0.1

Type RM Length L Ch R = 1,1533,416,416,416
BEGIN DESCRIPTION:
UNT 03268 IN LACR 3.0
END DESCRIPTION:
XS GIS Cut Line= 2
      3720328.51     10676685.10      3719564.58     10676498.46
#Sta/Elev= 30
  4685.0  408.15  4755.9  408.02  4770.1  407.14  4806.6  408.20  4848.3  407.17
  4879.5  404.83  4895.1  402.29  4930.9  399.96  4948.5  397.46  4951.3  396.96
  4954.5  397.46  5108.5  397.46  5126.5  399.79  5150.2  400.68  5178.0  402.94
  5186.7  404.09  5198.6  404.30  5208.9  405.98  5239.8  408.78  5270.0  409.72
  5280.9  410.77  5316.8  412.06  5322.1  413.06  5332.4  413.71  5353.0  414.84
  5363.6  414.77  5394.2  417.11  5405.3  417.26  5446.9  419.85  5471.4  420.71
#Mann=3,-1,0
  4685.0    0.05       0  4948.5   0.033       0  4954.5    0.05       0
Bank Sta=4948.5,4954.5
Exp/Cntr=0.3,0.1

Type RM Length L Ch R = 1,1117,42,42,42
BEGIN DESCRIPTION:
Mapping XS 49655244
END DESCRIPTION:
XS GIS Cut Line= 2
      3720358.89     10676245.75      3719673.80     10676135.53
#Sta/Elev= 30
  4752.7  413.78  4772.2  411.64  4782.4  409.20  4792.5  407.68  4802.6  403.67
  4812.7  403.43  4823.6  401.34  4833.0  400.64  4873.5  400.45  4877.4  397.46
  4880.1  396.96  4883.4  397.46  4885.4  398.99  4893.8  397.46  5157.1  397.46
  5187.5  400.38  5194.7  402.11  5228.0  403.68  5238.1  404.87  5248.3  405.38
  5261.7  407.20  5268.5  407.14  5323.5  409.93  5339.4  411.19  5369.8  412.42
  5379.9  412.72  5385.4  411.08  5390.5  412.70  5440.7  414.68  5446.6  415.76
#Mann=3,-1,0
  4752.7    0.05       0  4877.4    0.03       0  4883.4    0.05       0
Bank Sta=4877.4,4883.4
Exp/Cntr=0.3,0.1

Type RM Length L Ch R = 1,1075,79,79,79
BEGIN DESCRIPTION:
UNT 03268 IN LACR 2.0
END DESCRIPTION:
XS GIS Cut Line= 2
      3720378.49     10676207.93      3719684.32     10676096.86
#Sta/Elev= 30
  4747.9  413.42  4768.7  411.28  4787.3  405.12  4797.4  403.46  4825.6  399.93
  4834.9  399.88  4837.7  399.38  4840.9  399.88  4858.2  400.53  4878.4  402.95
  4898.7  402.75  4929.1  403.94  4954.8  403.50  4989.8  404.47  5016.8  403.24
  5021.8  404.23  5040.5  404.61  5078.8  403.25  5083.9  404.21  5091.1  404.32
  5145.9  403.45  5202.5  403.86  5213.0  404.32  5243.0  408.04  5270.0  409.20
  5283.5  410.60  5313.9  410.75  5354.4  413.26  5405.0  414.54  5450.9  416.86
#Mann=3,-1,0
  4747.9    0.05       0  4834.9    0.03       0  4840.9    0.05       0
Bank Sta=4834.9,4840.9
Exp/Cntr=0.3,0.1

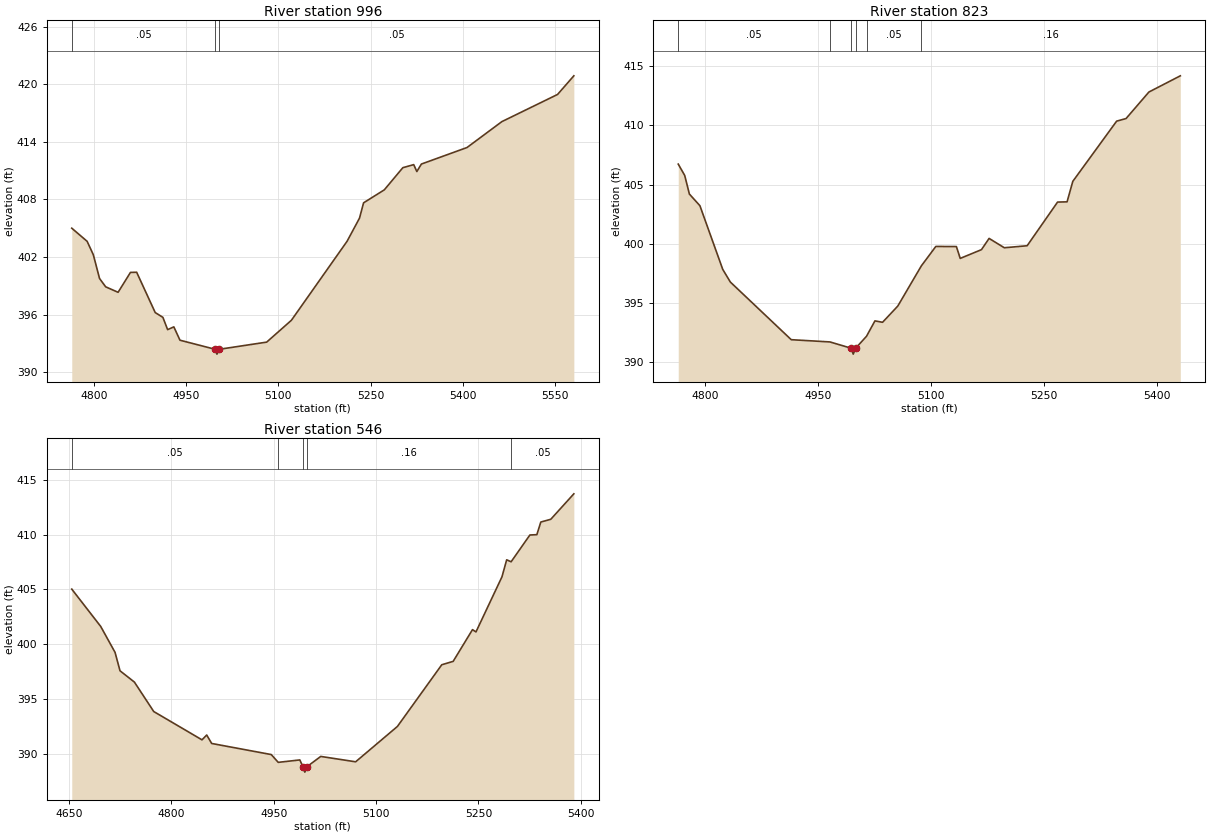
Type RM Length L Ch R = 1,996,173,173,173
BEGIN DESCRIPTION:
Mapping XS 7dfa7038
END DESCRIPTION:
XS GIS Cut Line= 2
      3720394.45     10676122.79      3719583.34     10676024.00
#Sta/Elev= 30
  4763.7  405.01  4788.7  403.64  4798.8  402.24  4808.9  399.77  4818.9  398.90
  4839.1  398.33  4859.2  400.40  4869.3  400.42  4899.5  396.22  4912.0  395.72
  4919.7  394.44  4929.8  394.73  4939.8  393.34  4997.3  392.39  5000.0  391.89
  5003.3  392.39  5080.9  393.14  5121.2  395.42  5211.8  403.65  5232.0  406.06
  5238.6  407.65  5272.3  409.00  5302.5  411.31  5320.2  411.63  5325.3  410.91
  5332.7  411.69  5406.9  413.41  5463.7  416.11  5554.3  418.94  5580.8  420.88
#Mann=3,-1,0
  4763.7    0.05       0  4997.3    0.03       0  5003.3    0.05       0
Bank Sta=4997.3,5003.3
Exp/Cntr=0.3,0.1

Type RM Length L Ch R = 1,823,277,277,277
BEGIN DESCRIPTION:
Mapping XS 1b81a601
END DESCRIPTION:
XS GIS Cut Line= 2
      3720458.09     10675967.43      3719798.32     10675873.67
#Sta/Elev= 30
  4764.4  406.73  4773.0  405.77  4779.2  404.20  4793.2  403.21  4823.5  397.83
  4833.6  396.76  4914.4  391.89  4965.8  391.70  4993.9  391.17  4996.7  390.67
  4999.9  391.17  5014.3  392.18  5025.5  393.48  5035.6  393.36  5055.8  394.73
  5087.1  398.13  5106.3  399.77  5133.6  399.76  5138.7  398.76  5166.9  399.50
  5177.0  400.45  5197.2  399.66  5227.5  399.83  5267.9  403.52  5280.5  403.54
  5288.1  405.27  5346.3  410.36  5358.8  410.58  5389.1  412.82  5430.8  414.19
#Mann=6,-1,0
  4764.4    0.05       0  4965.8    0.16       0  4993.9    0.07       0
  4999.9    0.16       0  5014.3    0.05       0  5087.1    0.16       0
Bank Sta=4993.9,4999.9
Exp/Cntr=0.3,0.1

Type RM Length L Ch R = 1,546,0,0,0
BEGIN DESCRIPTION:
UNT 03268 IN LACR 1.0
END DESCRIPTION:
XS GIS Cut Line= 3
      3720482.40     10675877.18      3720270.56     10675675.76
      3719836.56     10675585.49
#Sta/Elev= 30
  4654.2  405.03  4696.6  401.63  4717.6  399.27  4724.9  397.59  4746.0  396.56
  4774.3  393.88  4845.0  391.30  4851.9  391.74  4859.2  390.97  4946.5  389.96
  4956.7  389.25  4988.3  389.47  4992.9  388.86  4995.7  388.36  4998.9  388.86
  5019.0  389.79  5070.1  389.30  5131.3  392.52  5196.3  398.14  5213.0  398.45
  5241.3  401.34  5246.4  401.13  5284.5  406.15  5291.4  407.70  5297.9  407.52
  5325.4  409.96  5335.6  409.99  5341.4  411.14  5356.0  411.39  5389.8  413.71
#Mann=5,-1,0
  4654.2    0.05       0  4956.7    0.16       0  4992.9    0.07       0
  4998.9    0.16       0  5297.9    0.05       0
Bank Sta=4992.9,4998.9
Exp/Cntr=0.3,0.1

Chan Stop Cuts=-1