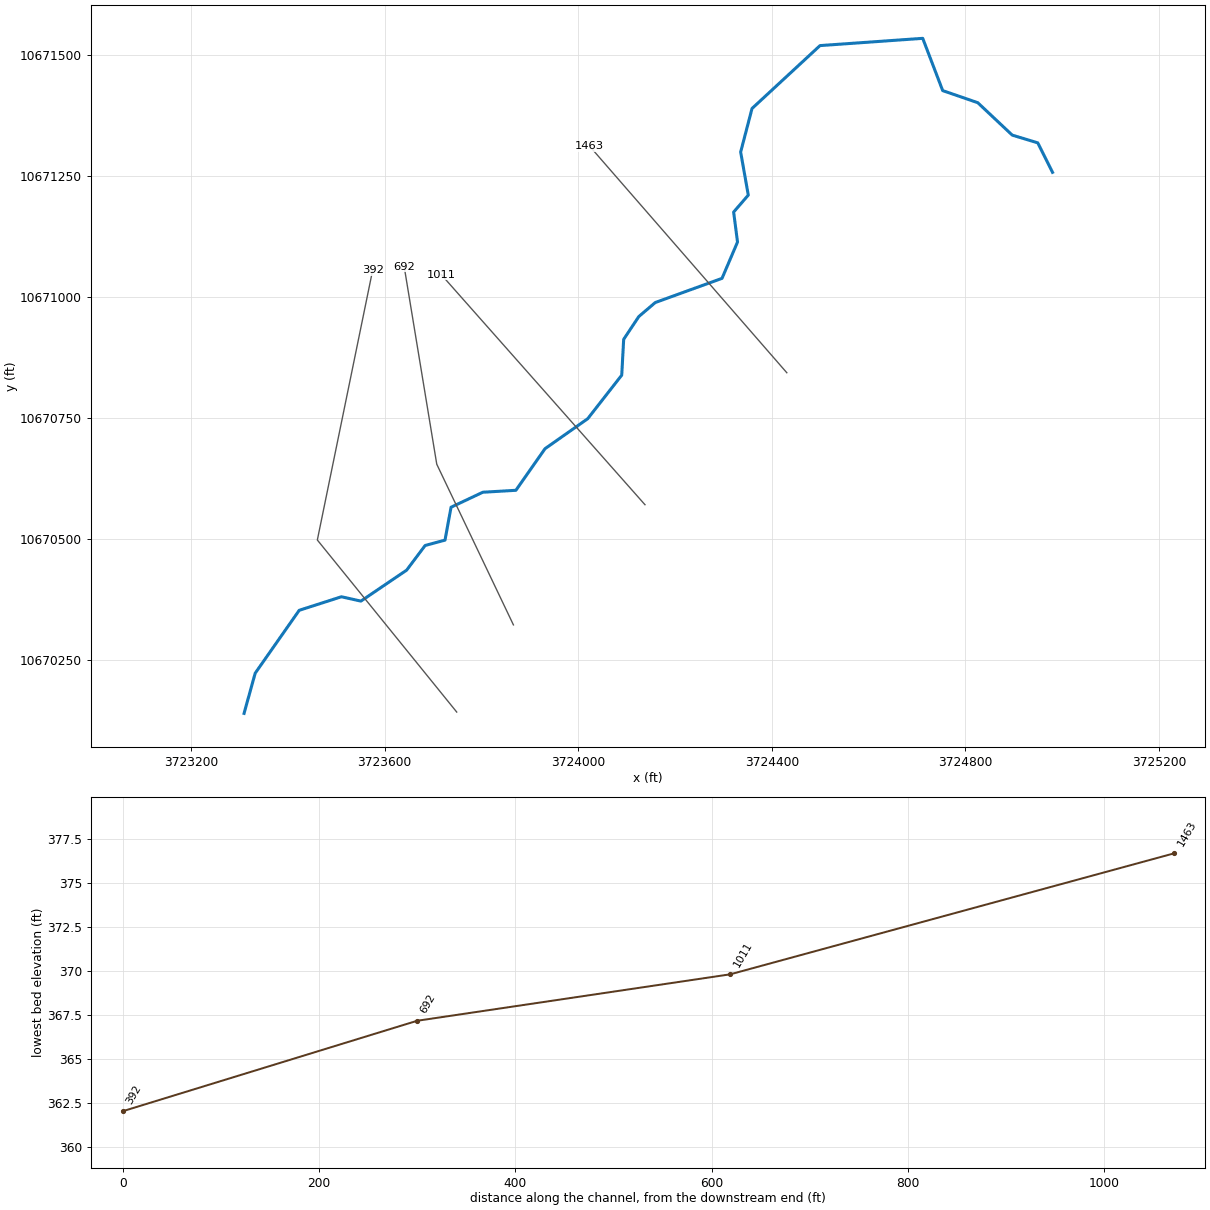
--- UNT 03276 IN LACR.prj (project) ---

Proj Title=UNT 03276 IN LACR Base Level Engineering
Current Plan=p01
Default Exp/Contr=0.3,0.1
English Units
Geom File=g01
Flow File=f01
Plan File=p01
BEGIN DESCRIPTION:
UNT 03276 IN LACR
END DESCRIPTION:

--- UNT 03276 IN LACR.p01 (plan) ---

Plan Title=Multiple Run
Short Identifier=Multiple
Geom File=g01
Flow File=f01
Subcritical Flow
K Sum by GR= 0
Std Step Tol= 0.01
Critical Tol= 0.01
Num of Std Step Trials= 20
Max Error Tol= 0.3
Flow Tol Ratio= 0.001
Split Flow NTrial= 30
Split Flow Tol= 0.02
Split Flow Ratio= 0.02
Log Output Level= 0
Friction Slope Method= 1
Unsteady Friction Slope Method= 2
Unsteady Bridges Friction Slope Method= 1
Parabolic Critical Depth
Global Vel Dist=  1 , 1 , 1
Global Log Level= 0
CheckData=True
Encroach Param= -1, 0, 0, 0
BEGIN DESCRIPTION:
Multiple Run
END DESCRIPTION:

--- UNT 03276 IN LACR.f01 (steady flow) ---

Flow Title=Multiple
Number of Profiles=7
Profile Names=10-year,25-year,50-year,1pct_min,100-year,1pct_plu,500-year
River Rch & RM= UNT 03276 IN LAC,Reach-1,1463
     440     589     711     632     855    1156    1239
Boundary for River Rch & Prof#=UNT 03276 IN LAC,Reach-1,1
Up Type=0
Dn Type=3
Dn Slope=0.005
Boundary for River Rch & Prof#=UNT 03276 IN LAC,Reach-1,2
Up Type=0
Dn Type=3
Dn Slope=0.005
Boundary for River Rch & Prof#=UNT 03276 IN LAC,Reach-1,3
Up Type=0
Dn Type=3
Dn Slope=0.005
Boundary for River Rch & Prof#=UNT 03276 IN LAC,Reach-1,4
Up Type=0
Dn Type=3
Dn Slope=0.005
Boundary for River Rch & Prof#=UNT 03276 IN LAC,Reach-1,5
Up Type=0
Dn Type=3
Dn Slope=0.005
Boundary for River Rch & Prof#=UNT 03276 IN LAC,Reach-1,6
Up Type=0
Dn Type=3
Dn Slope=0.005
Boundary for River Rch & Prof#=UNT 03276 IN LAC,Reach-1,7
Up Type=0
Dn Type=3
Dn Slope=0.005

--- UNT 03276 IN LACR.g01 (geometry) ---

Geom Title=Existing Conditions

River Reach=UNT 03276 IN LAC,Reach-1
Reach XY= 30
      3724980.24     10671258.11      3724949.75     10671319.00
      3724897.00     10671335.00      3724825.75     10671402.00
      3724753.25     10671427.00      3724712.00     10671535.00
      3724499.75     10671520.00      3724359.25     10671390.00
      3724335.75     10671300.00      3724351.50     10671211.00
      3724321.25     10671176.00      3724329.25     10671114.00
      3724297.25     10671039.00      3724159.25     10670989.00
      3724125.25     10670960.00      3724094.00     10670913.00
      3724090.00     10670839.00      3724019.75     10670749.00
      3723931.50     10670687.00      3723871.25     10670601.00
      3723803.00     10670597.00      3723737.25     10670566.00
      3723724.75     10670498.00      3723683.75     10670487.00
      3723645.50     10670436.00      3723551.00     10670372.00
      3723510.75     10670381.00      3723423.50     10670353.00
      3723332.50     10670223.00      3723309.50     10670140.00

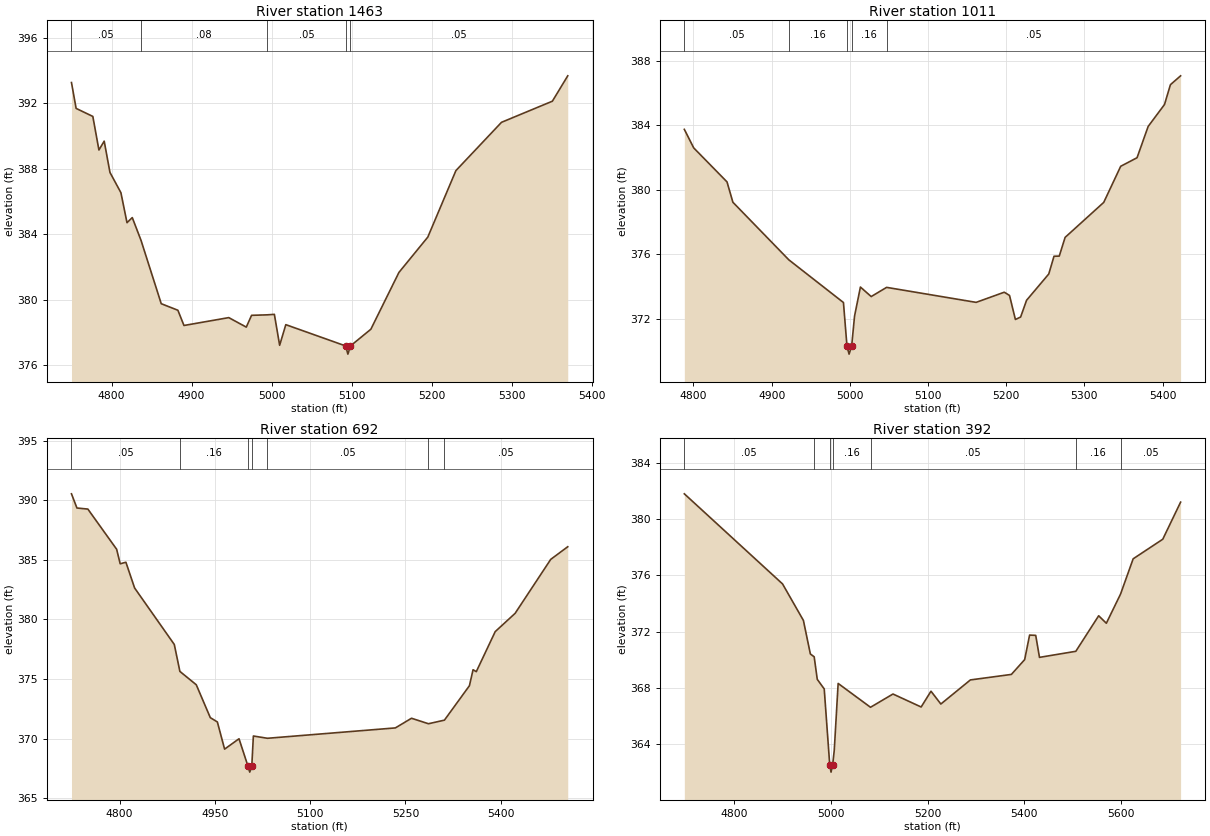
Type RM Length L Ch R = 1,1463,452,452,452
BEGIN DESCRIPTION:
UNT 03276 IN LACR 4.0
END DESCRIPTION:
XS GIS Cut Line= 2
      3724431.14     10670843.92      3724023.89     10671311.81
#Sta/Elev= 30
  4749.9  393.28  4755.7  391.70  4776.6  391.21  4784.2  389.16  4790.8  389.70
  4798.0  387.79  4811.7  386.55  4819.3  384.72  4825.9  385.03  4836.9  383.63
  4862.1  379.77  4882.9  379.37  4890.5  378.44  4946.5  378.92  4968.4  378.34
  4975.0  379.06  4994.6  379.09  5003.5  379.12  5010.1  377.23  5017.8  378.49
  5092.6  377.19  5095.4  376.69  5098.6  377.19  5124.1  378.21  5159.2  381.68
  5195.3  383.84  5230.4  387.90  5287.4  390.85  5351.0  392.14  5370.2  393.69
#Mann=5,-1,0
  4749.9    0.05       0  4836.9    0.08       0  4994.6    0.05       0
  5092.6    0.03       0  5098.6    0.05       0
Bank Sta=5092.6,5098.6
Exp/Cntr=0.3,0.1

Type RM Length L Ch R = 1,1011,319,319,319
BEGIN DESCRIPTION:
Mapping XS 63395f05
END DESCRIPTION:
XS GIS Cut Line= 2
      3724138.02     10670571.21      3723717.31     10671046.45
#Sta/Elev= 30
  4788.3  383.76  4800.3  382.61  4842.9  380.50  4850.4  379.24  4921.9  375.67
  4991.8  373.02  4996.3  370.32  4999.0  369.82  5002.3  370.32  5006.0  372.18
  5013.5  373.98  5027.3  373.39  5047.0  373.96  5161.5  373.03  5197.5  373.66
  5204.2  373.46  5211.7  371.97  5218.4  372.12  5226.0  373.16  5254.4  374.79
  5261.1  375.89  5267.8  375.90  5275.3  377.06  5324.7  379.23  5346.4  381.47
  5367.3  382.00  5381.5  383.94  5402.4  385.30  5410.0  386.53  5423.0  387.08
#Mann=5,-1,0
  4788.3    0.05       0  4921.9    0.16       0  4996.3    0.07       0
  5002.3    0.16       0  5047.0    0.05       0
Bank Sta=4996.3,5002.3
Exp/Cntr=0.3,0.1

Type RM Length L Ch R = 1,692,300,300,300
BEGIN DESCRIPTION:
Mapping XS c7edd983
END DESCRIPTION:
XS GIS Cut Line= 3
      3723866.15     10670322.87      3723707.73     10670654.91
      3723640.46     10671062.91
#Sta/Elev= 30
  4724.2  390.53  4732.8  389.34  4750.0  389.25  4795.3  385.88  4800.9  384.66
  4809.9  384.79  4823.6  382.63  4886.1  377.89  4894.9  375.63  4920.7  374.51
  4942.8  371.75  4953.9  371.39  4965.3  369.11  4988.0  369.98  5002.1  367.68
  5004.9  367.18  5008.1  367.68  5010.6  370.21  5032.8  370.02  5234.2  370.89
  5259.6  371.70  5286.3  371.24  5311.4  371.54  5350.8  374.43  5356.5  375.77
  5361.6  375.61  5391.4  378.97  5422.7  380.50  5478.8  385.03  5505.6  386.09
#Mann=7,-1,0
  4724.2    0.05       0  4894.9    0.16       0  5002.1    0.07       0
  5008.1    0.16       0  5032.8    0.05       0  5286.3    0.16       0
  5311.4    0.05       0
Bank Sta=5002.1,5008.1
Exp/Cntr=0.3,0.1

Type RM Length L Ch R = 1,392,0,0,0
BEGIN DESCRIPTION:
UNT 03276 IN LACR 1.0
END DESCRIPTION:
XS GIS Cut Line= 3
      3723748.99     10670142.73      3723460.94     10670498.29
      3723575.35     10671056.38
#Sta/Elev= 30
  4696.5  381.78  4899.8  375.39  4943.0  372.80  4957.4  370.42  4965.3  370.22
  4971.7  368.62  4986.1  367.94  4997.5  362.54  5000.2  362.04  5003.5  362.54
  5006.9  363.61  5014.9  368.33  5081.9  366.64  5128.4  367.58  5186.7  366.66
  5207.1  367.78  5227.5  366.87  5288.7  368.58  5373.5  368.97  5401.0  370.02
  5411.2  371.76  5423.9  371.74  5431.7  370.18  5506.9  370.61  5554.2  373.13
  5570.1  372.60  5599.5  374.67  5625.6  377.17  5686.9  378.56  5723.8  381.19
#Mann=7,-1,0
  4696.5    0.05       0  4965.3    0.16       0  4997.5    0.07       0
  5003.5    0.16       0  5081.9    0.05       0  5506.9    0.16       0
  5599.5    0.05       0
Bank Sta=4997.5,5003.5
Exp/Cntr=0.3,0.1

Chan Stop Cuts=-1