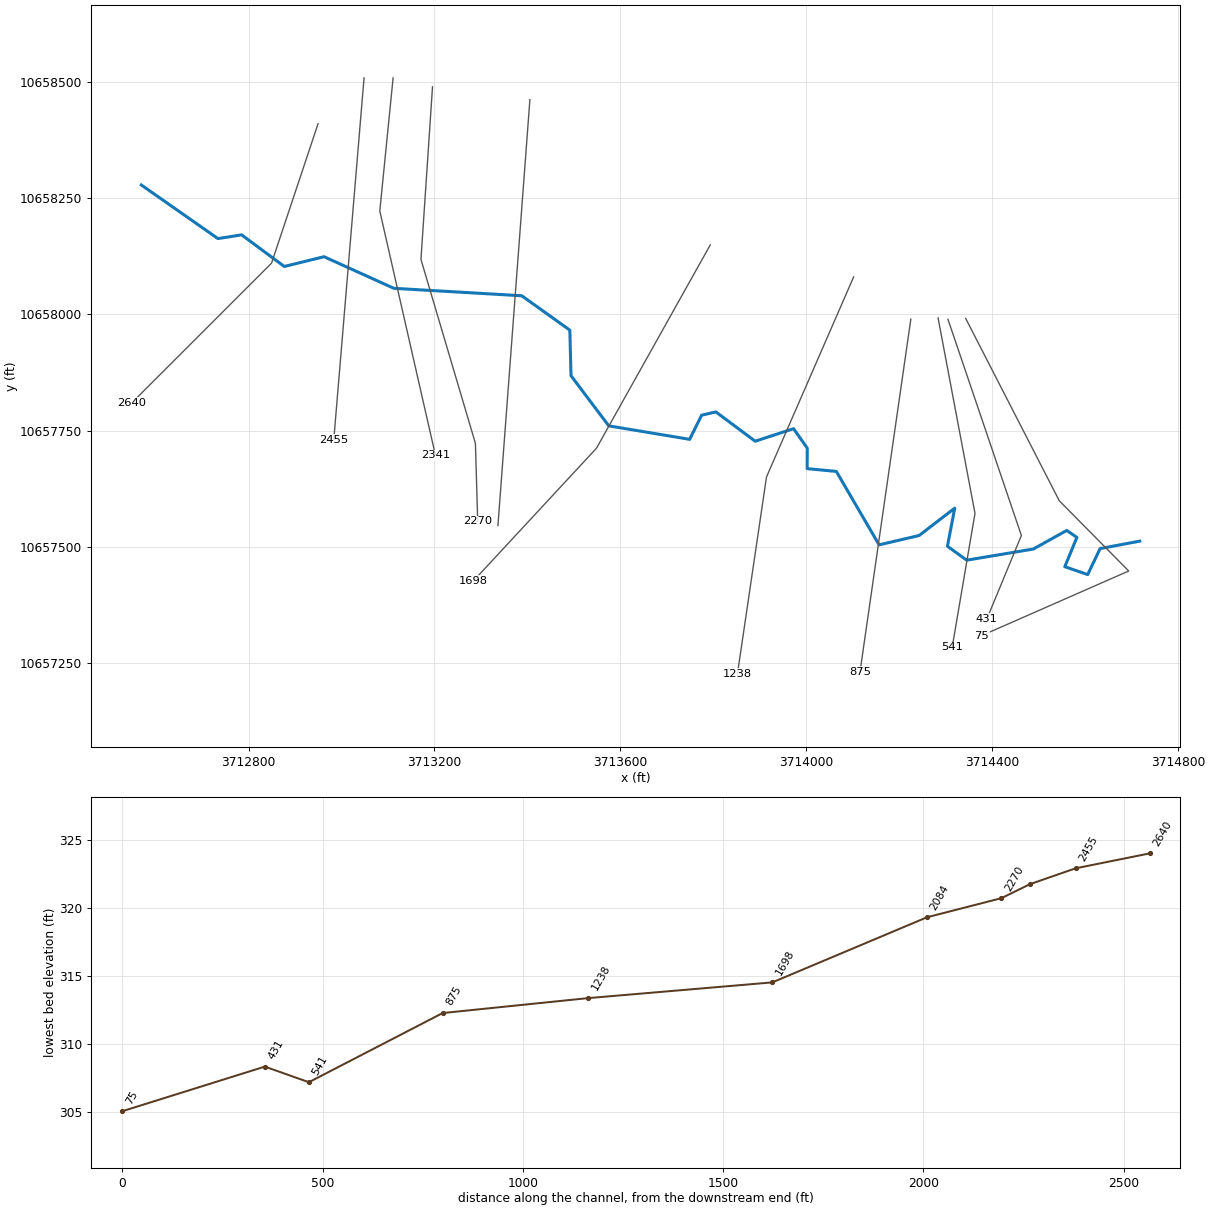
--- UNT 03296 IN LACR.prj (project) ---

Proj Title=UNT 03296 IN LACR Base Level Engineering
Current Plan=p01
Default Exp/Contr=0.3,0.1
English Units
Geom File=g01
Flow File=f01
Plan File=p01
BEGIN DESCRIPTION:
UNT 03296 IN LACR
END DESCRIPTION:

--- UNT 03296 IN LACR.p01 (plan) ---

Plan Title=Multiple Run
Short Identifier=Multiple
Geom File=g01
Flow File=f01
Subcritical Flow
K Sum by GR= 0
Std Step Tol= 0.01
Critical Tol= 0.01
Num of Std Step Trials= 20
Max Error Tol= 0.3
Flow Tol Ratio= 0.001
Split Flow NTrial= 30
Split Flow Tol= 0.02
Split Flow Ratio= 0.02
Log Output Level= 0
Friction Slope Method= 1
Unsteady Friction Slope Method= 2
Unsteady Bridges Friction Slope Method= 1
Parabolic Critical Depth
Global Vel Dist=  1 , 1 , 1
Global Log Level= 0
CheckData=True
Encroach Param= -1, 0, 0, 0
BEGIN DESCRIPTION:
Multiple Run
END DESCRIPTION:

--- UNT 03296 IN LACR.f01 (steady flow) ---

Flow Title=Multiple
Number of Profiles=7
Profile Names=10-year,25-year,50-year,1pct_min,100-year,1pct_plu,500-year
River Rch & RM= UNT 03296 IN LAC,Reach-1,2640
     298     387     458     400     541     732     756
Boundary for River Rch & Prof#=UNT 03296 IN LAC,Reach-1,1
Up Type=0
Dn Type=3
Dn Slope=0.005
Boundary for River Rch & Prof#=UNT 03296 IN LAC,Reach-1,2
Up Type=0
Dn Type=3
Dn Slope=0.005
Boundary for River Rch & Prof#=UNT 03296 IN LAC,Reach-1,3
Up Type=0
Dn Type=3
Dn Slope=0.005
Boundary for River Rch & Prof#=UNT 03296 IN LAC,Reach-1,4
Up Type=0
Dn Type=3
Dn Slope=0.005
Boundary for River Rch & Prof#=UNT 03296 IN LAC,Reach-1,5
Up Type=0
Dn Type=3
Dn Slope=0.005
Boundary for River Rch & Prof#=UNT 03296 IN LAC,Reach-1,6
Up Type=0
Dn Type=3
Dn Slope=0.005
Boundary for River Rch & Prof#=UNT 03296 IN LAC,Reach-1,7
Up Type=0
Dn Type=3
Dn Slope=0.005

--- UNT 03296 IN LACR.g01 (geometry) ---

Geom Title=Existing Conditions

River Reach=UNT 03296 IN LAC,Reach-1
Reach XY= 30
      3712569.43     10658278.35      3712734.25     10658163.00
      3712785.25     10658171.00      3712877.00     10658103.00
      3712962.50     10658124.00      3713112.75     10658056.00
      3713387.75     10658040.00      3713491.25     10657966.00
      3713493.75     10657868.00      3713575.00     10657760.00
      3713749.00     10657731.00      3713774.75     10657783.00
      3713805.50     10657790.00      3713890.00     10657727.00
      3713972.50     10657754.00      3714002.00     10657712.00
      3714001.75     10657668.00      3714064.50     10657662.00
      3714156.50     10657504.00      3714242.50     10657524.00
      3714319.25     10657583.00      3714303.50     10657501.00
      3714345.00     10657471.00      3714488.25     10657495.00
      3714560.25     10657535.00      3714582.00     10657520.00
      3714556.00     10657457.00      3714605.25     10657440.00
      3714632.00     10657496.00      3714717.25     10657512.00

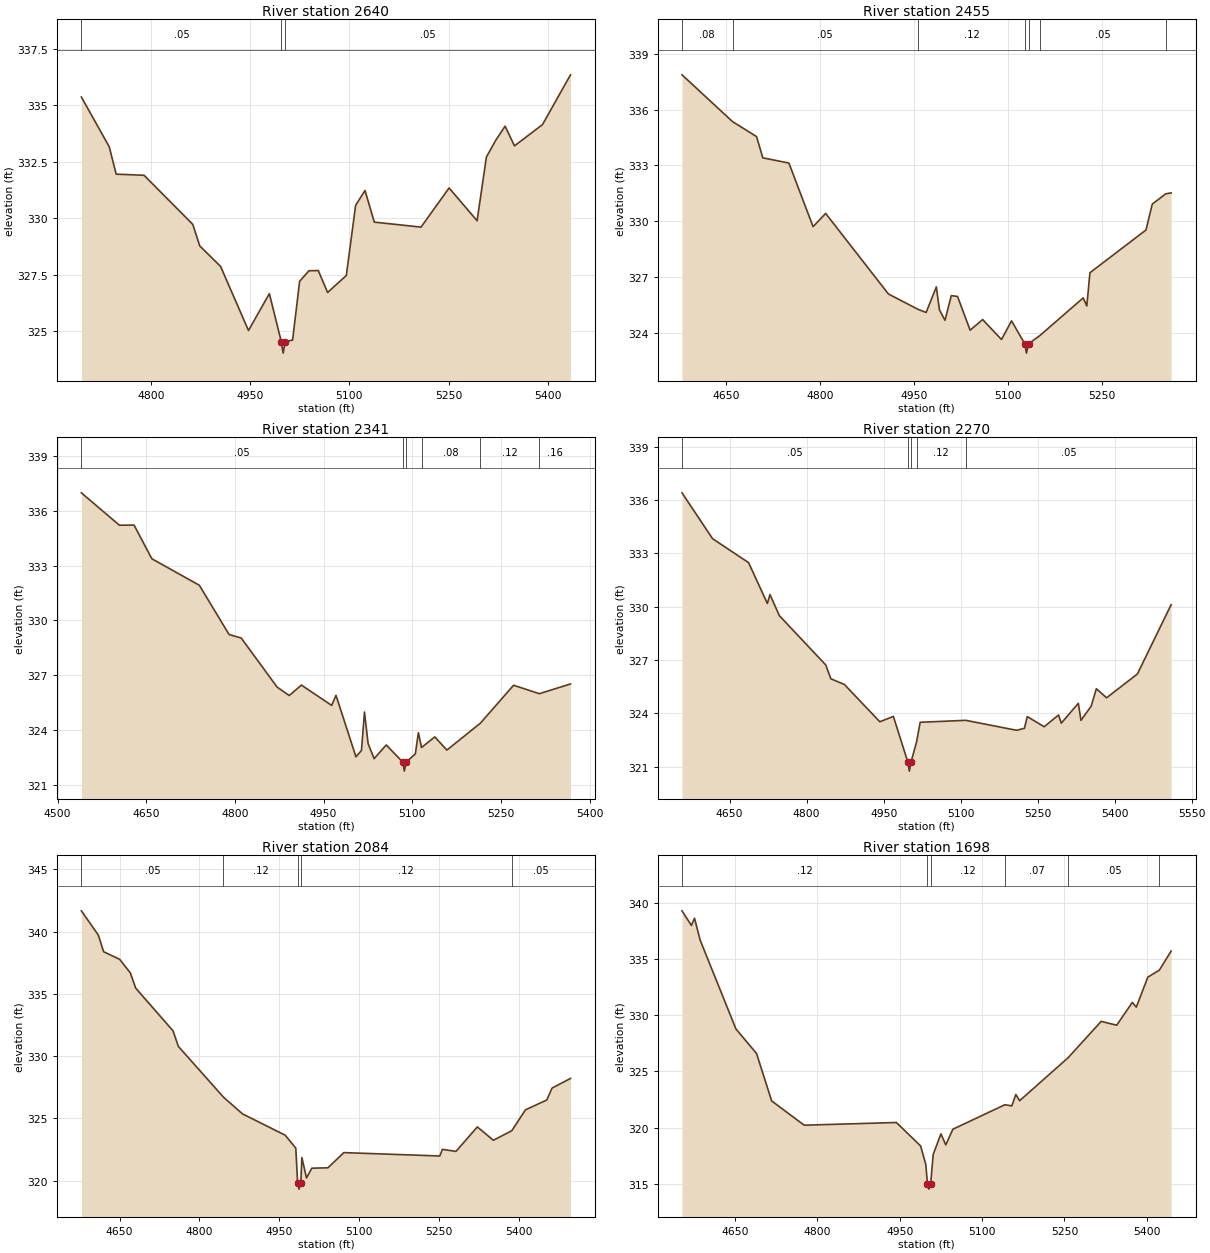
Type RM Length L Ch R = 1,2640,185,185,185
BEGIN DESCRIPTION:
UNT 03296 IN LACR 5.0
END DESCRIPTION:
XS GIS Cut Line= 3
      3712949.62     10658410.21      3712849.61     10658110.19
      3712549.62     10657810.20
#Sta/Elev= 30
  4694.2  335.36  4736.4  333.16  4746.9  331.95  4789.1  331.90  4862.9  329.73
  4873.4  328.78  4905.0  327.87  4947.2  325.04  4978.8  326.67  4996.9  324.54
  4999.7  324.04  5002.9  324.54  5014.0  324.62  5024.6  327.21  5038.7  327.68
  5052.9  327.69  5067.0  326.72  5095.3  327.47  5109.4  330.57  5123.6  331.23
  5137.7  329.83  5208.4  329.61  5250.9  331.34  5293.3  329.89  5307.4  332.71
  5321.6  333.45  5335.7  334.07  5349.9  333.20  5392.3  334.14  5434.7  336.34
#Mann=3,-1,0
  4694.2    0.05       0  4996.9    0.03       0  5002.9    0.05       0
Bank Sta=4996.9,5002.9
Exp/Cntr=0.3,0.1

Type RM Length L Ch R = 1,2455,114,114,114
BEGIN DESCRIPTION:
Mapping XS 435c7385
END DESCRIPTION:
XS GIS Cut Line= 2
      3713048.56     10658508.85      3712983.45     10657730.17
#Sta/Elev= 30
  4579.0  337.86  4659.8  335.35  4698.1  334.55  4708.1  333.41  4749.8  333.13
  4788.4  329.72  4808.5  330.43  4908.8  326.11  4956.0  325.29  4969.0  325.12
  4985.3  326.49  4990.3  325.26  4999.1  324.70  5009.2  326.02  5019.2  325.98
  5039.3  324.17  5059.3  324.74  5089.4  323.67  5105.5  324.67  5126.6  323.44
  5129.3  322.94  5132.6  323.44  5150.3  323.87  5219.9  325.90  5225.7  325.47
  5230.7  327.25  5320.2  329.54  5330.3  330.93  5351.8  331.48  5360.4  331.53
#Mann=7,-1,0
  4579.0    0.08       0  4659.8    0.05       0  4956.0    0.12       0
  5126.6    0.07       0  5132.6    0.12       0  5150.3    0.05       0
  5351.8    0.16       0
Bank Sta=5126.6,5132.6
Exp/Cntr=0.3,0.1

Type RM Length L Ch R = 1,2341,71,71,71
BEGIN DESCRIPTION:
Mapping XS 271434ce
END DESCRIPTION:
XS GIS Cut Line= 3
      3713111.06     10658508.81      3713082.41     10658222.36
      3713202.21     10657696.31
#Sta/Elev= 30
  4540.3  336.97  4604.7  335.20  4629.4  335.21  4659.5  333.37  4739.9  331.92
  4790.2  329.23  4810.7  329.04  4871.4  326.36  4891.9  325.90  4912.5  326.47
  4963.7  325.36  4971.0  325.91  5004.8  322.55  5014.1  322.90  5019.2  325.00
  5025.3  323.28  5035.5  322.45  5056.0  323.20  5083.8  322.27  5086.6  321.77
  5089.8  322.27  5105.2  322.71  5110.4  323.87  5115.7  323.06  5138.1  323.64
  5158.6  322.92  5215.3  324.39  5271.4  326.46  5315.0  326.00  5367.7  326.53
#Mann=6,-1,0
  4540.3    0.05       0  5083.8    0.04       0  5089.8    0.05       0
  5115.7    0.08       0  5215.3    0.12       0  5315.0    0.16       0
Bank Sta=5083.8,5089.8
Exp/Cntr=0.3,0.1

Type RM Length L Ch R = 1,2270,186,186,186
BEGIN DESCRIPTION:
UNT 03296 IN LACR 4.0
END DESCRIPTION:
XS GIS Cut Line= 4
      3713195.84     10658489.57      3713170.95     10658118.20
      3713288.14     10657722.36      3713293.04     10657554.56
#Sta/Elev= 30
  4557.1  336.41  4616.6  333.83  4686.8  332.48  4723.4  330.18  4728.5  330.68
  4746.9  329.49  4837.1  326.72  4847.1  325.94  4873.4  325.62  4942.5  323.52
  4968.9  323.82  4997.2  321.24  5000.0  320.74  5003.2  321.24  5014.3  322.41
  5021.1  323.49  5109.9  323.60  5208.8  323.04  5224.2  323.15  5229.7  323.81
  5262.7  323.24  5290.7  323.90  5296.0  323.44  5329.2  324.56  5334.4  323.60
  5354.3  324.40  5364.3  325.38  5384.3  324.87  5444.3  326.21  5510.0  330.11
#Mann=5,-1,0
  4557.1    0.05       0  4997.2    0.04       0  5003.2    0.05       0
  5014.3    0.12       0  5109.9    0.05       0
Bank Sta=4997.2,5003.2
Exp/Cntr=0.3,0.1

Type RM Length L Ch R = 1,2084,386,386,386
BEGIN DESCRIPTION:
Mapping XS 55f4e87d
END DESCRIPTION:
XS GIS Cut Line= 2
      3713405.33     10658461.91      3713336.58     10657545.68
#Sta/Elev= 30
  4578.3  341.66  4610.1  339.72  4620.1  338.38  4650.2  337.77  4670.3  336.68
  4680.3  335.46  4750.5  332.03  4760.5  330.78  4845.0  326.72  4880.9  325.37
  4961.1  323.66  4981.1  322.62  4984.5  319.83  4987.2  319.33  4990.5  319.83
  4992.5  321.86  5001.2  320.23  5011.2  321.01  5041.3  321.04  5071.4  322.26
  5251.5  321.99  5256.5  322.52  5282.0  322.36  5322.1  324.32  5352.2  323.25
  5386.9  324.02  5412.4  325.69  5452.5  326.48  5462.5  327.44  5497.1  328.21
#Mann=5,-1,0
  4578.3    0.05       0  4845.0    0.12       0  4984.5    0.07       0
  4990.5    0.12       0  5386.9    0.05       0
Bank Sta=4984.5,4990.5
Exp/Cntr=0.3,0.1

Type RM Length L Ch R = 1,1698,460,460,460
BEGIN DESCRIPTION:
UNT 03296 IN LACR 3.0
END DESCRIPTION:
XS GIS Cut Line= 3
      3713793.35     10658149.44      3713548.56     10657711.95
      3713283.74     10657426.35
#Sta/Elev= 30
  4553.6  339.30  4570.7  338.00  4576.4  338.64  4586.7  336.69  4651.8  328.79
  4689.4  326.60  4716.9  322.38  4776.2  320.22  4944.1  320.46  4988.2  318.37
  4997.7  316.72  5000.5  315.03  5003.2  314.53  5006.5  315.03  5011.1  317.62
  5025.2  319.45  5034.0  318.47  5046.9  319.86  5141.6  322.04  5154.3  321.94
  5161.6  322.95  5168.5  322.40  5256.9  326.23  5317.0  329.46  5345.3  329.12
  5373.7  331.15  5381.0  330.73  5402.0  333.40  5423.0  334.02  5444.4  335.72
#Mann=6,-1,0
  4553.6    0.12       0  5000.5    0.07       0  5006.5    0.12       0
  5141.6    0.07       0  5256.9    0.05       0  5423.0    0.16       0
Bank Sta=5000.5,5006.5
Exp/Cntr=0.3,0.1

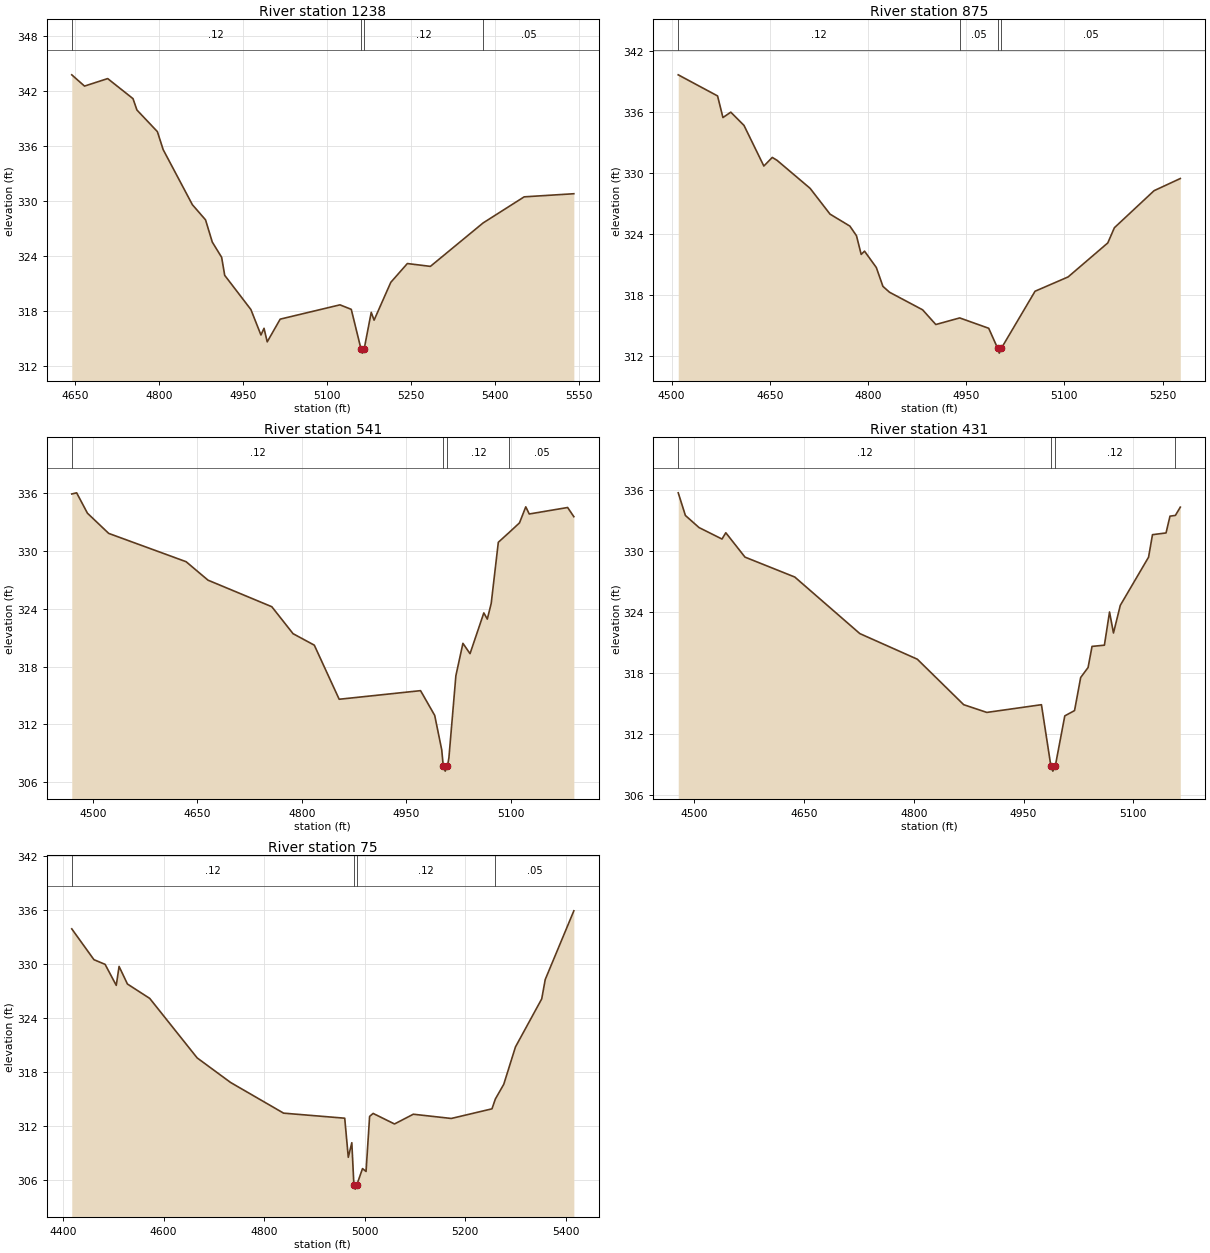
Type RM Length L Ch R = 1,1238,363,363,363
BEGIN DESCRIPTION:
UNT 03296 IN LACR 2.0
END DESCRIPTION:
XS GIS Cut Line= 3
      3714101.78     10658080.58      3713914.28     10657650.01
      3713851.78     10657226.42
#Sta/Elev= 30
  4643.8  343.75  4666.6  342.52  4708.0  343.34  4753.3  341.15  4760.3  339.91
  4796.9  337.55  4807.2  335.59  4859.5  329.57  4883.0  327.92  4895.1  325.49
  4911.8  323.83  4917.3  321.86  4964.1  318.13  4982.1  315.35  4987.6  316.08
  4993.3  314.60  5016.5  317.08  5123.4  318.64  5143.6  318.15  5160.8  313.87
  5163.5  313.37  5166.8  313.87  5179.3  317.82  5184.4  316.97  5214.3  321.10
  5243.9  323.15  5285.1  322.84  5379.3  327.58  5452.8  330.43  5541.6  330.77
#Mann=4,-1,0
  4643.8    0.12       0  5160.8    0.07       0  5166.8    0.12       0
  5379.3    0.05       0
Bank Sta=5160.8,5166.8
Exp/Cntr=0.3,0.1

Type RM Length L Ch R = 1,875,334,334,334
BEGIN DESCRIPTION:
Mapping XS 0c5e364b
END DESCRIPTION:
XS GIS Cut Line= 2
      3714224.79     10657989.67      3714115.41     10657230.51
#Sta/Elev= 30
  4510.2  339.70  4570.3  337.62  4578.5  335.49  4590.5  336.02  4610.7  334.71
  4641.0  330.71  4653.9  331.56  4661.2  331.27  4711.7  328.51  4742.1  325.97
  4772.4  324.79  4782.5  323.84  4789.7  322.00  4794.8  322.32  4812.8  320.71
  4822.9  318.85  4833.0  318.27  4883.5  316.54  4903.7  315.09  4940.2  315.74
  4984.5  314.72  4998.0  312.77  5000.7  312.27  5004.0  312.77  5055.3  318.37
  5105.8  319.78  5166.4  323.13  5176.5  324.63  5237.1  328.28  5277.2  329.48
#Mann=4,-1,0
  4510.2    0.12       0  4940.2    0.05       0  4998.0    0.03       0
  5004.0    0.05       0
Bank Sta=4998,5004
Exp/Cntr=0.3,0.1

Type RM Length L Ch R = 1,541,110,110,110
BEGIN DESCRIPTION:
Mapping XS 6d5c1ba8
END DESCRIPTION:
XS GIS Cut Line= 3
      3714283.37     10657992.29      3714362.81     10657571.67
      3714313.66     10657283.28
#Sta/Elev= 30
  4469.8  335.86  4476.8  335.98  4492.3  333.87  4522.8  331.78  4633.9  328.85
  4665.3  326.94  4756.9  324.19  4787.4  321.40  4817.9  320.21  4853.6  314.61
  4970.4  315.50  4990.7  312.94  5000.8  309.37  5003.0  307.67  5005.8  307.17
  5009.0  307.67  5011.1  308.56  5021.1  317.05  5031.2  320.40  5041.4  319.33
  5061.2  323.55  5066.2  322.91  5071.8  324.53  5082.0  330.86  5097.9  331.90
  5112.4  332.87  5121.4  334.53  5126.4  333.79  5181.5  334.46  5190.4  333.51
#Mann=4,-1,0
  4469.8    0.12       0  5003.0    0.07       0  5009.0    0.12       0
  5097.9    0.05       0
Bank Sta=5003,5009
Exp/Cntr=0.3,0.1

Type RM Length L Ch R = 1,431,356,356,356
BEGIN DESCRIPTION:
Mapping XS a1aebaca
END DESCRIPTION:
XS GIS Cut Line= 3
      3714304.60     10657989.44      3714462.59     10657524.12
      3714388.28     10657344.39
#Sta/Elev= 30
  4478.3  335.72  4488.1  333.49  4506.7  332.30  4538.1  331.17  4543.3  331.79
  4569.5  329.39  4637.5  327.43  4726.4  321.86  4804.9  319.34  4868.3  314.86
  4899.9  314.10  4974.5  314.86  4987.4  308.82  4990.1  308.32  4993.4  308.82
  5006.4  313.76  5019.7  314.28  5028.1  317.54  5038.2  318.52  5043.6  320.60
  5060.5  320.72  5067.5  323.99  5072.9  321.92  5082.2  324.64  5120.8  329.38
  5126.2  331.60  5144.7  331.77  5150.1  333.42  5157.5  333.50  5164.2  334.31
#Mann=4,-1,0
  4478.3    0.12       0  4987.4    0.07       0  4993.4    0.12       0
  5157.5    0.05       0
Bank Sta=4987.4,4993.4
Exp/Cntr=0.3,0.1

Type RM Length L Ch R = 1,75,0,0,0
BEGIN DESCRIPTION:
UNT 03296 IN LACR 1.0
END DESCRIPTION:
XS GIS Cut Line= 4
      3714342.79     10657991.16      3714544.19     10657598.78
      3714693.50     10657447.74      3714377.51     10657308.84
#Sta/Elev= 30
  4417.5  333.91  4461.6  330.49  4483.8  329.97  4506.0  327.64  4511.6  329.74
  4528.2  327.79  4572.6  326.19  4666.9  319.59  4733.5  316.86  4838.8  313.46
  4960.4  312.90  4967.5  308.56  4974.5  310.18  4978.6  305.53  4981.4  305.03
  4984.6  305.53  4995.8  307.31  5002.8  306.99  5009.9  313.10  5016.9  313.43
  5059.4  312.26  5096.8  313.34  5172.3  312.87  5253.3  313.94  5260.0  315.03
  5276.7  316.66  5300.0  320.81  5352.2  326.14  5359.2  328.29  5416.1  335.91
#Mann=4,-1,0
  4417.5    0.12       0  4978.6    0.07       0  4984.6    0.12       0
  5260.0    0.05       0
Bank Sta=4978.6,4984.6
Exp/Cntr=0.3,0.1

Chan Stop Cuts=-1