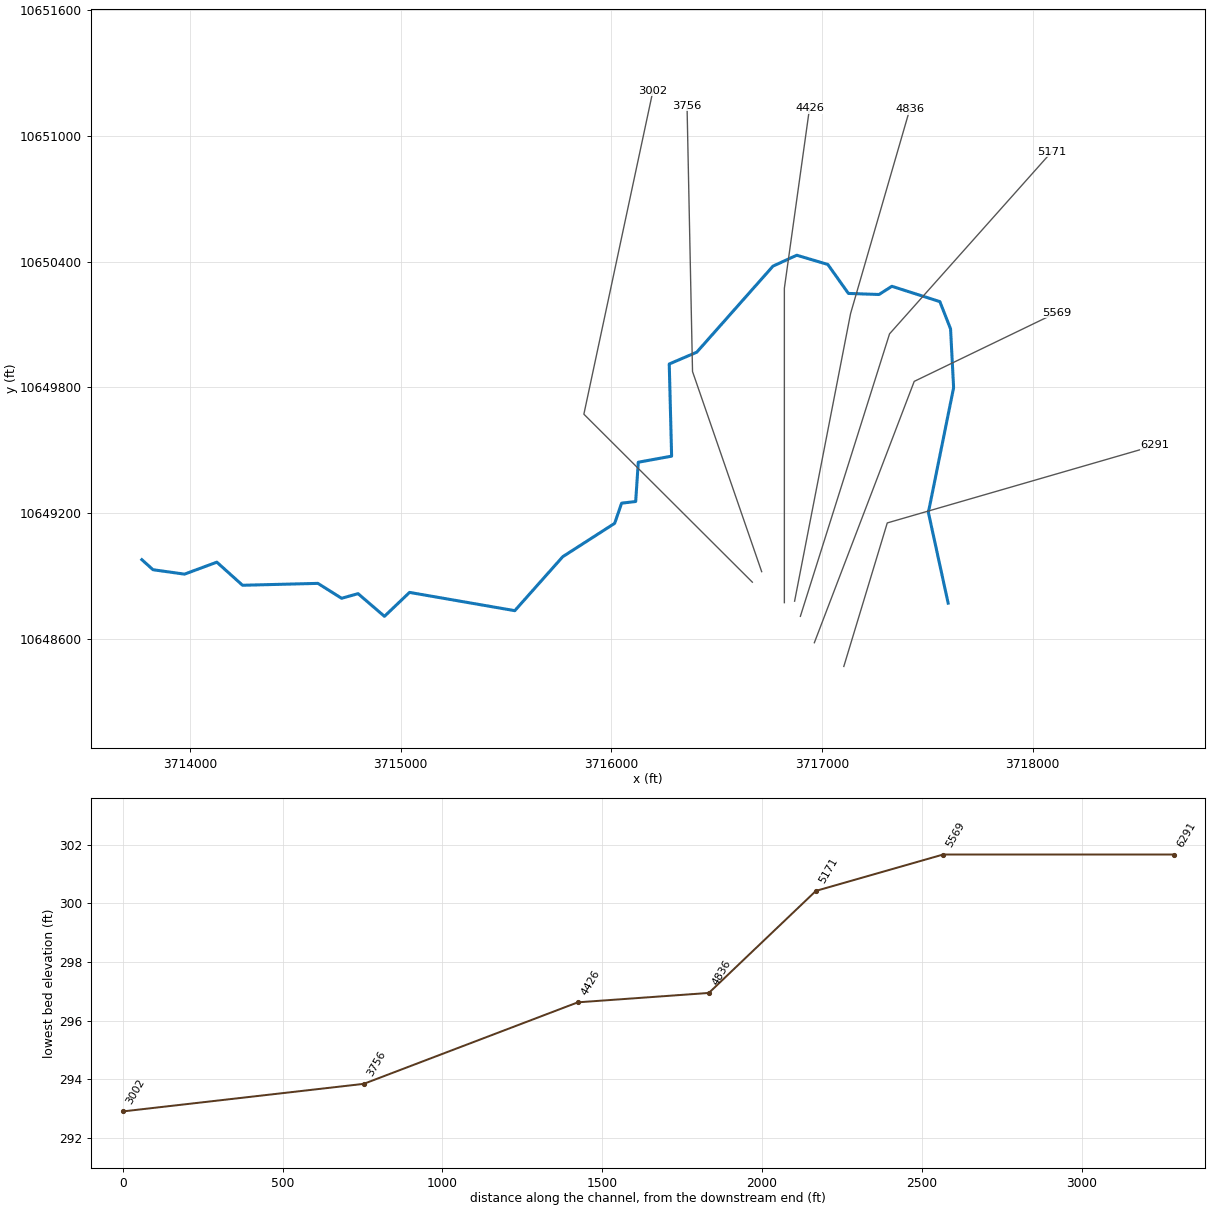
--- UNT 03303 IN LACR.prj (project) ---

Proj Title=UNT 03303 IN LACR Base Level Engineering
Current Plan=p01
Default Exp/Contr=0.3,0.1
English Units
Geom File=g01
Flow File=f01
Plan File=p01
Y Axis Title=Elevation
X Axis Title(PF)=Main Channel Distance
X Axis Title(XS)=Station
BEGIN DESCRIPTION:
UNT 03303 IN LACR
END DESCRIPTION:
DSS Export Rating Curves= 0
DSS Export Rating Curve Sorted= 0
DSS Export Volume Flow Curves= 0
DXF OffsetX= 0
DXF OffsetY= 0
DXF ScaleX= 1
DXF ScaleY= 10

--- UNT 03303 IN LACR.p01 (plan) ---

Plan Title=Multiple Run
Short Identifier=Multiple
Geom File=g01
Flow File=f01
Subcritical Flow
K Sum by GR= 0
Std Step Tol= 0.01
Critical Tol= 0.01
Num of Std Step Trials= 20
Max Error Tol= 0.3
Flow Tol Ratio= 0.001
Split Flow NTrial= 30
Split Flow Tol= 0.02
Split Flow Ratio= 0.02
Log Output Level= 0
Friction Slope Method= 1
Unsteady Friction Slope Method= 2
Unsteady Bridges Friction Slope Method= 1
Parabolic Critical Depth
Global Vel Dist=  1 , 1 , 1
Global Log Level= 0
CheckData=True
Encroach Param= -1, 0, 0, 0
BEGIN DESCRIPTION:
Multiple Run
END DESCRIPTION:

--- UNT 03303 IN LACR.f01 (steady flow) ---

Flow Title=Multiple
Program Version=4.10
Number of Profiles= 7
Profile Names=10-year,25-year,50-year,1pct_min,100-year,1pct_plu,500-year
River Rch & RM=UNT 03303 IN LAC,Reach-1         ,6291
     330     426     501     434     587     794     807
Boundary for River Rch & Prof#=UNT 03303 IN LAC,Reach-1         , 1
Up Type= 0
Dn Type= 3
Dn Slope=0.001
Boundary for River Rch & Prof#=UNT 03303 IN LAC,Reach-1         , 2
Up Type= 0
Dn Type= 3
Dn Slope=0.001
Boundary for River Rch & Prof#=UNT 03303 IN LAC,Reach-1         , 3
Up Type= 0
Dn Type= 3
Dn Slope=0.001
Boundary for River Rch & Prof#=UNT 03303 IN LAC,Reach-1         , 4
Up Type= 0
Dn Type= 3
Dn Slope=0.001
Boundary for River Rch & Prof#=UNT 03303 IN LAC,Reach-1         , 5
Up Type= 0
Dn Type= 3
Dn Slope=0.001
Boundary for River Rch & Prof#=UNT 03303 IN LAC,Reach-1         , 6
Up Type= 0
Dn Type= 3
Dn Slope=0.001
Boundary for River Rch & Prof#=UNT 03303 IN LAC,Reach-1         , 7
Up Type= 0
Dn Type= 3
Dn Slope=0.001
DSS Import GetInterval= 0
DSS Import GetPeak= 0
DSS Import FillOption= 0

--- UNT 03303 IN LACR.g01 (geometry) ---

Geom Title=Existing Conditions
Program Version=4.10

River Reach=UNT 03303 IN LAC,Reach-1
Reach XY= 30
      3717598.75       10648773.        3717505.       10649205.
      3717624.75       10649799.      3717610.25       10650079.
       3717559.5       10650209.      3717331.75       10650282.
      3717270.75       10650243.       3717125.5       10650248.
      3717027.75       10650386.      3716880.25       10650430.
       3716767.5       10650378.      3716405.75       10649968.
      3716275.25       10649912.       3716286.5       10649473.
      3716128.25       10649444.        3716116.       10649257.
      3716049.25       10649249.      3716016.25       10649153.
      3715769.75       10648994.      3715542.25       10648737.
      3715042.75       10648824.      3714923.75       10648710.
       3714798.5       10648818.      3714720.25       10648796.
        3714608.       10648867.      3714250.25       10648858.
      3714128.25       10648968.      3713974.75       10648911.
       3713825.5       10648932.      3713772.25       10648980.

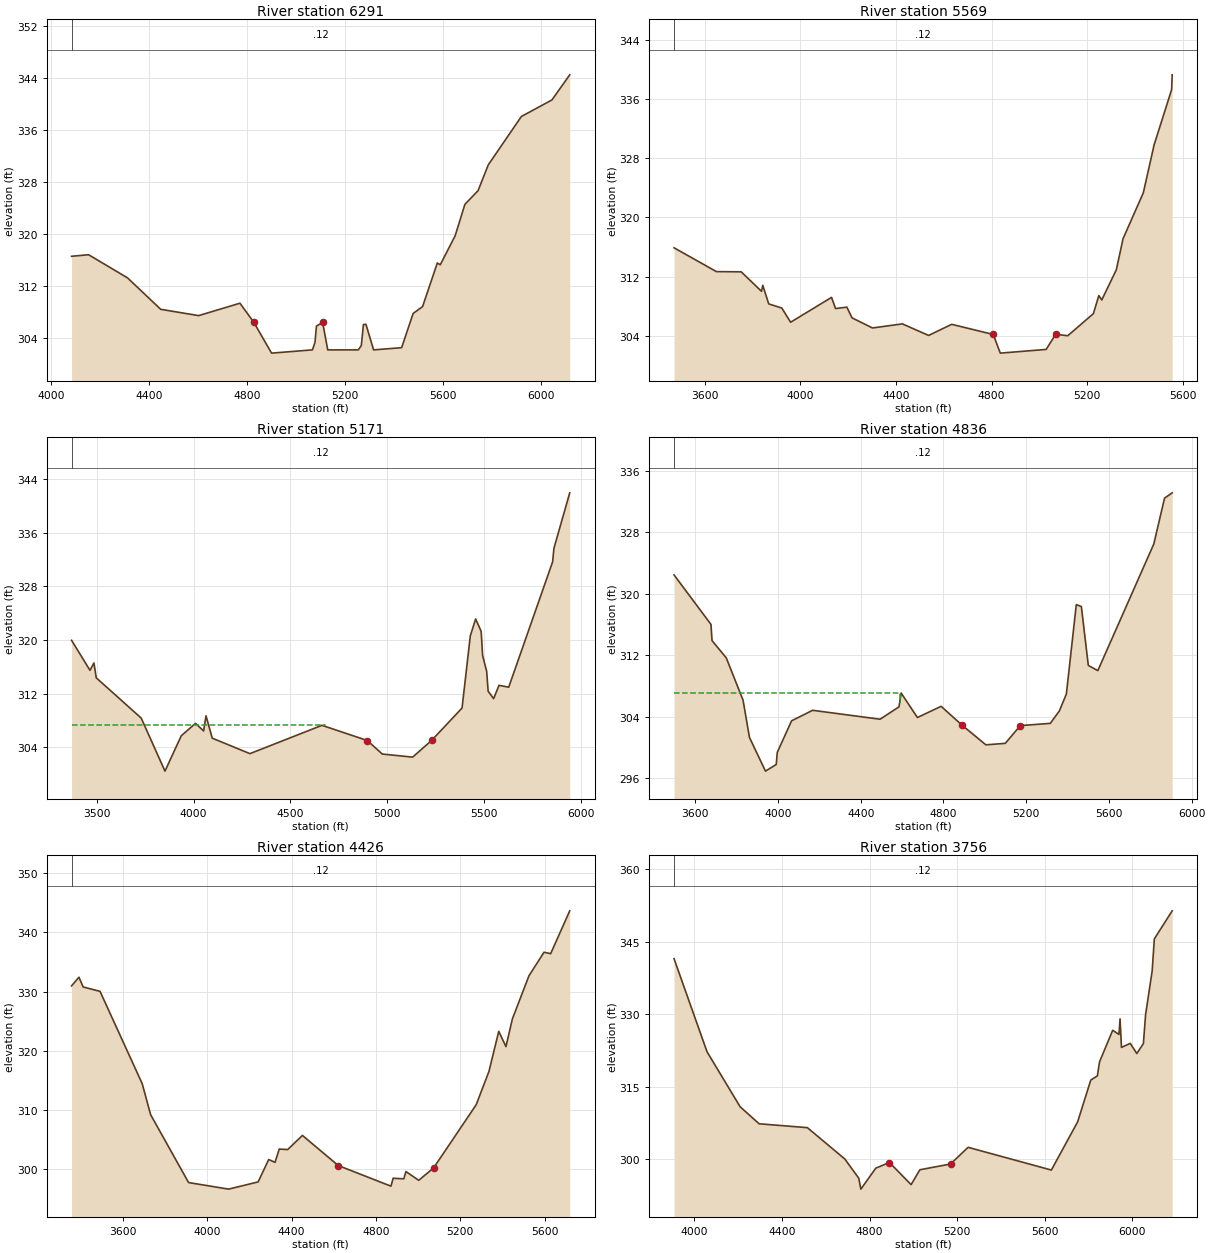
Type RM Length L Ch R = 1 ,6291    ,722,722,722
BEGIN DESCRIPTION:
UNT 03303 IN LACR 3.0
END DESCRIPTION:
XS GIS Cut Line= 3
      3717103.69     10648471.32      3717309.84     10649154.88
      3718579.36      10649523.8
#Sta/Elev= 30
  4082.4  316.57    4152  316.81    4311  313.25  4446.8  308.41  4601.7  307.44
  4770.6  309.35  4827.4   306.4  4899.8  301.67  5066.9  302.17  5077.3  303.34
  5083.3  305.84  5108.5  306.39  5129.4  302.17  5254.3  302.17  5266.6  302.83
  5275.2  306.07  5285.6   306.1  5316.8  302.17  5431.4  302.51  5478.3  307.77
    5517  308.83  5577.1  315.53  5589.3  315.27    5650  319.72  5689.9  324.56
  5743.8  326.67  5785.4  330.63  5920.8  338.08  6045.8  340.63  6118.4  344.49
#Mann= 1 ,-1 , 0
  4082.4     .12       0
Bank Sta=4827.4,5108.5
XS Rating Curve= 0 ,0
Exp/Cntr=0.3,0.1

Type RM Length L Ch R = 1 ,5569    ,398,398,398
BEGIN DESCRIPTION:
Mapping XS 88e77194
END DESCRIPTION:
XS GIS Cut Line= 3
      3716963.86     10648584.33      3717437.81     10649829.11
      3718114.75     10650157.17
#Sta/Elev= 30
  3471.4   315.9  3648.9  312.68  3752.5  312.65  3837.5  310.02  3842.8  310.83
  3867.6  308.32  3922.4  307.76  3959.2  305.84  4130.4   309.2  4147.2  307.69
  4194.6  307.88    4216  306.44  4301.6  305.07  4426.8  305.62  4536.5  304.06
  4633.3  305.56  4807.1  304.19  4836.4  301.67  5028.4  302.17    5068  304.21
  5118.7  304.02  5226.1  307.01  5248.6  309.44    5261  308.85  5321.9  312.93
  5350.1  317.13  5434.8  323.32    5480   329.8  5553.3  337.26  5555.6  339.26
#Mann= 1 ,-1 , 0
  3471.4     .12       0
Bank Sta=4807.1,5068
XS Rating Curve= 0 ,0
Exp/Cntr=0.3,0.1

Type RM Length L Ch R = 1 ,5171    ,335,335,335
BEGIN DESCRIPTION:
Mapping XS c4fa8d4f
END DESCRIPTION:
XS GIS Cut Line= 3
      3716897.52     10648710.03      3717320.69     10650055.48
      3718091.12     10650923.57
#Sta/Elev= 30
  3370.1  319.96  3465.1  315.48  3485.6  316.58  3497.5  314.36  3729.5  308.35
  3852.2  300.43  3936.3  305.71  4009.7  307.56  4051.7  306.43  4063.9  308.69
  4096.2  305.35  4290.6  303.04  4662.6  307.27  4896.2     305    4974  302.98
  5130.4  302.52    5229  305.03  5385.4  309.85  5428.1  320.64  5455.7  323.15
  5484.1   321.3  5491.6  317.69  5512.5  315.33  5520.1  312.36  5548.5  311.25
  5576.1  313.24  5626.3  312.96  5852.9  331.68  5859.6   333.7  5941.2  341.98
#Mann= 1 ,-1 , 0
  3370.1     .12       0
#XS Ineff= 2 , 0
         4677.42  307.34
Permanent Ineff=
       F       F
Bank Sta=4896.2,5229
XS Rating Curve= 0 ,0
Exp/Cntr=0.3,0.1

Type RM Length L Ch R = 1 ,4836    ,410,410,410
BEGIN DESCRIPTION:
Mapping XS 69b86451
END DESCRIPTION:
XS GIS Cut Line= 3
       3716870.1     10648782.21      3717135.73     10650152.02
      3717416.87     10651125.61
#Sta/Elev= 30
  3497.2  322.47  3675.9  316.03    3681  313.92  3749.8  311.68  3831.1  306.17
  3861.9  301.34  3939.4  296.95  3991.4  297.81  3996.5  299.39  4065.6  303.49
  4167.4  304.86  4493.4   303.7  4585.1  305.31  4595.3  307.11  4674.1  303.92
  4788.8  305.38  4889.6  302.93  5005.1  300.37  5098.8  300.56  5171.7  302.87
  5316.6  303.16  5360.7  304.79  5394.3  306.98  5442.3   318.6  5466.8  318.35
  5500.4   310.7  5546.4  310.02    5817  326.48    5869  332.45  5905.9  333.14
#Mann= 1 ,-1 , 0
  3497.2     .12       0
#XS Ineff= 2 , 0
         4587.81  307.17
Permanent Ineff=
       F       F
Bank Sta=4889.6,5171.7
XS Rating Curve= 0 ,0
Exp/Cntr=0.3,0.1

Type RM Length L Ch R = 1 ,4426    ,670,670,670
BEGIN DESCRIPTION:
UNT 03303 IN LACR 2.0
END DESCRIPTION:
XS GIS Cut Line= 3
      3716821.56     10648775.15      3716821.56      10650272.5
      3716940.91     10651129.68
#Sta/Elev= 30
  3356.7  330.96  3391.7  332.42  3411.7  330.77  3491.7  330.03  3691.7  314.44
  3731.7   309.2  3911.7  297.74  4101.5  296.63  4241.7  297.85  4291.7  301.63
  4321.7  301.15  4341.7   303.4  4381.7  303.31  4451.7   305.7  4621.7  300.61
  4871.5  297.13    4882  298.47  4932.5  298.37  4942.6   299.6  5003.2  298.12
  5073.8  300.21  5275.8  310.88  5336.3   316.5  5382.8  323.27  5417.1   320.7
  5447.4  325.37    5526  332.65  5597.5  336.63  5629.1   336.4  5719.5  343.63
#Mann= 1 ,-1 , 0
  3356.7     .12       0
#XS Ineff= 2 , 0
          4455.2  305.33
Permanent Ineff=
       F       F
Bank Sta=4621.7,5073.8
XS Rating Curve= 0 ,0
Exp/Cntr=0.3,0.1

Type RM Length L Ch R = 1 ,3756    ,754,754,754
BEGIN DESCRIPTION:
Mapping XS 6d09fd34
END DESCRIPTION:
XS GIS Cut Line= 3
      3716713.85     10648922.87      3716385.73     10649875.98
      3716359.68     10651141.61
#Sta/Elev= 30
  3907.7  341.47  4058.6  322.21  4209.4  310.87  4296.2  307.35  4516.4  306.55
  4687.5  300.07  4750.9  296.11  4760.6  293.85  4828.6  298.18  4891.1  299.35
  4989.9  294.78  5029.9  297.85    5170  299.04    5250  302.49  5630.1  297.79
  5750.1  307.75  5810.1  316.39  5840.1  317.25  5850.1  320.16  5910.1  326.67
  5938.7  325.81  5943.7  329.03  5950.1  323.13  5990.1  323.97  6020.1  321.86
  6050.2  323.92  6060.2   329.9  6090.2  338.92  6100.2  345.56  6181.6  351.35
#Mann= 1 ,-1 , 0
  3907.7     .12       0
Bank Sta=4891.1,5170
XS Rating Curve= 0 ,0
Exp/Cntr=0.3,0.1

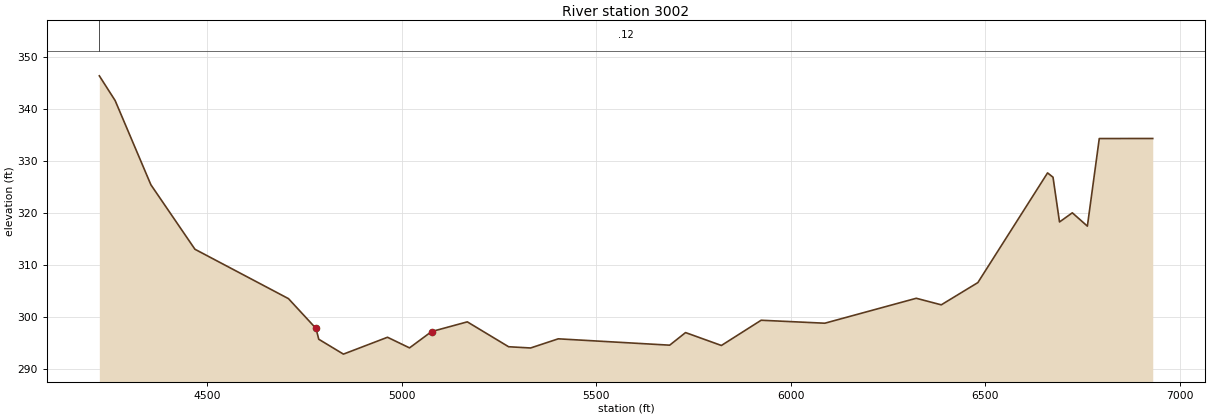
Type RM Length L Ch R = 1 ,3002    ,0,0,0
BEGIN DESCRIPTION:
UNT 03303 IN LACR 1.0
END DESCRIPTION:
XS GIS Cut Line= 3
      3716669.62     10648872.78       3715870.1     10649672.86
      3716198.23     10651214.54
#Sta/Elev= 30
  4222.8  346.38  4263.4  341.63  4355.3  325.45  4468.5  313.06  4708.9  303.57
  4779.6  297.85  4786.7  295.77  4850.1  292.91  4963.4  296.15    5020  294.11
  5076.6  297.24  5168.5  299.11  5274.6  294.33  5331.1  294.09  5402.3  295.85
  5688.6  294.63  5729.4  297.05  5821.5  294.57  5923.7  299.42  6087.3  298.85
  6322.4  303.64  6386.6  302.38  6480.6  306.65  6659.8  327.73  6673.8   326.9
  6690.5   318.3  6723.4  320.06  6762.1   317.5  6792.7  334.33  6930.1  334.34
#Mann= 1 ,-1 , 0
  4222.8     .12       0
Bank Sta=4779.6,5076.6
XS Rating Curve= 0 ,0
Exp/Cntr=0.3,0.1

Chan Stop Cuts=-1
Use User Specified Reach Order=0
Composite Channel Slope=5