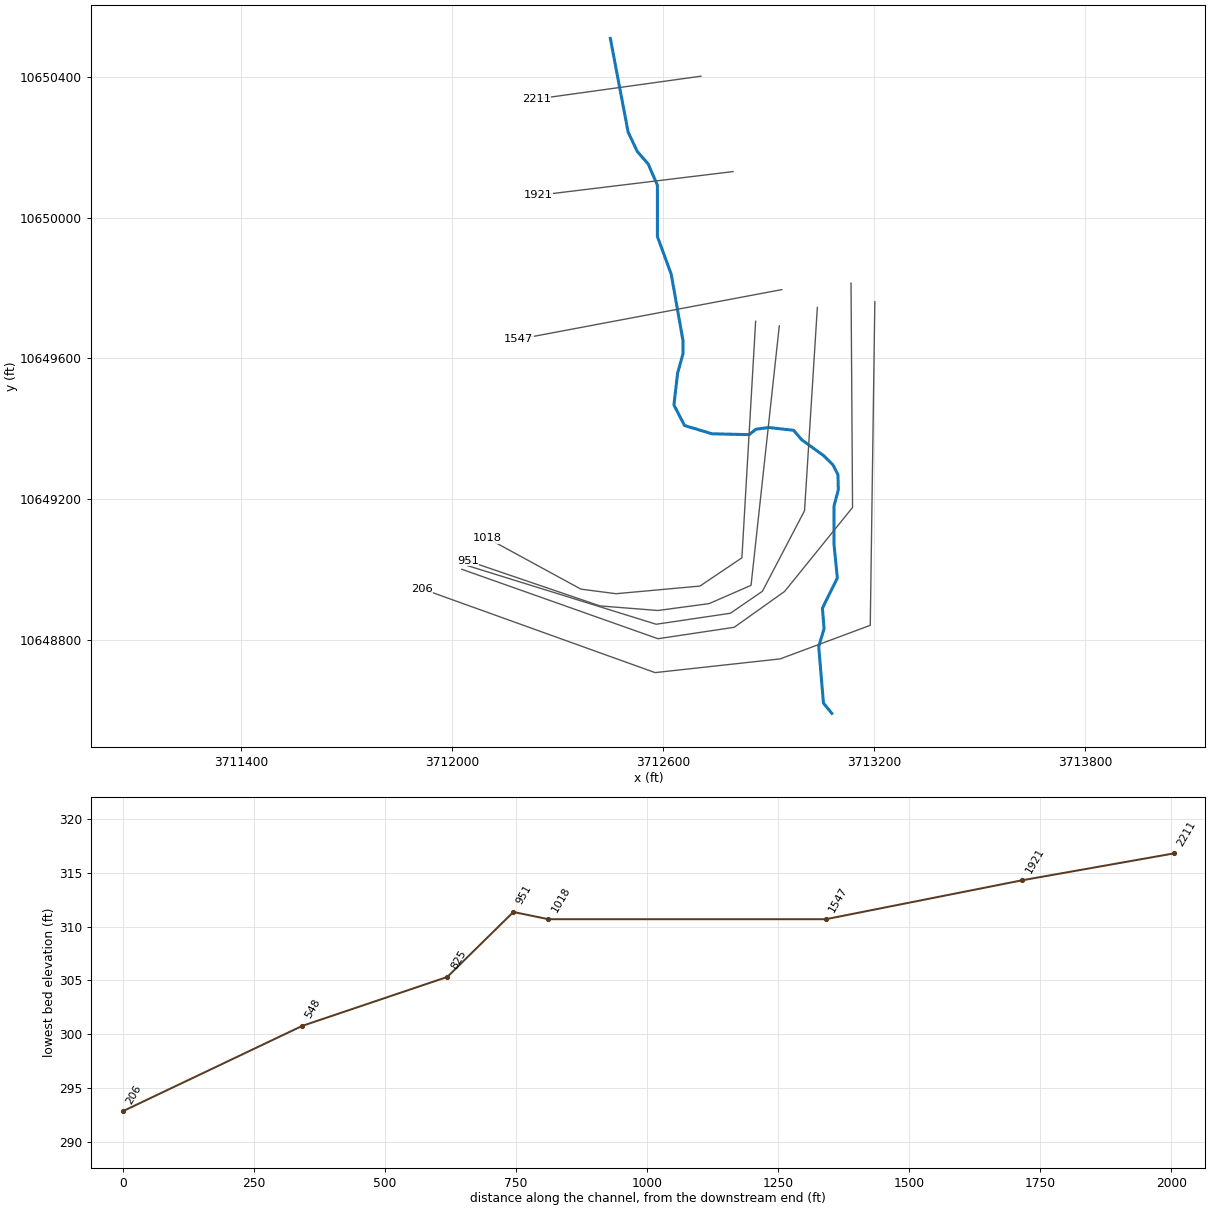
--- UNT 03305 IN LACR.prj (project) ---

Proj Title=UNT 03305 IN LACR Base Level Engineering
Current Plan=p01
Default Exp/Contr=0.3,0.1
English Units
Geom File=g01
Flow File=f01
Plan File=p01
Y Axis Title=Elevation
X Axis Title(PF)=Main Channel Distance
X Axis Title(XS)=Station
BEGIN DESCRIPTION:
UNT 03305 IN LACR
END DESCRIPTION:
DSS Export Rating Curves= 0
DSS Export Rating Curve Sorted= 0
DSS Export Volume Flow Curves= 0
DXF OffsetX= 0
DXF OffsetY= 0
DXF ScaleX= 1
DXF ScaleY= 10

--- UNT 03305 IN LACR.p01 (plan) ---

Plan Title=Multiple Run
Short Identifier=Multiple
Geom File=g01
Flow File=f01
Subcritical Flow
K Sum by GR= 0
Std Step Tol= 0.01
Critical Tol= 0.01
Num of Std Step Trials= 20
Max Error Tol= 0.3
Flow Tol Ratio= 0.001
Split Flow NTrial= 30
Split Flow Tol= 0.02
Split Flow Ratio= 0.02
Log Output Level= 0
Friction Slope Method= 1
Unsteady Friction Slope Method= 2
Unsteady Bridges Friction Slope Method= 1
Parabolic Critical Depth
Global Vel Dist=  1 , 1 , 1
Global Log Level= 0
CheckData=True
Encroach Param= -1, 0, 0, 0
BEGIN DESCRIPTION:
Multiple Run
END DESCRIPTION:

--- UNT 03305 IN LACR.f01 (steady flow) ---

Flow Title=Multiple
Program Version=4.10
Number of Profiles= 7
Profile Names=10-year,25-year,50-year,1pct_min,100-year,1pct_plu,500-year
River Rch & RM=UNT 03305 IN LAC,Reach-1         ,2211
     138     169     193     162     219     296     283
Boundary for River Rch & Prof#=UNT 03305 IN LAC,Reach-1         , 1
Up Type= 0
Dn Type= 3
Dn Slope=0.02
Boundary for River Rch & Prof#=UNT 03305 IN LAC,Reach-1         , 2
Up Type= 0
Dn Type= 3
Dn Slope=0.02
Boundary for River Rch & Prof#=UNT 03305 IN LAC,Reach-1         , 3
Up Type= 0
Dn Type= 3
Dn Slope=0.02
Boundary for River Rch & Prof#=UNT 03305 IN LAC,Reach-1         , 4
Up Type= 0
Dn Type= 3
Dn Slope=0.02
Boundary for River Rch & Prof#=UNT 03305 IN LAC,Reach-1         , 5
Up Type= 0
Dn Type= 3
Dn Slope=0.02
Boundary for River Rch & Prof#=UNT 03305 IN LAC,Reach-1         , 6
Up Type= 0
Dn Type= 3
Dn Slope=0.02
Boundary for River Rch & Prof#=UNT 03305 IN LAC,Reach-1         , 7
Up Type= 0
Dn Type= 3
Dn Slope=0.02
DSS Import GetInterval= 0
DSS Import GetPeak= 0
DSS Import FillOption= 0

--- UNT 03305 IN LACR.g01 (geometry) ---

Geom Title=Existing Conditions
Program Version=4.10

River Reach=UNT 03305 IN LAC,Reach-1
Reach XY= 30
      3712449.61     10650509.72      3712500.25       10650243.
      3712526.25       10650188.       3712557.5       10650152.
       3712583.5       10650092.       3712583.5       10649946.
      3712622.75       10649839.       3712656.5       10649649.
       3712656.5       10649613.        3712641.       10649558.
       3712630.5       10649467.      3712660.78     10649408.56
      3712738.91     10649385.12      3712844.15     10649382.62
       3712863.5       10649398.        3712900.       10649403.
        3712971.       10649395.        3712994.       10649368.
      3713056.25       10649323.       3713082.5       10649297.
        3713097.       10649269.        3713098.       10649226.
      3713085.75       10649180.      3713085.75       10649070.
      3713095.25       10648975.      3713052.75       10648889.
       3713057.5       10648831.      3713042.25       10648780.
      3713055.75       10648619.       3713079.5       10648590.

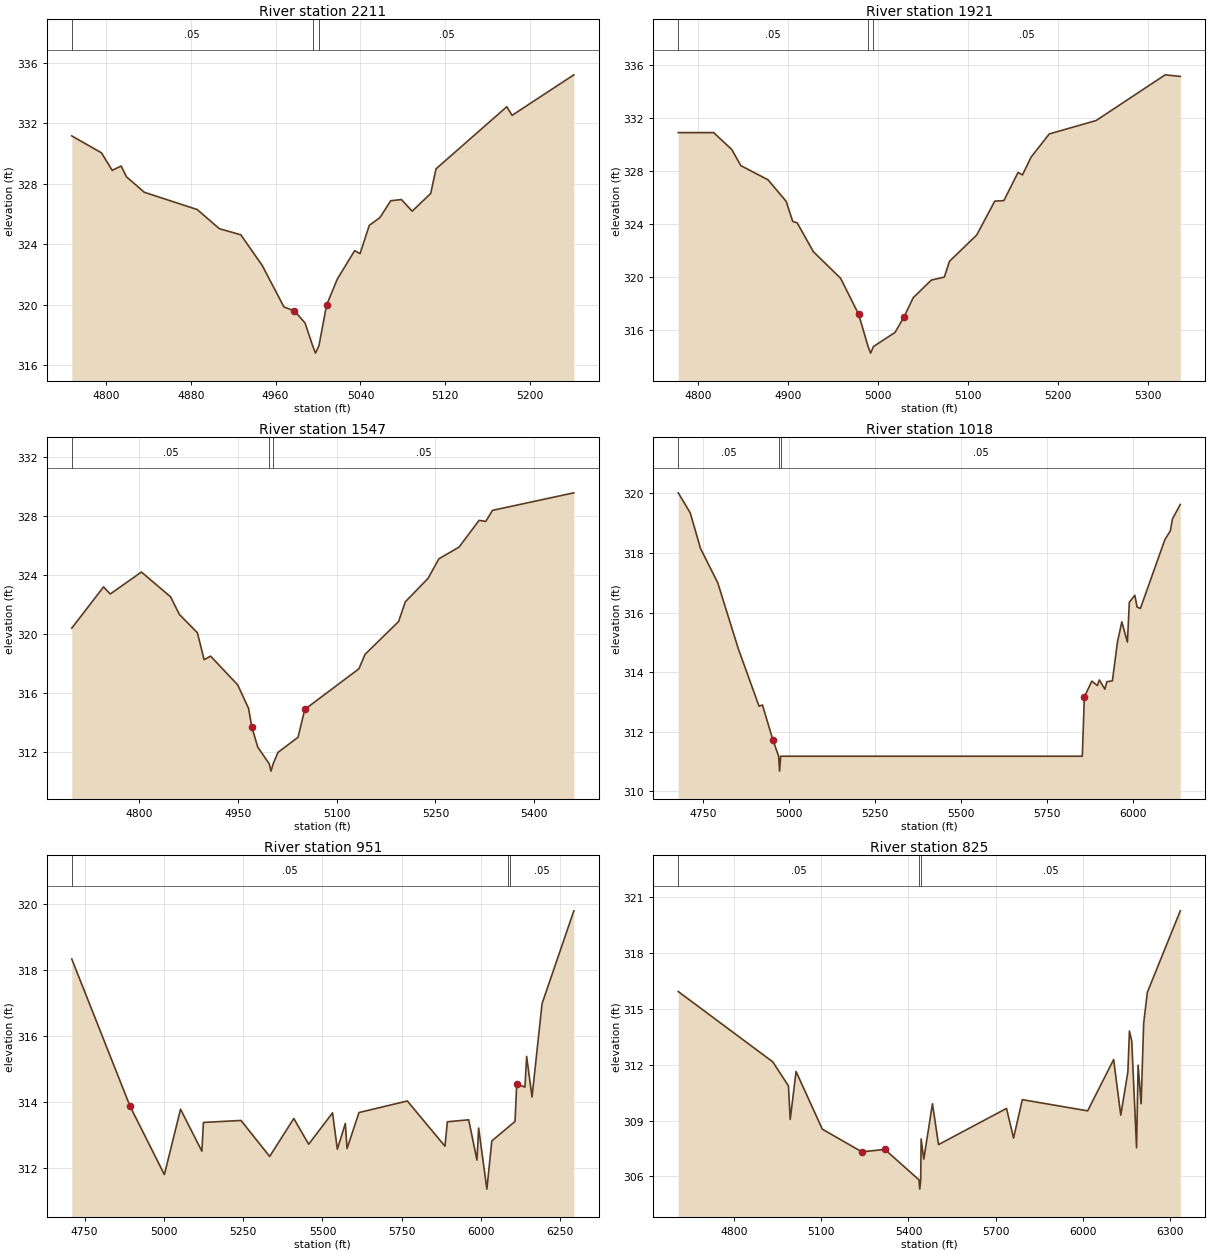
Type RM Length L Ch R = 1 ,2211    ,290,290,290
BEGIN DESCRIPTION:
UNT 03305 IN LACR 3.0
END DESCRIPTION:
XS GIS Cut Line= 2
      3712707.39     10650402.05      3712238.69     10650336.95
#Sta/Elev= 30
  4767.9  331.16  4795.9  330.04    4806  328.88  4814.4  329.17  4819.5  328.45
  4836.3  327.43  4886.1  326.29    4907  325.02  4927.2  324.62  4947.4  322.59
  4967.9  319.84  4977.7  319.59  4987.8  318.78  4994.9  317.29  4997.6  316.79
  5000.9  317.29    5008  319.95  5018.1  321.68  5034.5  323.57  5039.6  323.37
  5048.3  325.24  5058.4  325.76  5068.5  326.87  5078.6  326.95  5088.7  326.18
  5106.2  327.35  5111.2  328.98  5177.9  333.09  5182.9  332.52  5241.1   335.2
#Mann= 3 ,-1 , 0
  4767.9     .05       0  4994.9     .03       0  5000.9     .05       0
Bank Sta=4977.7,5008
XS Rating Curve= 0 ,0
Exp/Cntr=0.3,0.1

Type RM Length L Ch R = 1 ,1921    ,374,374,374
BEGIN DESCRIPTION:
UNT 03305 IN LACR 2.0
END DESCRIPTION:
XS GIS Cut Line= 2
      3712798.58     10650130.78      3712245.15     10650063.51
#Sta/Elev= 30
  4778.1  330.93  4817.4  330.93  4837.5  329.66  4847.6  328.44  4877.8  327.37
  4897.9  325.75  4905.2  324.23  4910.2  324.12  4928.2  321.94  4958.4  319.94
  4978.5  317.21  4988.9  314.79  4991.7  314.29  4994.9  314.79  5018.8  315.85
  5028.9  317.03    5039  318.47  5059.1   319.8  5073.6  320.03  5079.3  321.22
  5109.5   323.2  5129.6  325.76  5139.7   325.8  5155.4  327.92  5160.4  327.74
  5169.9  329.08  5190.1  330.83  5242.1  331.84  5318.8  335.29  5335.6  335.17
#Mann= 3 ,-1 , 0
  4778.1     .05       0  4988.9     .03       0  4994.9     .05       0
Bank Sta=4978.5,5028.9
XS Rating Curve= 0 ,0
Exp/Cntr=0.3,0.1

Type RM Length L Ch R = 1 ,1547    ,529,529,529
BEGIN DESCRIPTION:
Mapping XS 11479d19
END DESCRIPTION:
XS GIS Cut Line= 2
      3712936.96     10649795.06      3712188.33     10649654.01
#Sta/Elev= 30
  4698.3  320.39  4746.5  323.19  4756.7  322.71    4804   324.2  4848.2  322.52
  4861.6  321.32  4888.9  320.08  4899.1  318.25  4908.9  318.49    4950  316.54
  4966.5  314.95  4971.5  313.68  4980.5  312.31  4997.9  311.18  5000.6  310.68
  5003.9  311.18  5011.1  311.95  5041.6  312.98  5051.8  314.87    5134  317.63
  5143.3  318.61  5194.2  320.84  5204.4  322.18  5238.9  323.77  5255.3   325.1
  5285.8  325.89  5316.3  327.71  5326.5  327.64  5336.7  328.39  5460.1  329.58
#Mann= 3 ,-1 , 0
  4698.3     .05       0  4997.9     .03       0  5003.9     .05       0
Bank Sta=4971.5,5051.8
XS Rating Curve= 0 ,0
Exp/Cntr=0.3,0.1

Type RM Length L Ch R = 1 ,1018    ,67,67,67
BEGIN DESCRIPTION:
Mapping XS 9f9516a3
END DESCRIPTION:
XS GIS Cut Line= 6
      3712862.87     10649705.07      3712823.81     10649032.32
      3712704.45     10648952.03      3712465.73     10648930.33
      3712365.91     10648943.35      3712098.95     10649088.76
#Sta/Elev= 30
    4677  320.02  4711.9  319.35    4742  318.15  4792.1     317  4852.2  314.78
  4912.3  312.86  4922.3   312.9  4952.3  311.74  4969.4  311.18  4972.1  310.68
  4975.4  311.18  5853.7  311.18  5859.6  313.17  5881.5   313.7  5897.6  313.55
  5903.3  313.74  5919.4  313.43  5925.1  313.68  5941.3  313.71  5956.2  315.02
  5968.8  315.69    5985  315.01  5990.7  316.35  6006.8  316.58  6013.1  316.19
  6022.9  316.14  6094.2  318.45  6110.3  318.75    6116  319.14  6139.1  319.63
#Mann= 3 ,-1 , 0
    4677     .05       0  4969.4     .03       0  4975.4     .05       0
Bank Sta=4952.3,5859.6
XS Rating Curve= 0 ,0
Exp/Cntr=0.3,0.1

Type RM Length L Ch R = 1 ,951     ,126,126,126
BEGIN DESCRIPTION:
Mapping XS 02576cb6
END DESCRIPTION:
XS GIS Cut Line= 6
      3712930.14     10649692.05      3712849.85      10648954.2
      3712730.49     10648902.11      3712585.09     10648882.58
      3712420.16      10648895.6      3712044.76     10649023.63
#Sta/Elev= 30
  4709.3  318.32  4893.2  313.86  5001.4  311.79  5052.4  313.77  5119.6   312.5
  5124.6  313.37  5243.1  313.43  5333.5  312.34  5409.7  313.49  5456.5  312.71
  5531.8  313.66    5547  312.56  5572.2  313.34  5577.5  312.58  5615.3  313.67
  5767.7  314.02  5886.4  312.65    5894  313.39  5961.2  313.45  5987.3  312.23
  5992.6   313.2  6018.6  311.35  6034.2  312.81  6107.4   313.4  6112.7  314.54
  6138.7  314.44    6144  315.37    6161  314.14  6192.7  316.97  6292.9  319.78
#Mann= 3 ,-1 , 0
  4709.3     .05       0    6084     .03       0    6090     .05       0
Bank Sta=4893.2,6112.7
XS Rating Curve= 0 ,0
Exp/Cntr=0.3,0.1

Type RM Length L Ch R = 1 ,825     ,277,277,277
BEGIN DESCRIPTION:
Mapping XS 266c6313
END DESCRIPTION:
XS GIS Cut Line= 6
      3713038.38     10649744.45      3713001.93     10649166.37
      3712882.13      10648937.2      3712790.99      10648874.7
      3712580.05     10648843.45      3712044.15      10649009.9
#Sta/Elev= 30
  4608.5  315.92  4933.4  312.15  4987.4  310.86  4993.5  309.06  5013.6  311.63
  5103.7  308.54  5239.8  307.32  5318.8  307.45  5436.1  305.82  5438.9  305.32
  5442.1  305.82  5443.6  308.01  5452.7  306.93  5482.5   309.9  5503.4  307.71
  5737.1  309.65  5761.3  308.06  5791.5  310.12    6016  309.52  6105.4  312.27
  6129.9  309.29  6154.3   311.6  6159.7   313.8  6167.6  313.27  6184.2  307.54
  6189.5  311.97  6199.9   309.9  6208.6  314.21  6221.3  315.88  6334.6  320.25
#Mann= 3 ,-1 , 0
  4608.5     .05       0  5436.1     .03       0  5442.1     .05       0
Bank Sta=5239.8,5318.8
XS Rating Curve= 0 ,0
Exp/Cntr=0.3,0.1

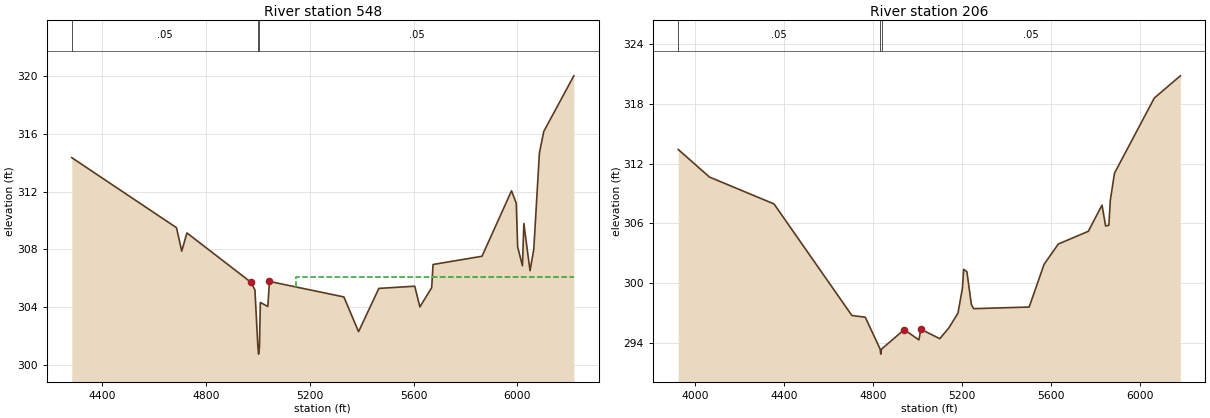
Type RM Length L Ch R = 1 ,548     ,342,342,342
BEGIN DESCRIPTION:
Mapping XS 5efe484d
END DESCRIPTION:
XS GIS Cut Line= 6
      3713134.14     10649813.57      3713138.48     10649175.55
      3712945.33     10648936.84      3712802.11     10648834.84
      3712585.09     10648802.29      3712027.36     10648999.77
#Sta/Elev= 30
  4283.7  314.34  4687.1   309.5  4707.1  307.88  4727.1  309.14  4974.6  305.72
    4989   305.2  5000.4  301.27  5003.1  300.77  5006.4  301.27  5009.8  304.34
  5038.6  304.06    5045  305.79  5331.5  304.72    5388  302.32  5466.2  305.31
  5604.4  305.46  5624.1  304.03  5669.6  305.36  5674.8  306.96  5863.4  307.53
    5977  312.05  5995.3  311.19  6000.7  308.17  6019.1  306.87  6024.5  309.79
  6048.3  306.53  6062.7     308  6084.4  314.66  6101.2  316.15    6217  319.99
#Mann= 3 ,-1 , 0
  4283.7     .05       0  5000.4     .03       0  5006.4     .05       0
#XS Ineff= 2 , 0
                         5146.95          306.09
Permanent Ineff=
       F       F
Bank Sta=4974.6,5045
XS Rating Curve= 0 ,0
Exp/Cntr=0.3,0.1

Type RM Length L Ch R = 1 ,206     ,0,0,0
BEGIN DESCRIPTION:
UNT 03305 IN LACR 1.0
END DESCRIPTION:
XS GIS Cut Line= 5
      3713201.86     10649760.59      3713188.84     10648840.45
      3712932.77     10648744.97      3712576.86     10648705.91
      3711913.68     10648944.31
#Sta/Elev= 30
  3925.4  313.41  4065.8  310.64  4355.8  307.94  4705.9  296.73  4765.9  296.56
  4832.9  293.35  4835.6  292.85  4838.9  293.35  4940.9  295.31    5007  294.28
  5015.6  295.35    5101   294.4  5142.2  295.51  5182.5  296.96  5202.6  299.49
  5208.1  301.37  5222.7  301.13  5242.8  297.83  5252.9  297.42  5502.5  297.58
  5569.7  301.88  5633.4  303.91  5768.4  305.19  5829.8  307.82    5846  305.73
  5860.5  305.79  5867.2  308.31  5885.9  311.03  6064.9  318.58  6181.7  320.81
#Mann= 3 ,-1 , 0
  3925.4     .05       0  4832.9     .03       0  4838.9     .05       0
Bank Sta=4940.9,5015.6
XS Rating Curve= 0 ,0
Exp/Cntr=0.3,0.1

Chan Stop Cuts=-1
Use User Specified Reach Order=0
Composite Channel Slope=5