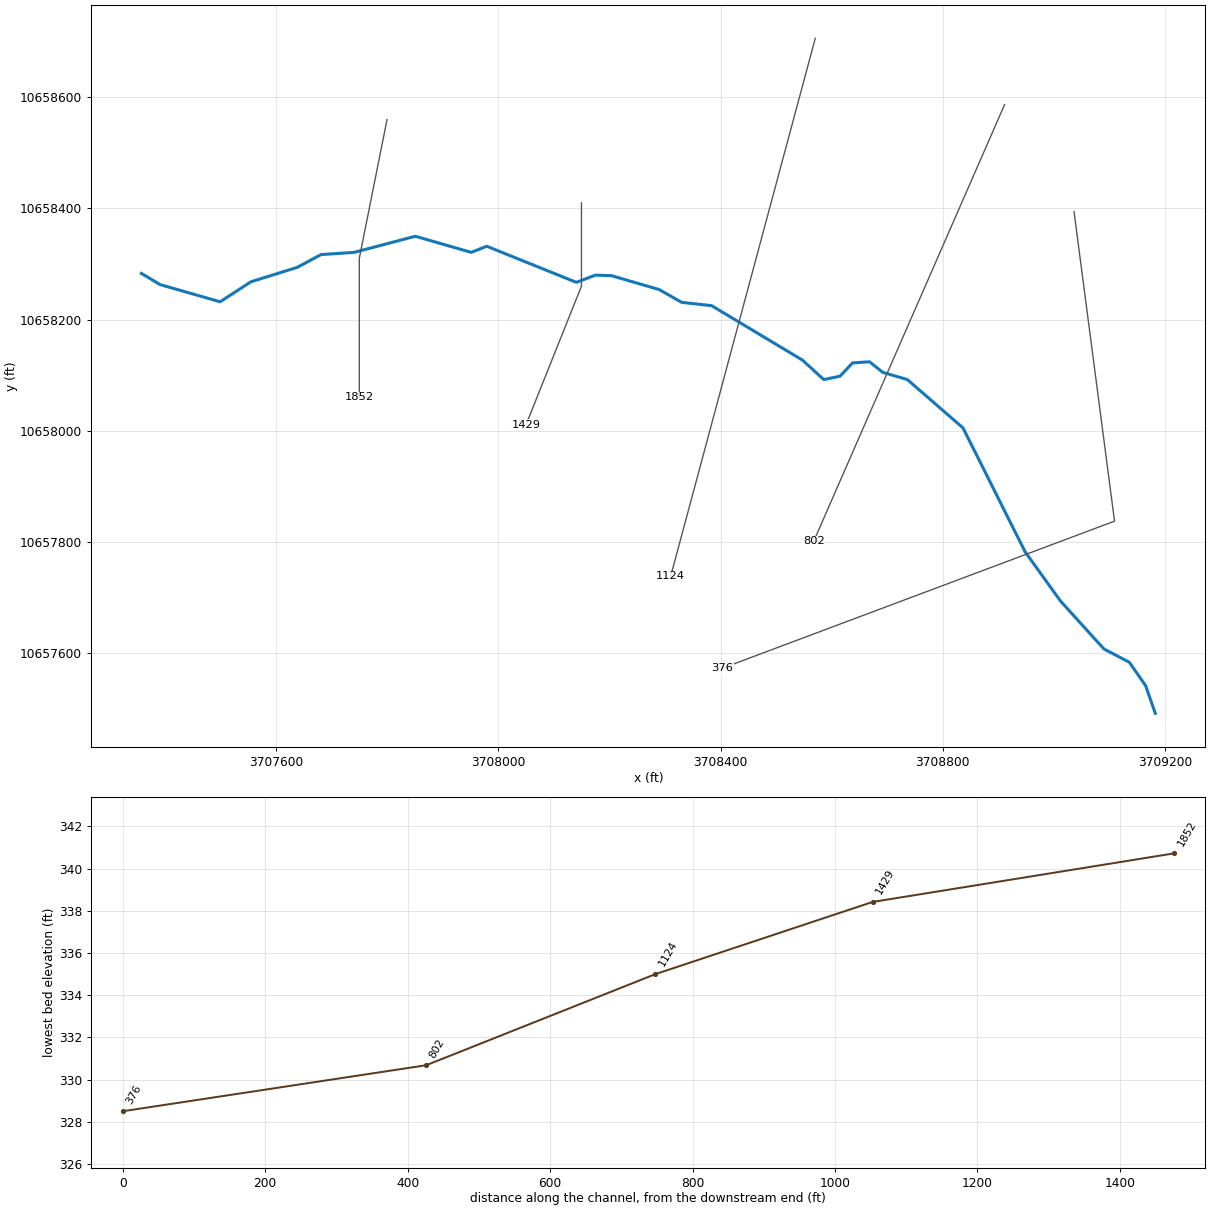
--- UNT 03314 IN LACR.prj (project) ---

Proj Title=UNT 03314 IN LACR Base Level Engineering
Current Plan=p01
Default Exp/Contr=0.3,0.1
English Units
Geom File=g01
Flow File=f01
Plan File=p01
BEGIN DESCRIPTION:
UNT 03314 IN LACR
END DESCRIPTION:

--- UNT 03314 IN LACR.p01 (plan) ---

Plan Title=Multiple Run
Short Identifier=Multiple
Geom File=g01
Flow File=f01
Subcritical Flow
K Sum by GR= 0
Std Step Tol= 0.01
Critical Tol= 0.01
Num of Std Step Trials= 20
Max Error Tol= 0.3
Flow Tol Ratio= 0.001
Split Flow NTrial= 30
Split Flow Tol= 0.02
Split Flow Ratio= 0.02
Log Output Level= 0
Friction Slope Method= 1
Unsteady Friction Slope Method= 2
Unsteady Bridges Friction Slope Method= 1
Parabolic Critical Depth
Global Vel Dist=  1 , 1 , 1
Global Log Level= 0
CheckData=True
Encroach Param= -1, 0, 0, 0
BEGIN DESCRIPTION:
Multiple Run
END DESCRIPTION:

--- UNT 03314 IN LACR.f01 (steady flow) ---

Flow Title=Multiple
Number of Profiles=7
Profile Names=10-year,25-year,50-year,1pct_min,100-year,1pct_plu,500-year
River Rch & RM= UNT 03314 IN LAC,Reach-1,1852
     221     281     329     284     384     519     523
Boundary for River Rch & Prof#=UNT 03314 IN LAC,Reach-1,1
Up Type=0
Dn Type=3
Dn Slope=0.005
Boundary for River Rch & Prof#=UNT 03314 IN LAC,Reach-1,2
Up Type=0
Dn Type=3
Dn Slope=0.005
Boundary for River Rch & Prof#=UNT 03314 IN LAC,Reach-1,3
Up Type=0
Dn Type=3
Dn Slope=0.005
Boundary for River Rch & Prof#=UNT 03314 IN LAC,Reach-1,4
Up Type=0
Dn Type=3
Dn Slope=0.005
Boundary for River Rch & Prof#=UNT 03314 IN LAC,Reach-1,5
Up Type=0
Dn Type=3
Dn Slope=0.005
Boundary for River Rch & Prof#=UNT 03314 IN LAC,Reach-1,6
Up Type=0
Dn Type=3
Dn Slope=0.005
Boundary for River Rch & Prof#=UNT 03314 IN LAC,Reach-1,7
Up Type=0
Dn Type=3
Dn Slope=0.005

--- UNT 03314 IN LACR.g01 (geometry) ---

Geom Title=Existing Conditions

River Reach=UNT 03314 IN LAC,Reach-1
Reach XY= 30
      3707357.32     10658283.08      3707391.00     10658263.00
      3707499.00     10658232.00      3707554.50     10658268.00
      3707638.00     10658294.00      3707680.75     10658317.00
      3707740.50     10658321.00      3707850.50     10658350.00
      3707951.25     10658321.00      3707979.00     10658332.00
      3708140.50     10658267.00      3708174.75     10658280.00
      3708203.75     10658279.00      3708289.50     10658254.00
      3708330.00     10658231.00      3708384.00     10658225.00
      3708547.50     10658127.00      3708585.75     10658092.00
      3708615.00     10658098.00      3708637.75     10658122.00
      3708668.25     10658124.00      3708692.00     10658105.00
      3708736.25     10658092.00      3708836.50     10658005.00
      3708948.25     10657782.00      3709012.25     10657693.00
      3709090.25     10657607.00      3709136.00     10657583.00
      3709165.25     10657541.00      3709182.75     10657491.00

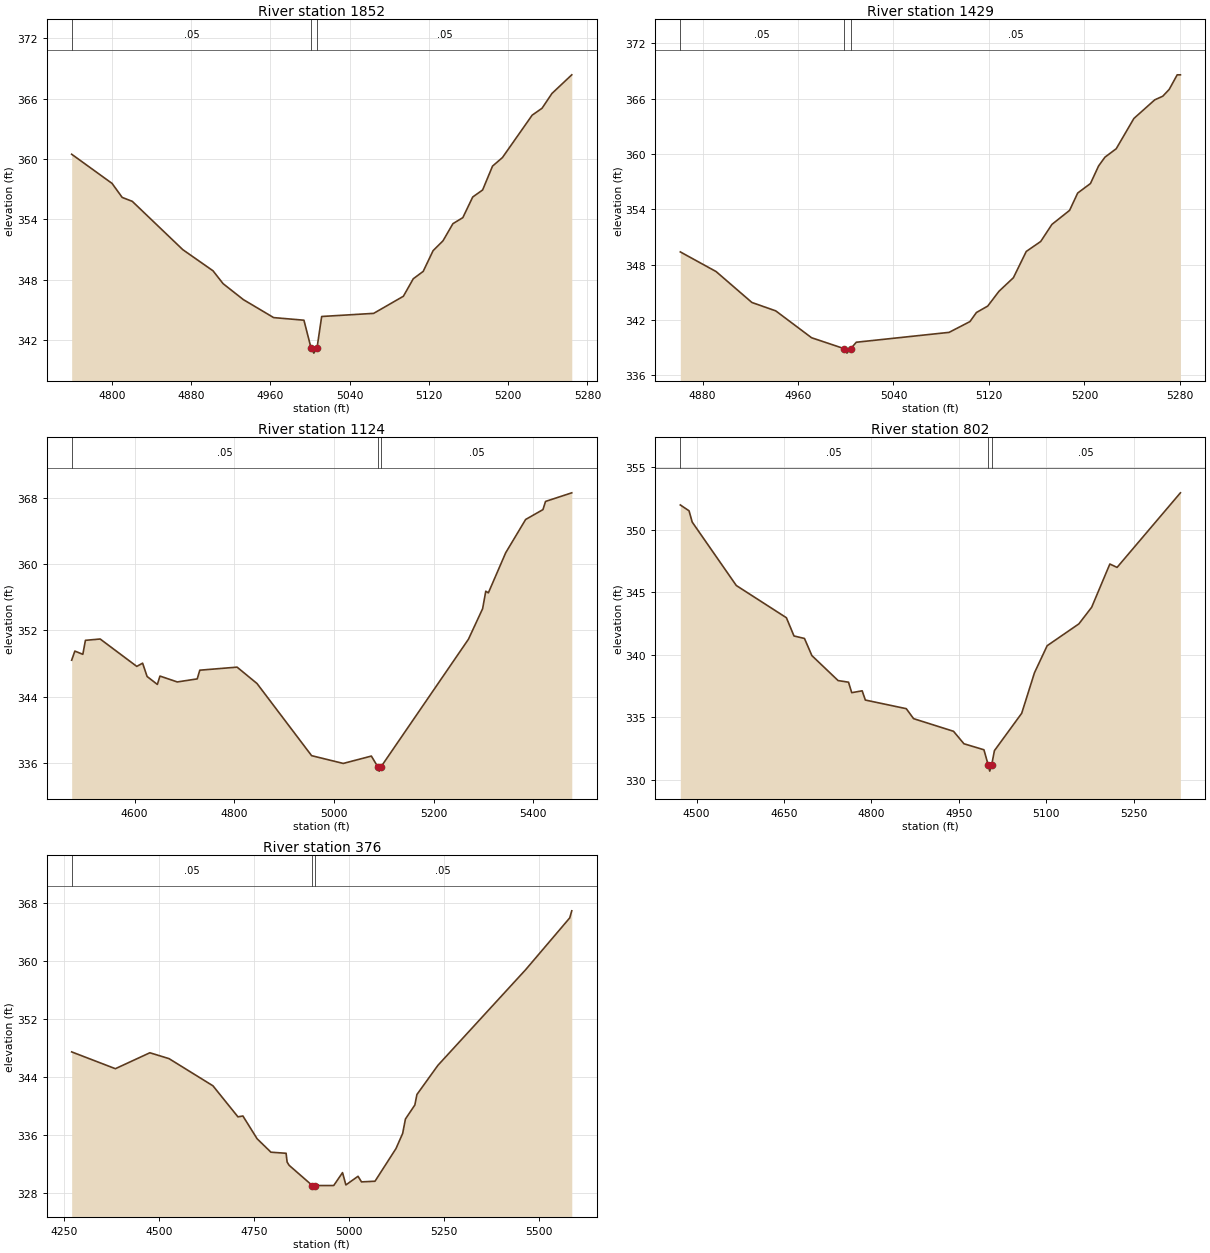
Type RM Length L Ch R = 1,1852,423,423,423
BEGIN DESCRIPTION:
UNT 03314 IN LACR 4.0
END DESCRIPTION:
XS GIS Cut Line= 3
      3707799.60     10658560.16      3707749.61     10658310.19
      3707749.61     10658060.21
#Sta/Elev= 30
  4759.3  360.48  4800.1  357.58  4810.3  356.19  4820.5  355.80  4871.5  351.00
  4902.0  348.90  4912.2  347.62  4932.6  346.04  4963.2  344.25  4993.8  343.99
  5001.0  341.22  5003.8  340.72  5007.0  341.22  5011.7  344.36  5064.2  344.67
  5094.2  346.37  5104.2  348.11  5114.2  348.84  5124.2  350.90  5134.2  351.88
  5144.2  353.58  5154.2  354.18  5164.2  356.23  5174.2  356.93  5184.2  359.30
  5194.2  360.15  5224.2  364.36  5234.2  365.05  5244.2  366.52  5264.2  368.37
#Mann=3,-1,0
  4759.3    0.05       0  5001.0    0.03       0  5007.0    0.05       0
Bank Sta=5001,5007
Exp/Cntr=0.3,0.1

Type RM Length L Ch R = 1,1429,305,305,305
BEGIN DESCRIPTION:
UNT 03314 IN LACR 3.0
END DESCRIPTION:
XS GIS Cut Line= 3
      3708149.61     10658410.14      3708149.61     10658260.19
      3708049.61     10658010.20
#Sta/Elev= 30
  4861.3  349.39  4891.3  347.26  4921.3  343.91  4941.3  343.00  4971.3  340.09
  4998.3  338.92  5001.0  338.42  5004.3  338.92  5008.8  339.60  5086.6  340.67
  5104.1  341.84  5109.5  342.82  5119.0  343.52  5128.4  345.12  5140.5  346.59
  5151.3  349.44  5163.4  350.52  5172.8  352.37  5187.6  353.89  5194.4  355.77
  5205.1  356.80  5211.9  358.70  5217.2  359.65  5226.7  360.57  5241.5  363.85
  5259.0  365.87  5265.7  366.26  5271.1  367.00  5277.8  368.58  5280.5  368.58
#Mann=3,-1,0
  4861.3    0.05       0  4998.3    0.03       0  5004.3    0.05       0
Bank Sta=4998.3,5004.3
Exp/Cntr=0.3,0.1

Type RM Length L Ch R = 1,1124,322,322,322
BEGIN DESCRIPTION:
UNT 03314 IN LACR 2.0
END DESCRIPTION:
XS GIS Cut Line= 2
      3708570.56     10658706.32      3708310.13     10657737.52
#Sta/Elev= 30
  4473.9  348.41  4480.3  349.51  4496.3  349.12  4501.5  350.81  4531.1  350.97
  4604.5  347.66  4616.2  348.05  4625.2  346.44  4645.8  345.48  4651.0  346.49
  4685.8  345.78  4725.8  346.15  4730.9  347.20  4805.7  347.57  4845.7  345.59
  4955.2  336.87  5018.7  335.93  5075.1  336.82  5088.2  335.50  5090.9  335.00
  5094.2  335.50  5269.8  350.94  5298.3  354.64  5304.6  356.75  5309.8  356.55
  5344.6  361.40  5384.6  365.42  5419.3  366.61  5424.5  367.60  5477.1  368.64
#Mann=3,-1,0
  4473.9    0.05       0  5088.2    0.03       0  5094.2    0.05       0
Bank Sta=5088.2,5094.2
Exp/Cntr=0.3,0.1

Type RM Length L Ch R = 1,802,426,426,426
BEGIN DESCRIPTION:
Mapping XS 2f81003e
END DESCRIPTION:
XS GIS Cut Line= 2
      3708911.41     10658587.07      3708567.66     10657800.61
#Sta/Elev= 30
  4472.0  351.99  4487.0  351.52  4492.4  350.62  4568.1  345.54  4654.1  342.96
  4667.1  341.50  4685.1  341.30  4697.8  339.93  4742.8  337.93  4760.7  337.80
  4766.2  336.96  4784.1  337.11  4789.6  336.37  4859.8  335.68  4872.4  334.88
  4940.9  333.87  4958.8  332.87  4993.1  332.39  5000.4  331.18  5003.1  330.68
  5006.4  331.18  5011.1  332.32  5057.9  335.31  5079.8  338.55  5101.6  340.72
  5156.1  342.47  5178.0  343.80  5209.2  347.26  5221.6  346.99  5330.3  352.96
#Mann=3,-1,0
  4472.0    0.05       0  5000.4    0.03       0  5006.4    0.05       0
Bank Sta=5000.4,5006.4
Exp/Cntr=0.3,0.1

Type RM Length L Ch R = 1,376,0,0,0
BEGIN DESCRIPTION:
UNT 03314 IN LACR 1.0
END DESCRIPTION:
XS GIS Cut Line= 3
      3709036.41     10658394.32      3709109.32     10657837.06
      3708402.77     10657572.10
#Sta/Elev= 30
  4269.2  347.45  4384.3  345.13  4475.1  347.33  4525.5  346.52  4641.1  342.77
  4707.0  338.48  4720.0  338.60  4757.5  335.45  4793.8  333.60  4833.7  333.45
  4836.4  332.24  4841.7  331.79  4902.7  329.00  4905.4  328.50  4908.7  329.00
  4959.1  329.00  4982.3  330.78  4991.1  329.08  5023.1  330.27  5032.2  329.50
  5067.8  329.59  5123.0  334.10  5140.6  336.19  5147.9  338.18  5172.7  340.12
  5178.1  341.56  5233.3  345.59  5464.7  358.82  5580.4  365.95  5585.8  366.93
#Mann=3,-1,0
  4269.2    0.05       0  4902.7   0.033       0  4908.7    0.05       0
Bank Sta=4902.7,4908.7
Exp/Cntr=0.3,0.1

Chan Stop Cuts=-1