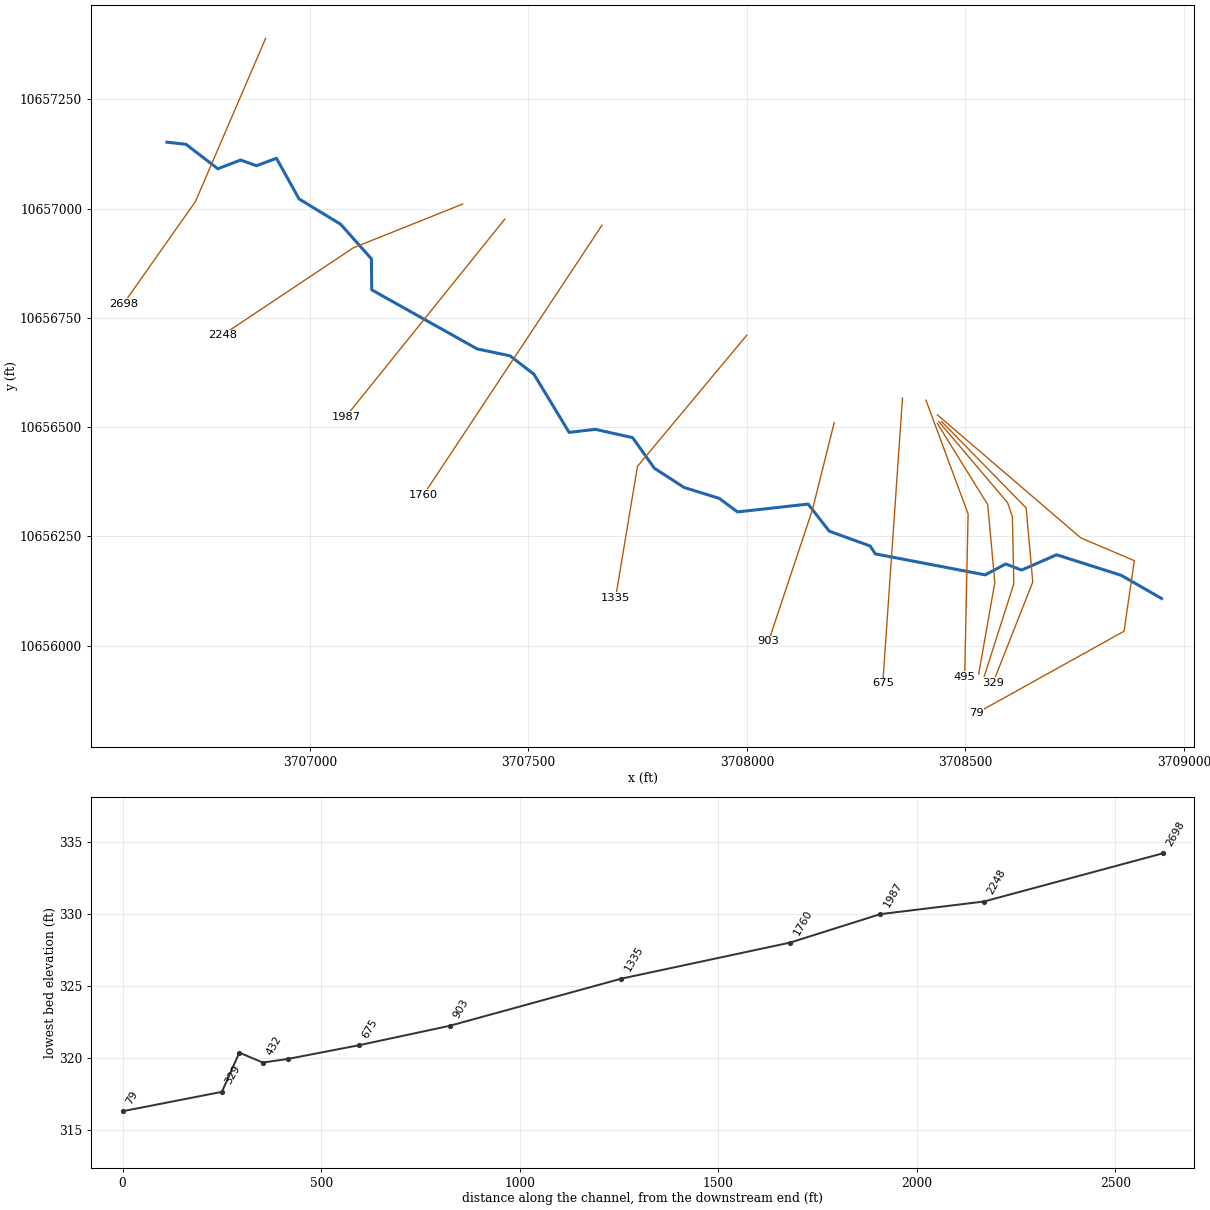
--- UNT 03315 IN LACR.prj (project) ---

Proj Title=UNT 03315 IN LACR Base Level Engineering
Current Plan=p01
Default Exp/Contr=0.3,0.1
English Units
Geom File=g01
Flow File=f01
Plan File=p01
BEGIN DESCRIPTION:
UNT 03315 IN LACR
END DESCRIPTION:

--- UNT 03315 IN LACR.p01 (plan) ---

Plan Title=Multiple Run
Short Identifier=Multiple
Geom File=g01
Flow File=f01
Subcritical Flow
K Sum by GR= 0
Std Step Tol= 0.01
Critical Tol= 0.01
Num of Std Step Trials= 20
Max Error Tol= 0.3
Flow Tol Ratio= 0.001
Split Flow NTrial= 30
Split Flow Tol= 0.02
Split Flow Ratio= 0.02
Log Output Level= 0
Friction Slope Method= 1
Unsteady Friction Slope Method= 2
Unsteady Bridges Friction Slope Method= 1
Parabolic Critical Depth
Global Vel Dist=  1 , 1 , 1
Global Log Level= 0
CheckData=True
Encroach Param= -1, 0, 0, 0
BEGIN DESCRIPTION:
Multiple Run
END DESCRIPTION:

--- UNT 03315 IN LACR.f01 (steady flow) ---

Flow Title=Multiple
Number of Profiles=7
Profile Names=10-year,25-year,50-year,1pct_min,100-year,1pct_plu,500-year
River Rch & RM= UNT 03315 IN LAC,Reach-1,2698
     346     456     544     479     648     877     921
River Rch & RM= UNT 03315 IN LAC,Reach-1,79
     751    1024    1250    1120    1515    2048    2232
Boundary for River Rch & Prof#=UNT 03315 IN LAC,Reach-1,1
Up Type=0
Dn Type=3
Dn Slope=0.005
Boundary for River Rch & Prof#=UNT 03315 IN LAC,Reach-1,2
Up Type=0
Dn Type=3
Dn Slope=0.005
Boundary for River Rch & Prof#=UNT 03315 IN LAC,Reach-1,3
Up Type=0
Dn Type=3
Dn Slope=0.005
Boundary for River Rch & Prof#=UNT 03315 IN LAC,Reach-1,4
Up Type=0
Dn Type=3
Dn Slope=0.005
Boundary for River Rch & Prof#=UNT 03315 IN LAC,Reach-1,5
Up Type=0
Dn Type=3
Dn Slope=0.005
Boundary for River Rch & Prof#=UNT 03315 IN LAC,Reach-1,6
Up Type=0
Dn Type=3
Dn Slope=0.005
Boundary for River Rch & Prof#=UNT 03315 IN LAC,Reach-1,7
Up Type=0
Dn Type=3
Dn Slope=0.005

--- UNT 03315 IN LACR.g01 (geometry) ---

Geom Title=Existing Conditions

River Reach=UNT 03315 IN LAC,Reach-1
Reach XY= 30
      3706673.18     10657151.88      3706716.75     10657147.00
      3706789.75     10657091.00      3706841.75     10657111.00
      3706878.25     10657098.00      3706923.75     10657115.00
      3706975.50     10657022.00      3707070.75     10656964.00
      3707141.00     10656885.00      3707141.75     10656814.00
      3707382.75     10656679.00      3707458.25     10656663.00
      3707512.75     10656621.00      3707593.25     10656488.00
      3707653.00     10656495.00      3707738.50     10656476.00
      3707788.25     10656406.00      3707856.25     10656362.00
      3707936.75     10656337.00      3707978.50     10656306.00
      3708140.00     10656324.00      3708188.25     10656262.00
      3708282.00     10656228.00      3708293.75     10656210.00
      3708545.00     10656162.00      3708592.00     10656187.00
      3708628.25     10656173.00      3708708.50     10656208.00
      3708856.25     10656161.00      3708948.50     10656108.00

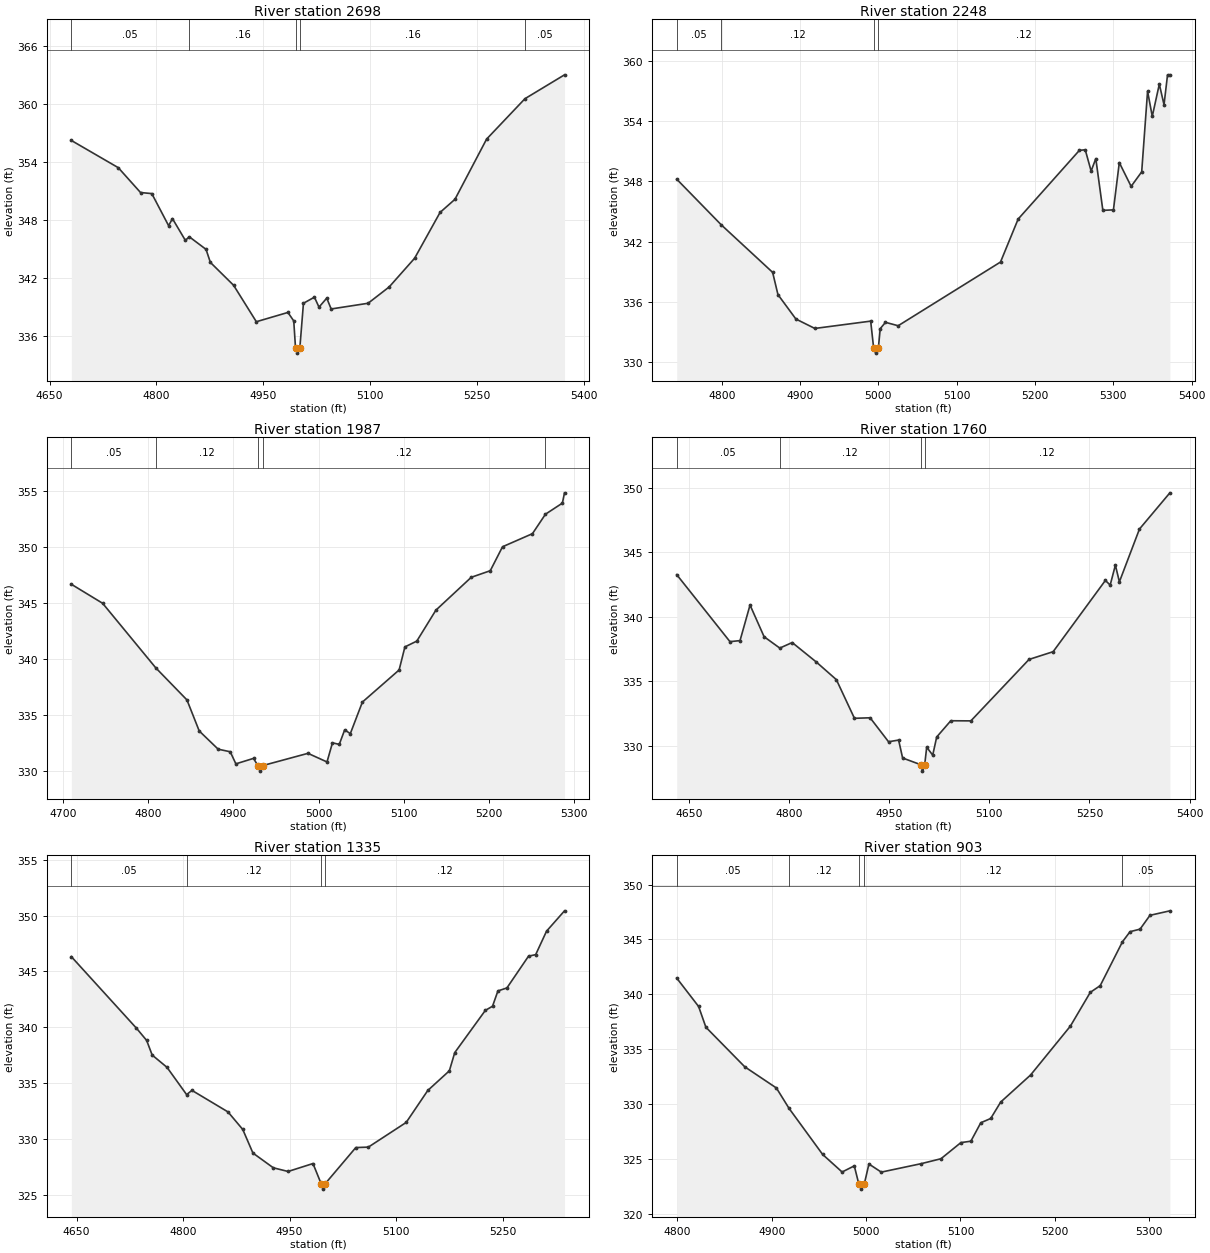
Type RM Length L Ch R = 1,2698,450,450,450
BEGIN DESCRIPTION:
UNT 03315 IN LACR 6.0
END DESCRIPTION:
XS GIS Cut Line= 3
      3706899.05     10657389.39      3706738.44     10657016.09
      3706574.07     10656782.51
#Sta/Elev= 30
  4680.5  356.25  4746.4  353.43  4777.6  350.86  4793.4  350.75  4817.0  347.43
  4822.4  348.16  4840.5  345.91  4846.0  346.28  4869.5  344.98  4875.6  343.63
  4908.2  341.26  4940.1  337.49  4984.4  338.45  4992.6  337.57  4995.1  334.74
  4997.8  334.24  5001.1  334.74  5006.2  339.40  5021.6  340.03  5028.0  339.00
  5038.9  339.93  5045.1  338.81  5096.9  339.40  5126.5  341.09  5162.2  344.06
  5197.9  348.80  5218.8  350.16  5263.2  356.39  5317.0  360.57  5372.5  363.04
#Mann=5,-1,0
  4680.5    0.05       0  4846.0    0.16       0  4995.1    0.07       0
  5001.1    0.16       0  5317.0    0.05       0
Bank Sta=4995.1,5001.1
Exp/Cntr=0.3,0.1

Type RM Length L Ch R = 1,2248,261,261,261
BEGIN DESCRIPTION:
UNT 03315 IN LACR 5.0
END DESCRIPTION:
XS GIS Cut Line= 3
      3707349.64     10657010.20      3707099.61     10656910.19
      3706799.65     10656710.21
#Sta/Elev= 30
  4742.4  348.23  4799.4  343.67  4864.9  338.94  4871.7  336.72  4894.6  334.29
  4918.8  333.35  4990.1  334.08  4993.9  331.39  4996.6  330.89  4999.9  331.39
  5002.3  333.33  5009.0  333.96  5025.2  333.62  5155.9  339.97  5178.4  344.25
  5256.6  351.10  5264.1  351.16  5271.6  349.04  5277.6  350.28  5286.6  345.12
  5300.1  345.17  5307.6  349.88  5322.7  347.51  5336.2  348.96  5343.7  357.00
  5349.7  354.49  5358.7  357.70  5364.7  355.65  5369.2  358.63  5372.2  358.63
#Mann=4,-1,0
  4742.4    0.05       0  4799.4    0.12       0  4993.9    0.07       0
  4999.9    0.12       0
Bank Sta=4993.9,4999.9
Exp/Cntr=0.3,0.1

Type RM Length L Ch R = 1,1987,227,227,227
BEGIN DESCRIPTION:
Mapping XS ee9b5bd7
END DESCRIPTION:
XS GIS Cut Line= 2
      3707446.07     10656975.81      3707082.48     10656523.92
#Sta/Elev= 30
  4709.3  346.71  4746.1  345.01  4808.6  339.24  4845.3  336.37  4859.7  333.60
  4882.0  331.97  4896.2  331.74  4902.8  330.66  4923.6  331.15  4928.6  330.51
  4931.4  330.01  4934.6  330.51  4987.6  331.60  5010.0  330.83  5016.4  332.54
  5024.4  332.40  5030.8  333.70  5037.4  333.36  5051.6  336.18  5094.8  339.05
  5101.6  341.11  5115.6  341.63  5138.0  344.39  5179.6  347.33  5202.0  347.92
  5216.4  350.06  5251.6  351.23  5266.9  352.97  5286.8  353.96  5289.3  354.88
#Mann=5,-1,0
  4709.3    0.05       0  4808.6    0.12       0  4928.6    0.07       0
  4934.6    0.12       0  5266.9    0.05       0
Bank Sta=4928.6,4934.6
Exp/Cntr=0.3,0.1

Type RM Length L Ch R = 1,1760,425,425,425
BEGIN DESCRIPTION:
UNT 03315 IN LACR 4.0
END DESCRIPTION:
XS GIS Cut Line= 2
      3707668.54     10656961.96      3707260.51     10656345.58
#Sta/Elev= 30
  4631.3  343.28  4711.1  338.08  4726.2  338.16  4741.2  340.92  4762.3  338.46
  4785.8  337.58  4804.4  338.01  4840.5  336.50  4870.6  335.13  4897.7  332.13
  4921.2  332.17  4948.8  330.31  4963.9  330.44  4969.9  329.05  4997.0  328.53
  4999.7  328.03  5003.0  328.53  5006.0  329.89  5015.0  329.27  5021.0  330.68
  5042.1  331.94  5072.2  331.93  5159.4  336.70  5195.5  337.30  5273.8  342.83
  5281.0  342.47  5288.8  344.02  5294.8  342.72  5324.9  346.82  5370.5  349.63
#Mann=4,-1,0
  4631.3    0.05       0  4785.8    0.12       0  4997.0    0.07       0
  5003.0    0.12       0
Bank Sta=4997,5003
Exp/Cntr=0.3,0.1

Type RM Length L Ch R = 1,1335,432,432,432
BEGIN DESCRIPTION:
UNT 03315 IN LACR 3.0
END DESCRIPTION:
XS GIS Cut Line= 3
      3707999.64     10656710.22      3707749.61     10656410.19
      3707699.61     10656110.18
#Sta/Elev= 30
  4642.6  346.33  4734.4  339.92  4748.7  338.83  4756.5  337.52  4777.4  336.42
  4805.0  333.98  4812.5  334.36  4863.3  332.43  4884.1  330.86  4898.4  328.75
  4927.1  327.43  4947.9  327.10  4983.0  327.81  4994.4  326.02  4997.1  325.52
  5000.4  326.02  5043.3  329.24  5061.0  329.28  5114.3  331.49  5144.7  334.35
  5175.1  336.11  5182.7  337.74  5225.8  341.52  5235.9  341.89  5243.5  343.26
  5256.2  343.53  5286.6  346.37  5296.7  346.51  5312.0  348.61  5337.3  350.43
#Mann=4,-1,0
  4642.6    0.05       0  4805.0    0.12       0  4994.4    0.07       0
  5000.4    0.12       0
Bank Sta=4994.4,5000.4
Exp/Cntr=0.3,0.1

Type RM Length L Ch R = 1,903,228,228,228
BEGIN DESCRIPTION:
UNT 03315 IN LACR 2.0
END DESCRIPTION:
XS GIS Cut Line= 3
      3708199.61     10656510.18      3708149.61     10656310.19
      3708049.60     10656010.17
#Sta/Elev= 30
  4799.4  341.48  4822.6  338.89  4830.3  337.00  4871.5  333.39  4905.0  331.46
  4918.4  329.60  4954.0  325.40  4974.6  323.80  4987.5  324.36  4992.2  322.74
  4995.0  322.24  4998.2  322.74  5003.0  324.53  5016.1  323.79  5058.3  324.56
  5079.3  325.01  5100.4  326.48  5111.0  326.61  5121.5  328.29  5132.0  328.68
  5142.6  330.18  5174.2  332.64  5216.4  337.10  5237.5  340.18  5248.0  340.79
  5271.5  344.78  5279.6  345.71  5290.2  345.94  5300.7  347.20  5321.8  347.61
#Mann=5,-1,0
  4799.4    0.05       0  4918.4    0.12       0  4992.2    0.07       0
  4998.2    0.12       0  5271.5    0.05       0
Bank Sta=4992.2,4998.2
Exp/Cntr=0.3,0.1

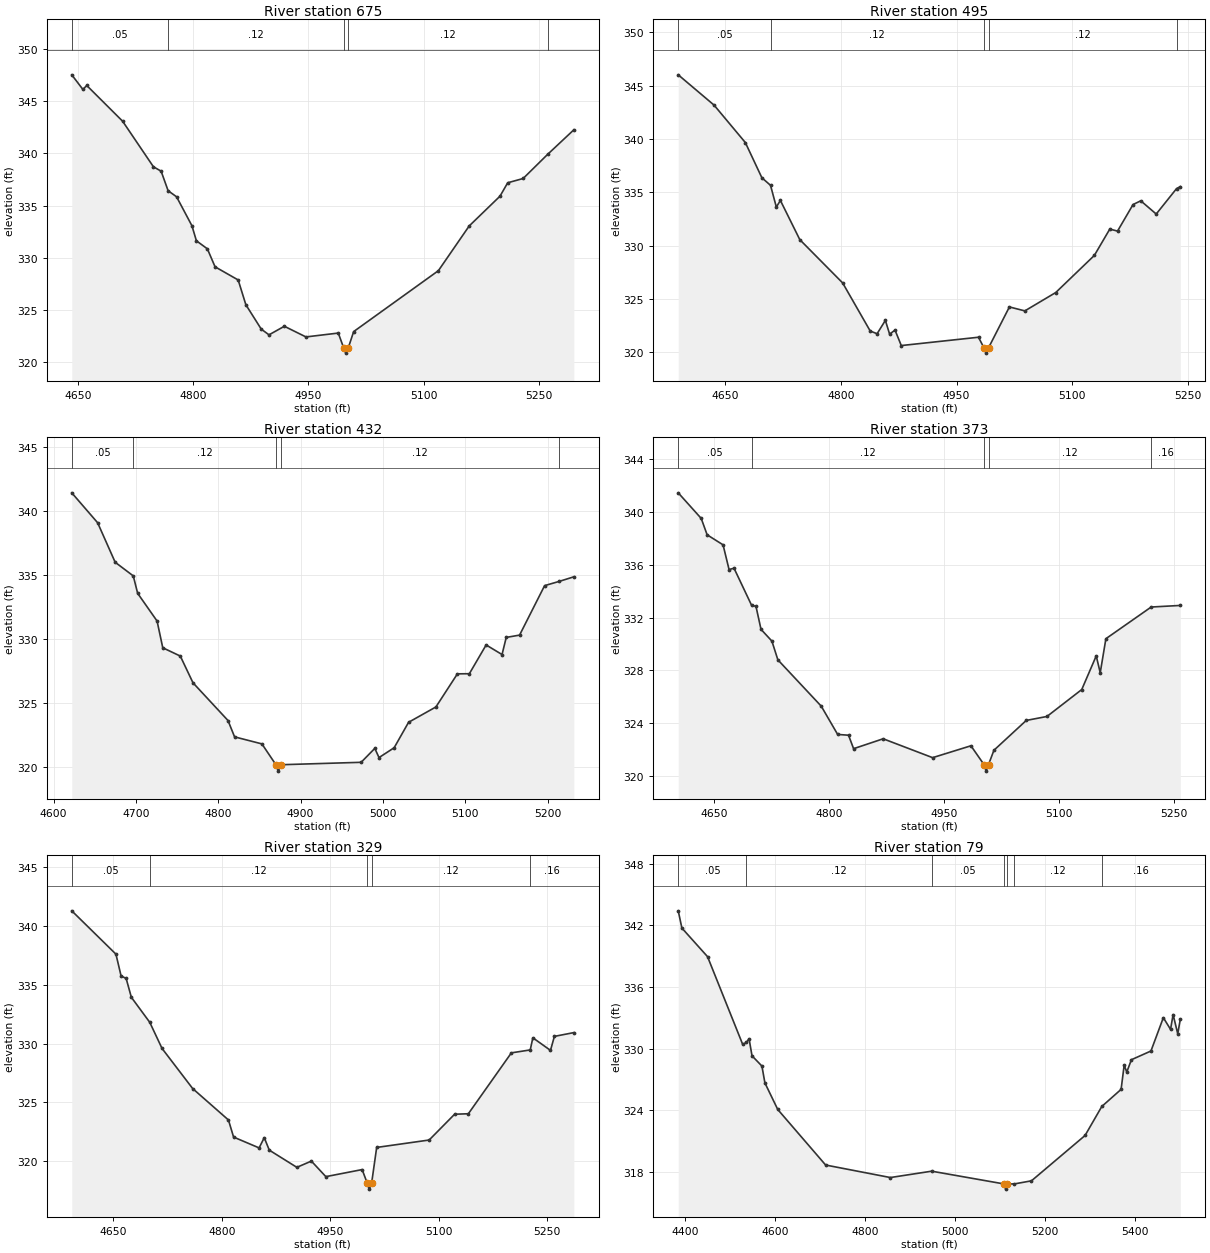
Type RM Length L Ch R = 1,675,180,180,180
BEGIN DESCRIPTION:
Mapping XS 619527fd
END DESCRIPTION:
XS GIS Cut Line= 2
      3708355.85     10656566.25      3708310.77     10655914.30
#Sta/Elev= 30
  4642.0  347.52  4656.5  346.12  4661.5  346.50  4708.2  343.08  4748.3  338.72
  4758.3  338.30  4767.4  336.43  4778.4  335.85  4798.4  333.08  4804.2  331.64
  4818.5  330.87  4828.5  329.15  4858.6  327.89  4868.6  325.52  4888.6  323.19
  4898.7  322.64  4918.7  323.46  4946.8  322.44  4988.9  322.81  4995.9  321.39
  4998.7  320.89  5001.9  321.39  5008.9  322.95  5119.2  328.78  5159.3  333.06
  5199.4  335.91  5209.4  337.19  5229.5  337.60  5261.4  339.91  5295.5  342.26
#Mann=5,-1,0
  4642.0    0.05       0  4767.4    0.12       0  4995.9    0.07       0
  5001.9    0.12       0  5261.4    0.05       0
Bank Sta=4995.9,5001.9
Exp/Cntr=0.3,0.1

Type RM Length L Ch R = 1,495,63,63,63
BEGIN DESCRIPTION:
Mapping XS 81339da7
END DESCRIPTION:
XS GIS Cut Line= 3
      3708409.60     10656561.72      3708505.95     10656301.31
      3708498.14     10655928.96
#Sta/Elev= 30
  4589.6  346.02  4636.0  343.18  4676.5  339.67  4697.9  336.37  4709.1  335.66
  4716.6  333.63  4721.9  334.24  4747.0  330.57  4802.5  326.51  4838.2  322.00
  4847.1  321.75  4857.8  323.00  4863.3  321.71  4870.3  322.09  4878.4  320.64
  4978.4  321.42  4985.4  320.43  4988.2  319.93  4991.4  320.43  5018.4  324.26
  5038.4  323.89  5078.4  325.61  5128.4  329.09  5148.4  331.56  5158.4  331.37
  5178.5  333.86  5188.5  334.21  5208.5  332.97  5234.8  335.35  5239.7  335.54
#Mann=5,-1,0
  4589.6    0.05       0  4709.1    0.12       0  4985.4    0.07       0
  4991.4    0.12       0  5234.8    0.16       0
Bank Sta=4985.4,4991.4
Exp/Cntr=0.3,0.1

Type RM Length L Ch R = 1,432,59,59,59
BEGIN DESCRIPTION:
Mapping XS 030a568c
END DESCRIPTION:
XS GIS Cut Line= 4
      3708435.79     10656508.23      3708550.83     10656322.65
      3708567.10     10656144.70      3708530.21     10655935.26
#Sta/Elev= 30
  4622.1  341.45  4653.5  339.11  4674.8  336.02  4696.8  334.95  4702.1  333.59
  4725.7  331.42  4732.6  329.33  4753.9  328.68  4769.3  326.59  4811.8  323.64
  4819.8  322.36  4853.0  321.81  4870.0  320.18  4872.8  319.68  4876.0  320.18
  4973.5  320.37  4990.1  321.46  4995.2  320.74  5013.6  321.51  5031.1  323.50
  5064.3  324.70  5090.4  327.29  5104.9  327.30  5125.3  329.55  5144.6  328.80
  5149.7  330.14  5165.9  330.32  5196.3  334.19  5213.9  334.52  5231.8  334.88
#Mann=5,-1,0
  4622.1    0.05       0  4696.8    0.12       0  4870.0    0.07       0
  4876.0    0.12       0  5213.9    0.16       0
Bank Sta=4870,4876
Exp/Cntr=0.3,0.1

Type RM Length L Ch R = 1,373,44,44,44
BEGIN DESCRIPTION:
Mapping XS d293fbbc
END DESCRIPTION:
XS GIS Cut Line= 5
      3708439.06     10656512.55      3708596.40     10656326.99
      3708607.25     10656295.52      3708610.51     10656141.44
      3708542.15     10655927.69
#Sta/Elev= 30
  4602.7  341.45  4632.7  339.51  4640.4  338.27  4661.2  337.51  4669.0  335.64
  4675.5  335.74  4698.5  332.92  4704.1  332.86  4710.7  331.11  4724.9  330.22
  4732.7  328.80  4789.3  325.29  4810.7  323.15  4824.9  323.09  4831.5  322.07
  4870.1  322.82  4934.6  321.39  4984.6  322.29  5001.6  320.87  5004.4  320.37
  5007.6  320.87  5014.6  321.95  5056.8  324.21  5083.8  324.51  5129.2  326.55
  5148.1  329.10  5153.3  327.82  5160.7  330.40  5219.8  332.80  5257.8  332.92
#Mann=5,-1,0
  4602.7    0.05       0  4698.5    0.12       0  5001.6    0.07       0
  5007.6    0.12       0  5219.8    0.16       0
Bank Sta=5001.6,5007.6
Exp/Cntr=0.3,0.1

Type RM Length L Ch R = 1,329,250,250,250
BEGIN DESCRIPTION:
Mapping XS fdf3a2ef
END DESCRIPTION:
XS GIS Cut Line= 4
      3708445.55     10656512.57      3708638.72     10656315.06
      3708653.91     10656145.78      3708562.86     10655914.91
#Sta/Elev= 30
  4592.5  341.27  4653.6  337.59  4660.7  335.74  4667.7  335.53  4674.9  333.93
  4700.4  331.80  4717.3  329.59  4759.7  326.18  4809.2  323.51  4816.3  322.06
  4851.6  321.14  4858.7  322.01  4865.7  320.95  4903.8  319.49  4923.9  320.02
  4943.9  318.70  4994.1  319.30  5001.2  318.14  5003.9  317.64  5007.2  318.14
  5014.2  321.18  5086.8  321.81  5122.0  324.00  5141.0  324.04  5200.5  329.21
  5226.6  329.46  5230.2  330.49  5254.6  329.42  5260.0  330.61  5286.9  330.93
#Mann=5,-1,0
  4592.5    0.05       0  4700.4    0.12       0  5001.2    0.07       0
  5007.2    0.12       0  5226.6    0.16       0
Bank Sta=5001.2,5007.2
Exp/Cntr=0.3,0.1

Type RM Length L Ch R = 1,79,0,0,0
BEGIN DESCRIPTION:
UNT 03315 IN LACR 1.0
END DESCRIPTION:
XS GIS Cut Line= 5
      3708435.68     10656528.05      3708763.76     10656246.62
      3708886.16     10656194.54      3708862.72     10656033.08
      3708524.64     10655845.19
#Sta/Elev= 30
  4385.3  343.43  4393.4  341.75  4450.4  338.96  4528.4  330.41  4536.8  330.59
  4542.6  330.96  4549.2  329.29  4571.2  328.29  4577.8  326.65  4606.3  324.06
  4712.7  318.64  4856.5  317.42  4948.2  318.04  5109.7  316.79  5112.4  316.29
  5115.7  316.79  5132.1  316.80  5169.9  317.10  5288.9  321.52  5326.1  324.35
  5369.0  326.02  5375.8  328.38  5381.6  327.71  5391.9  328.91  5435.3  329.76
  5462.8  333.01  5478.8  331.87  5484.5  333.31  5494.8  331.44  5500.5  332.86
#Mann=7,-1,0
  4385.3    0.05       0  4536.8    0.12       0  4948.2    0.05       0
  5109.7    0.03       0  5115.7    0.05       0  5132.1    0.12       0
  5326.1    0.16       0
Bank Sta=5109.7,5115.7
Exp/Cntr=0.3,0.1

Chan Stop Cuts=-1