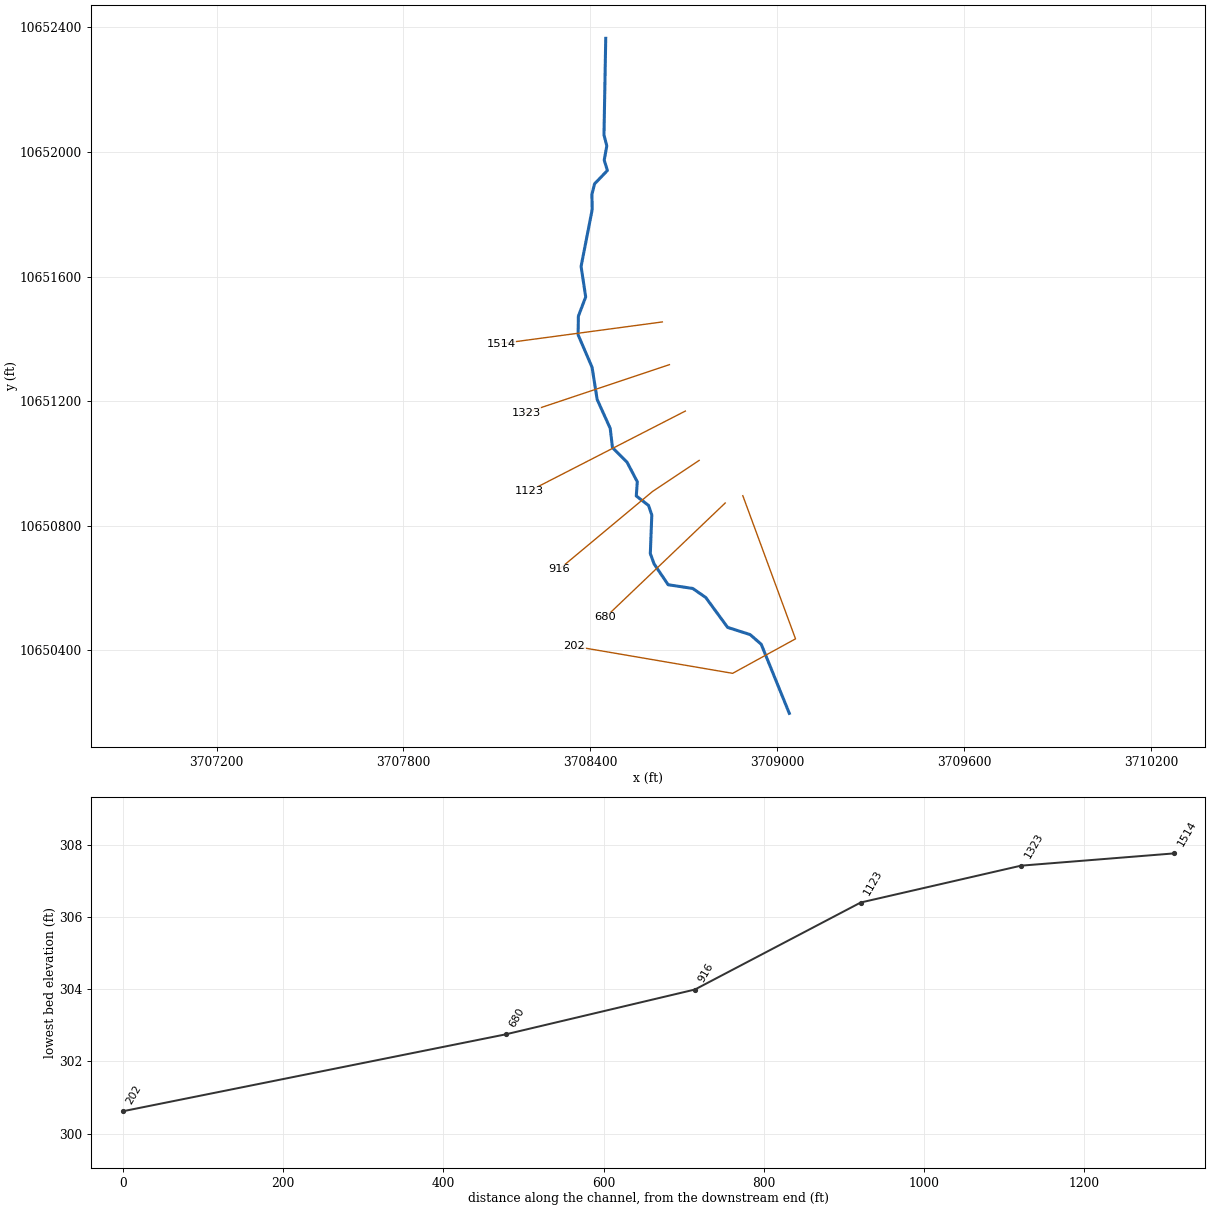
--- UNT 03317 IN LACR.prj (project) ---

Proj Title=UNT 03317 IN LACR Base Level Engineering
Current Plan=p01
Default Exp/Contr=0.3,0.1
English Units
Geom File=g01
Flow File=f01
Plan File=p01
BEGIN DESCRIPTION:
UNT 03317 IN LACR
END DESCRIPTION:

--- UNT 03317 IN LACR.p01 (plan) ---

Plan Title=Multiple Run
Short Identifier=Multiple
Geom File=g01
Flow File=f01
Subcritical Flow
K Sum by GR= 0
Std Step Tol= 0.01
Critical Tol= 0.01
Num of Std Step Trials= 20
Max Error Tol= 0.3
Flow Tol Ratio= 0.001
Split Flow NTrial= 30
Split Flow Tol= 0.02
Split Flow Ratio= 0.02
Log Output Level= 0
Friction Slope Method= 1
Unsteady Friction Slope Method= 2
Unsteady Bridges Friction Slope Method= 1
Parabolic Critical Depth
Global Vel Dist=  1 , 1 , 1
Global Log Level= 0
CheckData=True
Encroach Param= -1, 0, 0, 0
BEGIN DESCRIPTION:
Multiple Run
END DESCRIPTION:

--- UNT 03317 IN LACR.f01 (steady flow) ---

Flow Title=Multiple
Number of Profiles=7
Profile Names=10-year,25-year,50-year,1pct_min,100-year,1pct_plu,500-year
River Rch & RM= UNT 03317 IN LAC,Reach-1,1514
     216     275     321     277     375     507     510
Boundary for River Rch & Prof#=UNT 03317 IN LAC,Reach-1,1
Up Type=0
Dn Type=3
Dn Slope=0.005
Boundary for River Rch & Prof#=UNT 03317 IN LAC,Reach-1,2
Up Type=0
Dn Type=3
Dn Slope=0.005
Boundary for River Rch & Prof#=UNT 03317 IN LAC,Reach-1,3
Up Type=0
Dn Type=3
Dn Slope=0.005
Boundary for River Rch & Prof#=UNT 03317 IN LAC,Reach-1,4
Up Type=0
Dn Type=3
Dn Slope=0.005
Boundary for River Rch & Prof#=UNT 03317 IN LAC,Reach-1,5
Up Type=0
Dn Type=3
Dn Slope=0.005
Boundary for River Rch & Prof#=UNT 03317 IN LAC,Reach-1,6
Up Type=0
Dn Type=3
Dn Slope=0.005
Boundary for River Rch & Prof#=UNT 03317 IN LAC,Reach-1,7
Up Type=0
Dn Type=3
Dn Slope=0.005

--- UNT 03317 IN LACR.g01 (geometry) ---

Geom Title=Existing Conditions

River Reach=UNT 03317 IN LAC,Reach-1
Reach XY= 30
      3708449.61     10652365.19      3708444.00     10652055.00
      3708453.00     10652020.00      3708444.75     10651974.00
      3708455.00     10651941.00      3708413.75     10651898.00
      3708405.25     10651864.00      3708406.25     10651816.00
      3708370.50     10651633.00      3708385.25     10651535.00
      3708361.75     10651473.00      3708361.00     10651413.00
      3708405.75     10651309.00      3708422.00     10651206.00
      3708464.00     10651113.00      3708471.25     10651051.00
      3708518.25     10651004.00      3708550.95     10650941.51
      3708547.67     10650896.00      3708587.02     10650865.53
      3708597.50     10650835.00      3708592.75     10650711.00
      3708604.75     10650678.00      3708650.00     10650611.00
      3708729.00     10650599.00      3708770.75     10650570.00
      3708841.00     10650474.00      3708913.00     10650451.00
      3708948.75     10650420.00      3709039.00     10650198.00

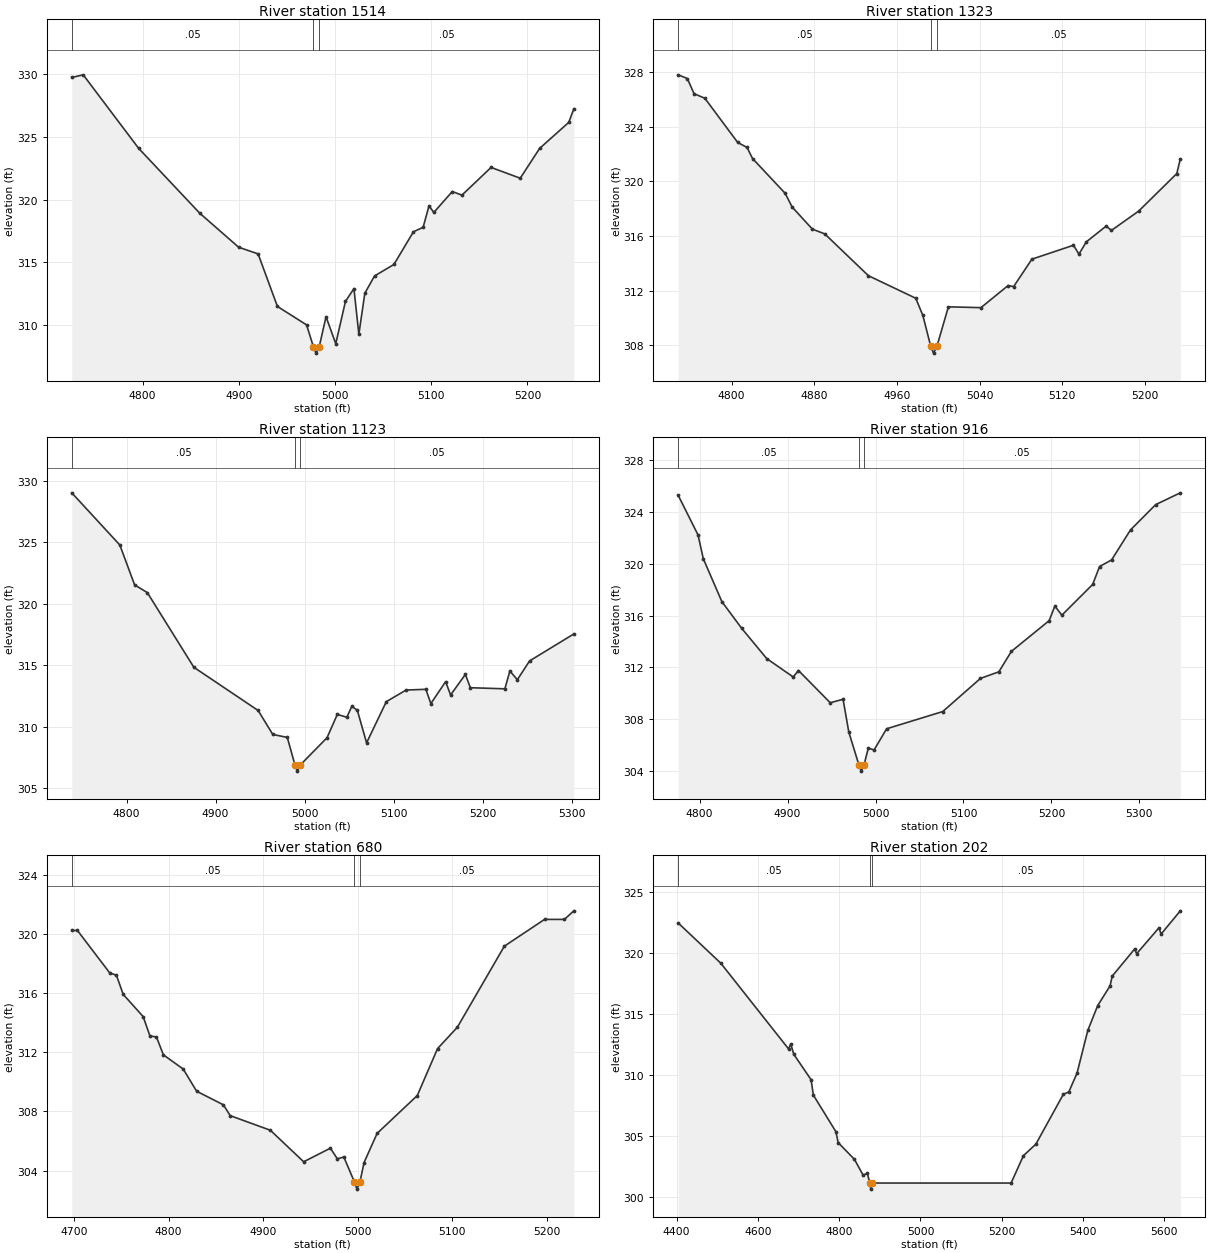
Type RM Length L Ch R = 1,1514,191,191,191
BEGIN DESCRIPTION:
UNT 03317 IN LACR 5.0
END DESCRIPTION:
XS GIS Cut Line= 2
      3708631.45     10651454.71      3708114.39     10651385.30
#Sta/Elev= 30
  4726.5  329.73  4738.4  329.94  4796.0  324.08  4859.5  318.91  4899.9  316.20
  4920.1  315.67  4940.2  311.48  4970.5  310.01  4977.6  308.26  4980.3  307.76
  4983.6  308.26  4990.7  310.66  5000.8  308.51  5010.9  311.89  5019.7  312.90
  5024.8  309.26  5031.0  312.53  5041.1  313.91  5061.3  314.83  5081.5  317.43
  5091.6  317.79  5097.7  319.50  5102.7  318.97  5121.9  320.64  5131.9  320.35
  5162.2  322.56  5192.5  321.70  5212.7  324.08  5242.9  326.15  5248.2  327.23
#Mann=3,-1,0
  4726.5    0.05       0  4977.6    0.03       0  4983.6    0.05       0
Bank Sta=4977.6,4983.6
Exp/Cntr=0.3,0.1

Type RM Length L Ch R = 1,1323,200,200,200
BEGIN DESCRIPTION:
UNT 03317 IN LACR 3.0
END DESCRIPTION:
XS GIS Cut Line= 2
      3708654.09     10651317.57      3708193.40     10651163.43
#Sta/Elev= 30
  4748.4  327.80  4757.2  327.53  4763.7  326.42  4774.2  326.08  4805.9  322.85
  4815.0  322.48  4820.3  321.67  4851.9  319.12  4858.6  318.12  4878.2  316.50
  4890.2  316.15  4932.4  313.09  4978.2  311.44  4985.1  310.18  4992.7  307.92
  4995.4  307.42  4998.7  307.92  5009.8  310.81  5041.3  310.75  5067.6  312.37
  5072.9  312.29  5090.6  314.30  5130.8  315.32  5136.1  314.67  5143.3  315.57
  5162.4  316.72  5167.6  316.41  5193.9  317.82  5230.8  320.57  5234.2  321.64
#Mann=3,-1,0
  4748.4    0.05       0  4992.7    0.03       0  4998.7    0.05       0
Bank Sta=4992.7,4998.7
Exp/Cntr=0.3,0.1

Type RM Length L Ch R = 1,1123,207,207,207
BEGIN DESCRIPTION:
Mapping XS 1f0bb6ac
END DESCRIPTION:
XS GIS Cut Line= 2
      3708705.14     10651168.57      3708203.13     10650911.07
#Sta/Elev= 30
  4738.4  329.02  4792.4  324.78  4809.0  321.54  4823.3  320.91  4875.6  314.84
  4947.8  311.33  4964.3  309.38  4980.6  309.14  4989.2  306.90  4991.9  306.40
  4995.2  306.90  5025.3  309.12  5036.8  311.01  5047.5  310.78  5053.1  311.67
  5059.3  311.34  5069.7  308.70  5091.9  312.05  5114.1  312.99  5136.3  313.05
  5141.9  311.89  5158.5  313.67  5164.1  312.59  5180.7  314.26  5186.3  313.18
  5225.1  313.09  5230.7  314.54  5239.1  313.83  5252.9  315.36  5302.6  317.55
#Mann=3,-1,0
  4738.4    0.05       0  4989.2    0.03       0  4995.2    0.05       0
Bank Sta=4989.2,4995.2
Exp/Cntr=0.3,0.1

Type RM Length L Ch R = 1,916,236,236,236
BEGIN DESCRIPTION:
UNT 03317 IN LACR 2.0
END DESCRIPTION:
XS GIS Cut Line= 3
      3708749.60     10651010.18      3708599.61     10650910.19
      3708299.60     10650660.18
#Sta/Elev= 30
  4775.7  325.28  4798.2  322.23  4804.2  320.39  4825.3  317.08  4847.8  315.02
  4876.3  312.68  4906.4  311.26  4912.4  311.76  4948.5  309.27  4963.1  309.54
  4969.6  307.01  4981.0  304.49  4983.7  303.99  4987.0  304.49  4991.8  305.77
  4998.3  305.62  5012.6  307.26  5076.4  308.59  5119.3  311.15  5140.2  311.66
  5154.5  313.24  5197.4  315.61  5203.9  316.74  5211.8  316.03  5246.9  318.41
  5254.7  319.79  5268.4  320.30  5289.9  322.62  5318.5  324.57  5346.5  325.48
#Mann=3,-1,0
  4775.7    0.05       0  4981.0    0.03       0  4987.0    0.05       0
Bank Sta=4981,4987
Exp/Cntr=0.3,0.1

Type RM Length L Ch R = 1,680,478,478,478
BEGIN DESCRIPTION:
Mapping XS 2b693684
END DESCRIPTION:
XS GIS Cut Line= 2
      3708833.23     10650873.46      3708449.10     10650506.70
#Sta/Elev= 30
  4697.5  320.24  4703.5  320.24  4737.8  317.36  4744.7  317.22  4751.9  315.92
  4773.0  314.42  4780.2  313.11  4787.1  313.04  4794.4  311.83  4815.4  310.87
  4829.6  309.37  4857.9  308.45  4865.1  307.72  4907.6  306.73  4942.8  304.60
  4971.1  305.52  4978.4  304.80  4985.3  304.92  4996.4  303.25  4999.2  302.75
  5002.4  303.25  5006.7  304.55  5020.5  306.52  5063.0  309.08  5084.4  312.25
  5105.4  313.70  5155.1  319.18  5197.6  320.99  5218.6  320.99  5228.6  321.57
#Mann=3,-1,0
  4697.5    0.05       0  4996.4    0.03       0  5002.4    0.05       0
Bank Sta=4996.4,5002.4
Exp/Cntr=0.3,0.1

Type RM Length L Ch R = 1,202,0,0,0
BEGIN DESCRIPTION:
UNT 03317 IN LACR 1.0
END DESCRIPTION:
XS GIS Cut Line= 4
      3708889.70     10650896.95      3709058.90     10650437.25
      3708857.08     10650326.57      3708349.27     10650413.38
#Sta/Elev= 30
  4404.0  322.47  4508.7  319.17  4675.5  312.13  4680.8  312.54  4688.3  311.69
  4730.9  309.60  4736.4  308.34  4792.0  305.33  4797.4  304.44  4837.4  303.07
  4858.8  301.77  4869.4  301.92  4875.1  301.12  4877.8  300.62  4881.1  301.12
  5222.9  301.12  5253.3  303.37  5283.8  304.31  5351.5  308.41  5364.9  308.60
  5385.2  310.15  5411.6  313.65  5436.0  315.69  5466.4  317.31  5471.7  318.11
  5526.7  320.33  5531.8  319.95  5586.8  322.08  5591.9  321.56  5639.2  323.47
#Mann=3,-1,0
  4404.0    0.05       0  4875.1   0.033       0  4881.1    0.05       0
Bank Sta=4875.1,4881.1
Exp/Cntr=0.3,0.1

Chan Stop Cuts=-1