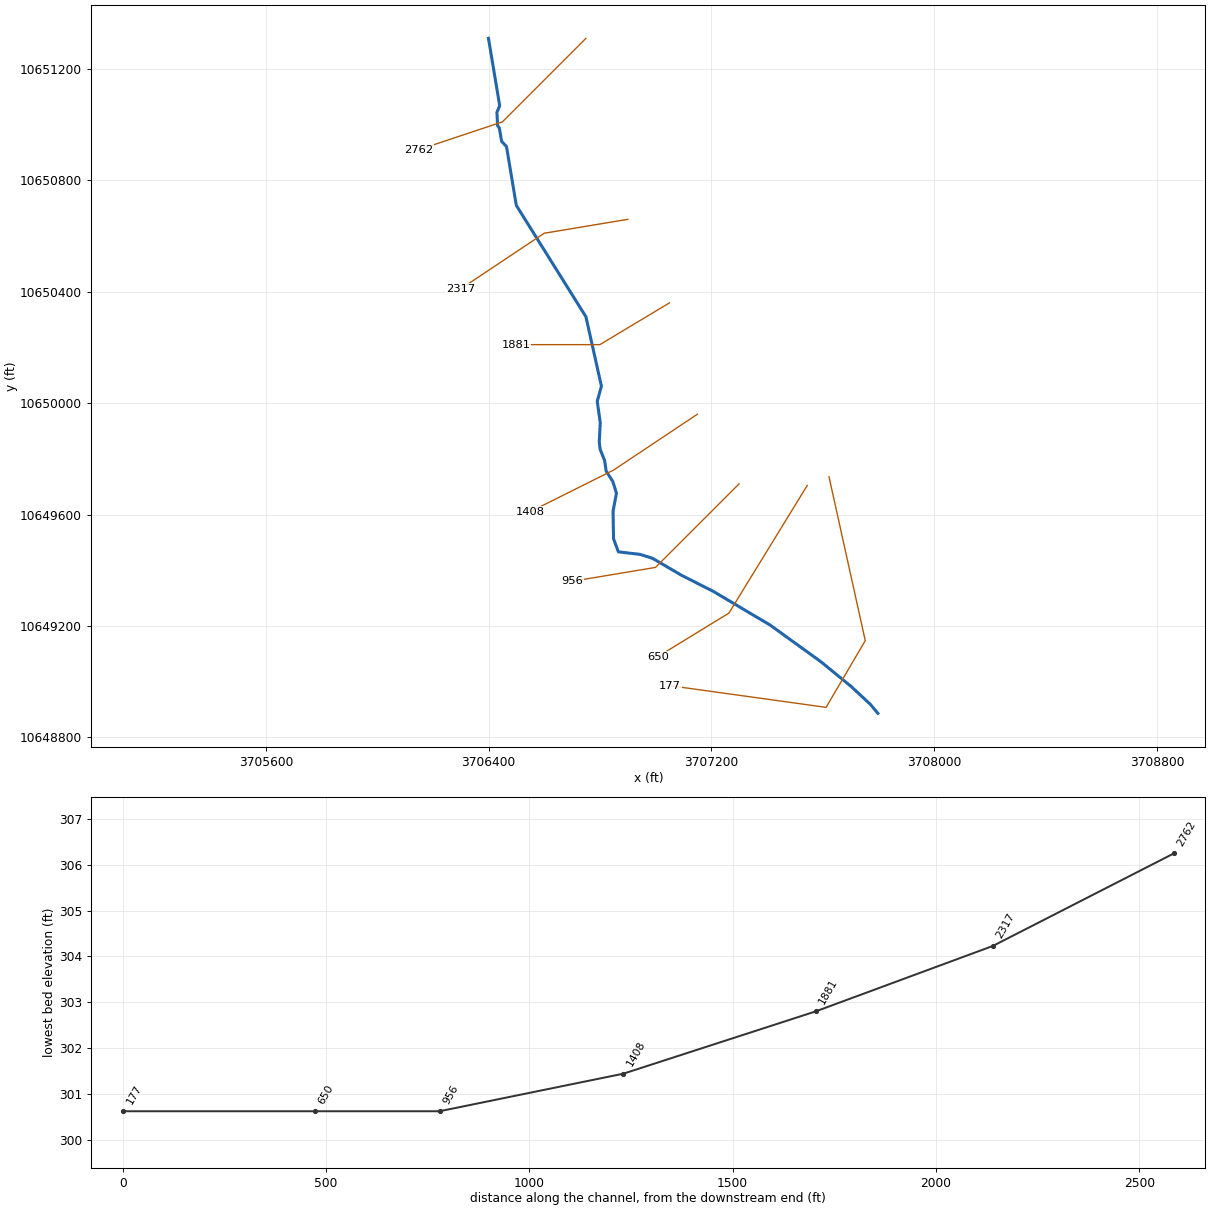
--- UNT 03318 IN LACR.prj (project) ---

Proj Title=UNT 03318 IN LACR Base Level Engineering
Current Plan=p01
Default Exp/Contr=0.3,0.1
English Units
Geom File=g01
Flow File=f01
Plan File=p01
BEGIN DESCRIPTION:
UNT 03318 IN LACR
END DESCRIPTION:

--- UNT 03318 IN LACR.p01 (plan) ---

Plan Title=Multiple Run
Short Identifier=Multiple
Geom File=g01
Flow File=f01
Subcritical Flow
K Sum by GR= 0
Std Step Tol= 0.01
Critical Tol= 0.01
Num of Std Step Trials= 20
Max Error Tol= 0.3
Flow Tol Ratio= 0.001
Split Flow NTrial= 30
Split Flow Tol= 0.02
Split Flow Ratio= 0.02
Log Output Level= 0
Friction Slope Method= 1
Unsteady Friction Slope Method= 2
Unsteady Bridges Friction Slope Method= 1
Parabolic Critical Depth
Global Vel Dist=  1 , 1 , 1
Global Log Level= 0
CheckData=True
Encroach Param= -1, 0, 0, 0
BEGIN DESCRIPTION:
Multiple Run
END DESCRIPTION:

--- UNT 03318 IN LACR.f01 (steady flow) ---

Flow Title=Multiple
Number of Profiles=7
Profile Names=10-year,25-year,50-year,1pct_min,100-year,1pct_plu,500-year
River Rch & RM= UNT 03318 IN LAC,Reach-1,2762
     453     605     729     646     874    1182    1261
Boundary for River Rch & Prof#=UNT 03318 IN LAC,Reach-1,1
Up Type=0
Dn Type=3
Dn Slope=0.005
Boundary for River Rch & Prof#=UNT 03318 IN LAC,Reach-1,2
Up Type=0
Dn Type=3
Dn Slope=0.005
Boundary for River Rch & Prof#=UNT 03318 IN LAC,Reach-1,3
Up Type=0
Dn Type=3
Dn Slope=0.005
Boundary for River Rch & Prof#=UNT 03318 IN LAC,Reach-1,4
Up Type=0
Dn Type=3
Dn Slope=0.005
Boundary for River Rch & Prof#=UNT 03318 IN LAC,Reach-1,5
Up Type=0
Dn Type=3
Dn Slope=0.005
Boundary for River Rch & Prof#=UNT 03318 IN LAC,Reach-1,6
Up Type=0
Dn Type=3
Dn Slope=0.005
Boundary for River Rch & Prof#=UNT 03318 IN LAC,Reach-1,7
Up Type=0
Dn Type=3
Dn Slope=0.005

--- UNT 03318 IN LACR.g01 (geometry) ---

Geom Title=Existing Conditions

River Reach=UNT 03318 IN LAC,Reach-1
Reach XY= 30
      3706399.61     10651310.19      3706439.91     10651068.37
      3706429.97     10651044.43      3706432.40     10650996.17
      3706438.65     10650988.18      3706446.98     10650939.92
      3706464.37     10650921.61      3706499.61     10650710.19
      3706749.61     10650310.19      3706805.25     10650061.00
      3706790.25     10650007.00      3706801.00     10649930.00
      3706797.50     10649860.00      3706800.75     10649834.00
      3706816.75     10649794.00      3706822.25     10649756.00
      3706846.00     10649719.00      3706859.25     10649677.00
      3706847.00     10649612.00      3706848.75     10649513.00
      3706866.25     10649466.00      3706944.25     10649457.00
      3706988.50     10649443.00      3707092.75     10649382.00
      3707207.25     10649324.00      3707411.25     10649203.00
      3707592.75     10649072.00      3707700.50     10648984.00
      3707771.50     10648918.00      3707798.00     10648886.00

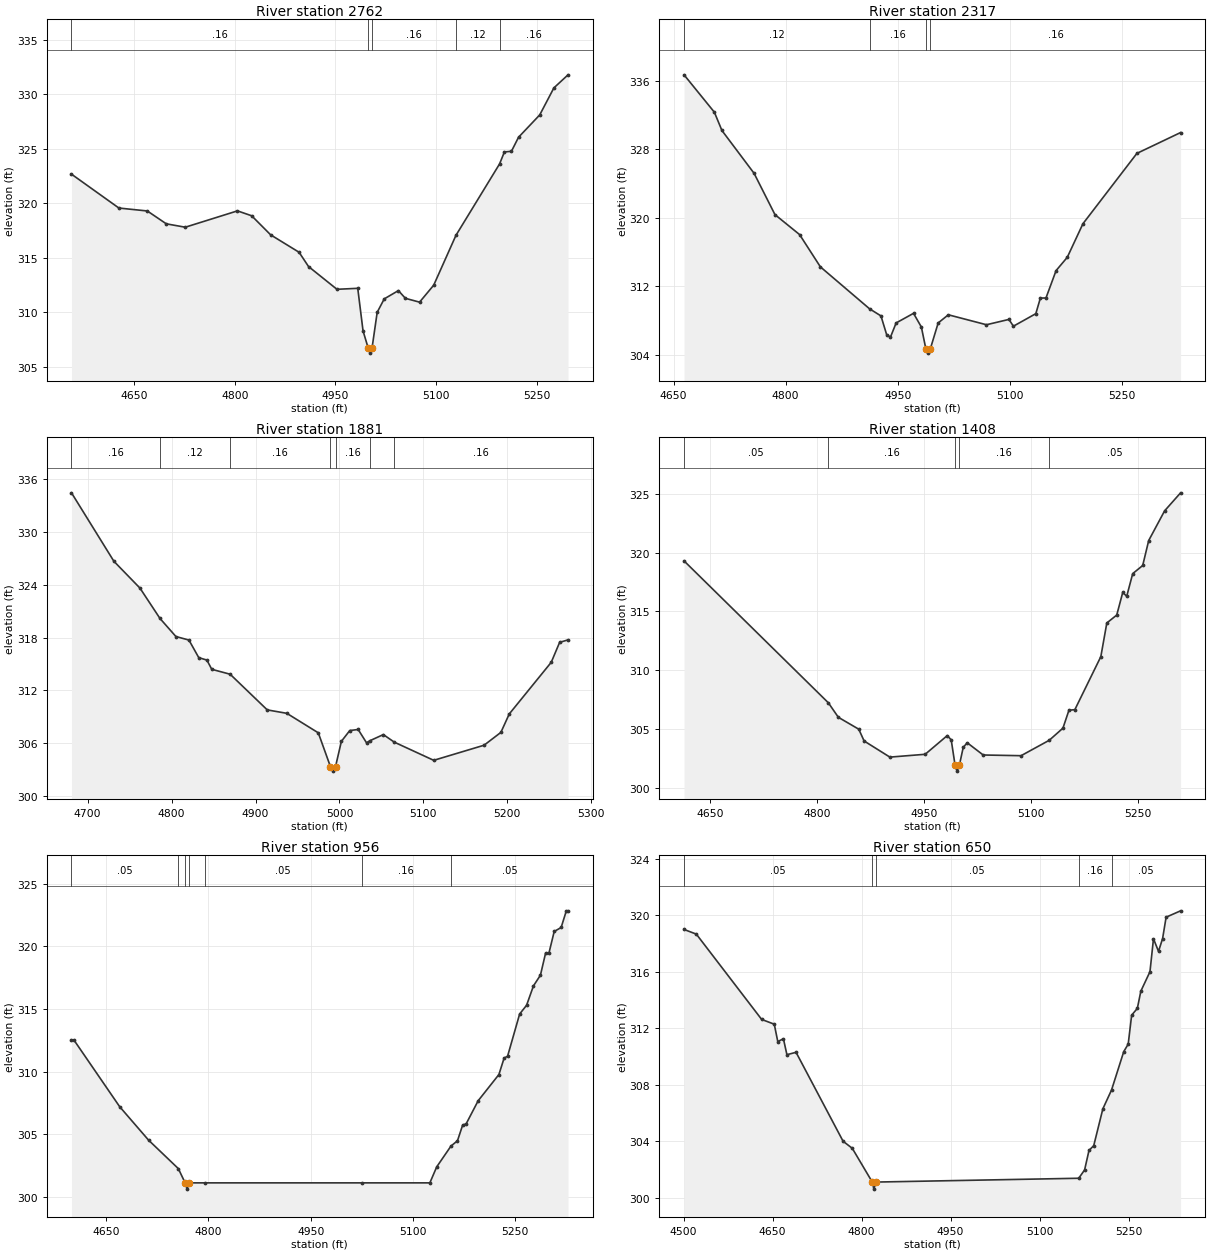
Type RM Length L Ch R = 1,2762,445,445,445
BEGIN DESCRIPTION:
UNT 03318 IN LACR 6.0
END DESCRIPTION:
XS GIS Cut Line= 3
      3706749.59     10651310.17      3706449.61     10651010.19
      3706149.57     10650910.18
#Sta/Elev= 30
  4556.4  322.68  4627.1  319.57  4669.5  319.30  4697.8  318.12  4726.1  317.81
  4803.9  319.31  4825.1  318.86  4853.4  317.11  4895.8  315.51  4909.9  314.20
  4952.3  312.11  4983.3  312.20  4991.2  308.29  4998.7  306.75  5001.5  306.25
  5004.7  306.75  5012.3  310.00  5022.8  311.23  5043.9  311.99  5054.4  311.28
  5075.5  310.93  5096.6  312.49  5129.8  317.07  5194.8  323.62  5202.0  324.72
  5212.5  324.78  5223.1  326.07  5254.7  328.12  5275.8  330.60  5296.9  331.80
#Mann=5,-1,0
  4556.4    0.16       0  4998.7    0.07       0  5004.7    0.16       0
  5129.8    0.12       0  5194.8    0.16       0
Bank Sta=4998.7,5004.7
Exp/Cntr=0.3,0.1

Type RM Length L Ch R = 1,2317,436,436,436
BEGIN DESCRIPTION:
UNT 03318 IN LACR 5.0
END DESCRIPTION:
XS GIS Cut Line= 3
      3706899.66     10650660.20      3706599.61     10650610.19
      3706299.64     10650410.21
#Sta/Elev= 30
  4664.0  336.68  4704.6  332.32  4714.7  330.19  4757.8  325.19  4785.7  320.38
  4818.7  318.05  4846.5  314.29  4912.3  309.40  4927.6  308.57  4935.2  306.39
  4940.3  306.09  4947.9  307.75  4971.2  308.87  4981.7  307.27  4987.7  304.73
  4990.5  304.23  4993.7  304.73  5004.2  307.75  5017.8  308.70  5068.8  307.54
  5098.9  308.16  5104.9  307.37  5134.9  308.83  5141.0  310.65  5148.5  310.66
  5162.0  313.85  5177.0  315.40  5198.0  319.32  5270.2  327.52  5328.7  329.95
#Mann=4,-1,0
  4664.0    0.12       0  4912.3    0.16       0  4987.7    0.07       0
  4993.7    0.16       0
Bank Sta=4987.7,4993.7
Exp/Cntr=0.3,0.1

Type RM Length L Ch R = 1,1881,473,473,473
BEGIN DESCRIPTION:
UNT 03318 IN LACR 4.0
END DESCRIPTION:
XS GIS Cut Line= 3
      3707049.59     10650360.18      3706799.61     10650210.19
      3706499.64     10650210.19
#Sta/Elev= 30
  4680.8  334.48  4731.3  326.69  4762.4  323.63  4786.2  320.18  4805.2  318.12
  4820.7  317.72  4832.4  315.72  4842.1  315.44  4847.9  314.39  4869.8  313.83
  4914.0  309.77  4937.3  309.38  4974.8  307.16  4989.3  303.30  4992.1  302.80
  4995.3  303.30  5002.3  306.19  5012.3  307.42  5022.3  307.54  5032.3  306.02
  5036.0  306.25  5052.3  306.96  5065.3  306.10  5112.3  304.03  5172.3  305.75
  5192.3  307.21  5202.3  309.31  5252.3  315.19  5262.3  317.46  5272.3  317.74
#Mann=7,-1,0
  4680.8    0.16       0  4786.2    0.12       0  4869.8    0.16       0
  4989.3    0.07       0  4995.3    0.16       0  5036.0    0.12       0
  5065.3    0.16       0
Bank Sta=4989.3,4995.3
Exp/Cntr=0.3,0.1

Type RM Length L Ch R = 1,1408,452,452,452
BEGIN DESCRIPTION:
UNT 03318 IN LACR 3.0
END DESCRIPTION:
XS GIS Cut Line= 3
      3707149.62     10649960.20      3706849.61     10649760.19
      3706549.59     10649610.18
#Sta/Elev= 30
  4614.0  319.29  4816.3  307.24  4830.3  306.01  4858.9  305.00  4866.4  304.00
  4902.5  302.63  4952.0  302.87  4983.0  304.46  4988.5  304.09  4993.9  301.94
  4996.7  301.44  4999.9  301.94  5005.3  303.45  5010.9  303.85  5033.3  302.81
  5086.4  302.75  5125.9  304.06  5145.1  305.09  5153.5  306.61  5161.8  306.66
  5198.2  311.16  5206.6  314.02  5220.5  314.69  5228.9  316.61  5234.5  316.29
  5242.9  318.21  5256.9  318.90  5265.3  321.02  5287.6  323.54  5310.0  325.07
#Mann=5,-1,0
  4614.0    0.05       0  4816.3    0.16       0  4993.9    0.07       0
  4999.9    0.16       0  5125.9    0.05       0
Bank Sta=4993.9,4999.9
Exp/Cntr=0.3,0.1

Type RM Length L Ch R = 1,956,306,306,306
BEGIN DESCRIPTION:
UNT 03318 IN LACR 2.0
END DESCRIPTION:
XS GIS Cut Line= 3
      3707299.62     10649710.20      3706999.61     10649410.19
      3706699.62     10649360.19
#Sta/Elev= 30
  4599.2  312.53  4602.7  312.53  4669.9  307.20  4712.3  304.53  4755.9  302.26
  4765.9  301.12  4768.7  300.62  4771.9  301.12  4794.6  301.12  5024.9  301.12
  5124.9  301.12  5135.0  302.40  5155.9  304.06  5165.4  304.48  5173.0  305.73
  5178.1  305.83  5195.8  307.68  5226.2  309.77  5233.8  311.08  5238.9  311.23
  5256.6  314.60  5266.8  315.30  5276.9  316.85  5287.1  317.70  5294.7  319.47
  5299.7  319.49  5307.3  321.19  5317.5  321.51  5325.1  322.84  5327.6  322.84
#Mann=7,-1,0
  4599.2    0.05       0  4755.9    0.16       0  4765.9   0.033       0
  4771.9    0.16       0  4794.6    0.05       0  5024.9    0.16       0
  5155.9    0.05       0
Bank Sta=4765.9,4771.9
Exp/Cntr=0.3,0.1

Type RM Length L Ch R = 1,650,473,473,473
BEGIN DESCRIPTION:
Mapping XS 99f2a4aa
END DESCRIPTION:
XS GIS Cut Line= 3
      3707544.38     10649704.49      3707263.11     10649246.13
      3707007.92     10649089.89
#Sta/Elev= 30
  4500.7  319.01  4521.4  318.68  4631.5  312.64  4652.8  312.30  4658.7  311.07
  4668.2  311.27  4674.1  310.14  4689.5  310.31  4768.8  304.01  4784.3  303.51
  4818.0  301.12  4820.7  300.62  4824.0  301.12  5166.0  301.39  5175.9  301.98
  5183.3  303.36  5191.3  303.70  5206.7  306.31  5221.3  307.64  5241.9  310.36
  5249.4  310.89  5255.2  312.94  5264.8  313.42  5270.7  314.64  5286.1  316.02
  5292.0  318.35  5300.5  317.46  5307.4  318.37  5313.3  319.88  5337.7  320.33
#Mann=5,-1,0
  4500.7    0.05       0  4818.0   0.033       0  4824.0    0.05       0
  5166.0    0.16       0  5221.3    0.05       0
Bank Sta=4818,4824
Exp/Cntr=0.3,0.1

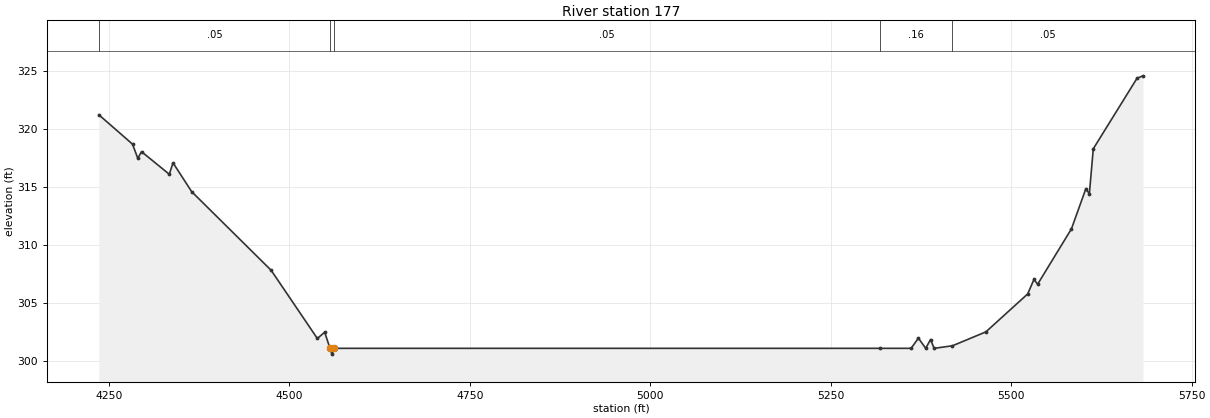
Type RM Length L Ch R = 1,177,0,0,0
BEGIN DESCRIPTION:
UNT 03318 IN LACR 1.0
END DESCRIPTION:
XS GIS Cut Line= 4
      3707622.48     10649735.73      3707752.70     10649147.17
      3707612.07     10648907.59      3707051.45     10648985.46
#Sta/Elev= 30
  4235.9  321.26  4282.5  318.73  4289.8  317.51  4295.0  318.08  4333.5  316.13
  4338.6  317.12  4364.5  314.63  4474.6  307.85  4538.6  301.97  4548.8  302.51
  4556.1  301.12  4558.8  300.62  4562.1  301.12  5318.1  301.12  5361.3  301.12
  5371.4  302.00  5381.5  301.12  5388.2  301.88  5393.2  301.12  5418.6  301.34
  5464.9  302.54  5522.8  305.81  5531.5  307.06  5536.6  306.65  5583.4  311.42
  5603.2  314.85  5608.3  314.47  5613.7  318.33  5674.3  324.41  5682.5  324.62
#Mann=5,-1,0
  4235.9    0.05       0  4556.1   0.033       0  4562.1    0.05       0
  5318.1    0.16       0  5418.6    0.05       0
Bank Sta=4556.1,4562.1
Exp/Cntr=0.3,0.1

Chan Stop Cuts=-1