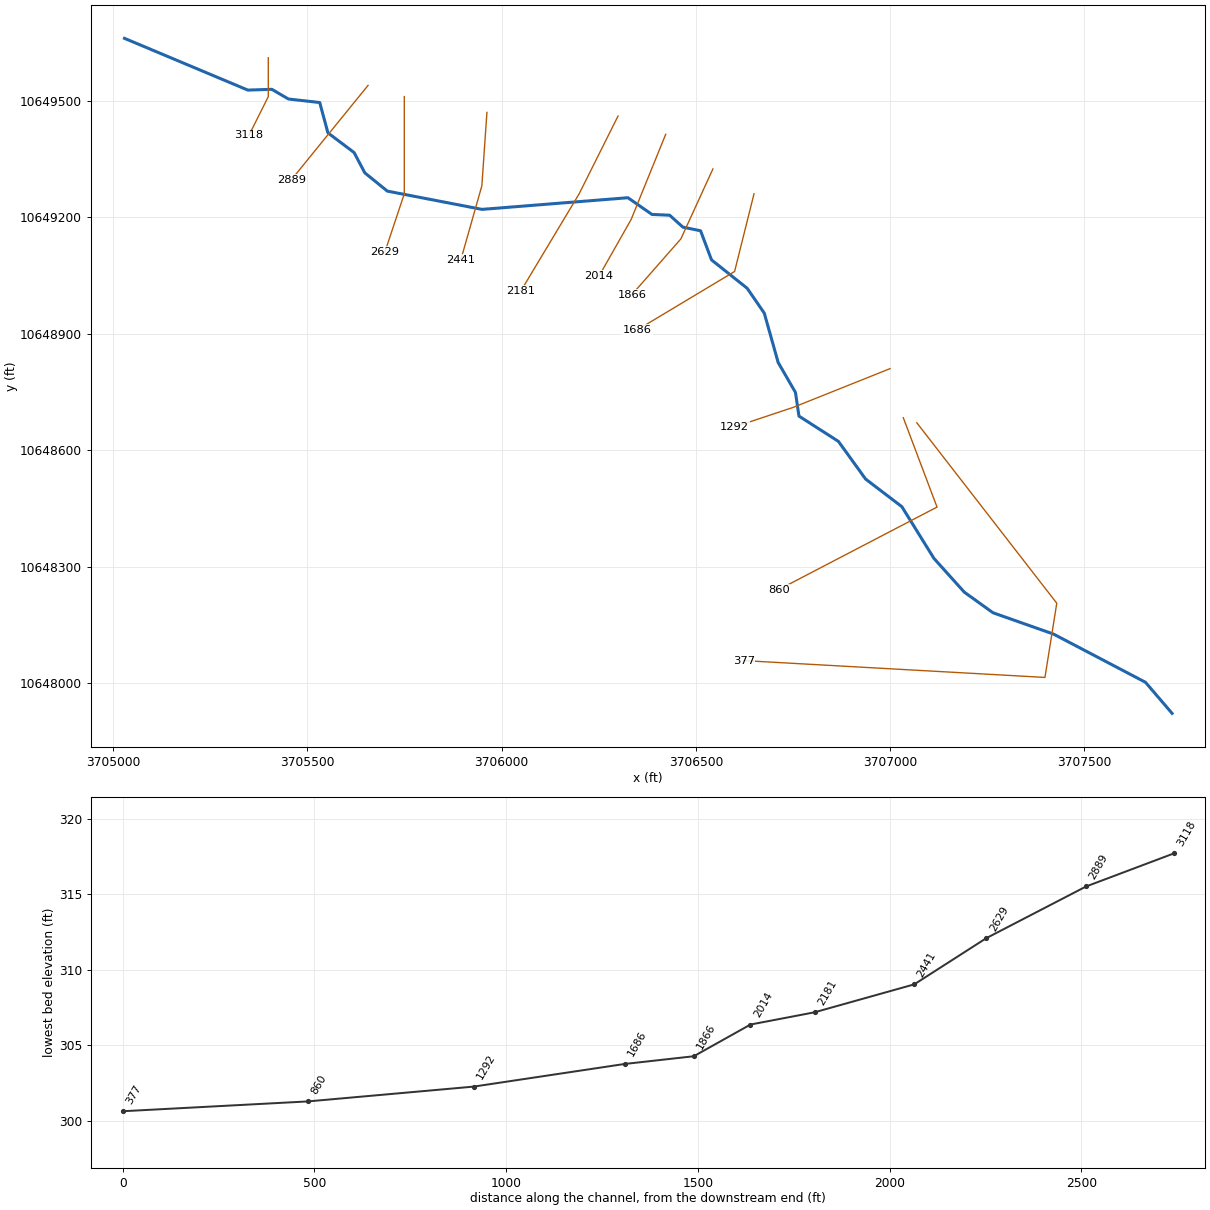
--- UNT 03320 IN LACR.prj (project) ---

Proj Title=UNT 03320 IN LACR Base Level Engineering
Current Plan=p01
Default Exp/Contr=0.3,0.1
English Units
Geom File=g01
Flow File=f01
Plan File=p01
Y Axis Title=Elevation
X Axis Title(PF)=Main Channel Distance
X Axis Title(XS)=Station
BEGIN DESCRIPTION:
UNT 03320 IN LACR
END DESCRIPTION:
DSS Export Rating Curves= 0
DSS Export Rating Curve Sorted= 0
DSS Export Volume Flow Curves= 0
DXF OffsetX= 0
DXF OffsetY= 0
DXF ScaleX= 1
DXF ScaleY= 10

--- UNT 03320 IN LACR.p01 (plan) ---

Plan Title=Multiple Run
Short Identifier=Multiple
Geom File=g01
Flow File=f01
Subcritical Flow
K Sum by GR= 0
Std Step Tol= 0.01
Critical Tol= 0.01
Num of Std Step Trials= 20
Max Error Tol= 0.3
Flow Tol Ratio= 0.001
Split Flow NTrial= 30
Split Flow Tol= 0.02
Split Flow Ratio= 0.02
Log Output Level= 0
Friction Slope Method= 1
Unsteady Friction Slope Method= 2
Unsteady Bridges Friction Slope Method= 1
Parabolic Critical Depth
Global Vel Dist=  1 , 1 , 1
Global Log Level= 0
CheckData=True
Encroach Param= -1, 0, 0, 0
BEGIN DESCRIPTION:
Multiple Run
END DESCRIPTION:

--- UNT 03320 IN LACR.f01 (steady flow) ---

Flow Title=Multiple
Program Version=4.10
Number of Profiles= 7
Profile Names=10-year,25-year,50-year,1pct_min,100-year,1pct_plu,500-year
River Rch & RM=UNT 03320 IN LAC,Reach-1         ,3118
     256     329     385     333     450     609     615
Boundary for River Rch & Prof#=UNT 03320 IN LAC,Reach-1         , 1
Up Type= 0
Dn Type= 3
Dn Slope=0.001
Boundary for River Rch & Prof#=UNT 03320 IN LAC,Reach-1         , 2
Up Type= 0
Dn Type= 3
Dn Slope=0.001
Boundary for River Rch & Prof#=UNT 03320 IN LAC,Reach-1         , 3
Up Type= 0
Dn Type= 3
Dn Slope=0.001
Boundary for River Rch & Prof#=UNT 03320 IN LAC,Reach-1         , 4
Up Type= 0
Dn Type= 3
Dn Slope=0.001
Boundary for River Rch & Prof#=UNT 03320 IN LAC,Reach-1         , 5
Up Type= 0
Dn Type= 3
Dn Slope=0.001
Boundary for River Rch & Prof#=UNT 03320 IN LAC,Reach-1         , 6
Up Type= 0
Dn Type= 3
Dn Slope=0.001
Boundary for River Rch & Prof#=UNT 03320 IN LAC,Reach-1         , 7
Up Type= 0
Dn Type= 3
Dn Slope=0.001
DSS Import GetInterval= 0
DSS Import GetPeak= 0
DSS Import FillOption= 0

--- UNT 03320 IN LACR.g01 (geometry) ---

Geom Title=Existing Conditions
Program Version=4.10

River Reach=UNT 03320 IN LAC,Reach-1
Reach XY= 30
      3705029.52     10649660.19        3705347.       10649527.
      3705408.75       10649529.       3705451.5       10649504.
        3705532.       10649495.        3705553.       10649417.
      3705620.39     10649366.28        3705648.       10649314.
        3705706.       10649267.      3705949.75       10649220.
        3706325.       10649250.        3706387.       10649207.
       3706432.5       10649205.      3706466.57     10649174.26
        3706512.       10649165.      3706540.25       10649090.
        3706632.       10649017.        3706676.       10648953.
      3706711.75       10648826.      3706756.25       10648749.
      3706765.25       10648688.      3706866.75       10648623.
      3706936.75       10648526.        3707030.       10648455.
       3707112.5       10648322.      3707190.75       10648235.
       3707264.5       10648182.       3707420.5       10648127.
        3707657.       10648003.       3707725.5       10647923.

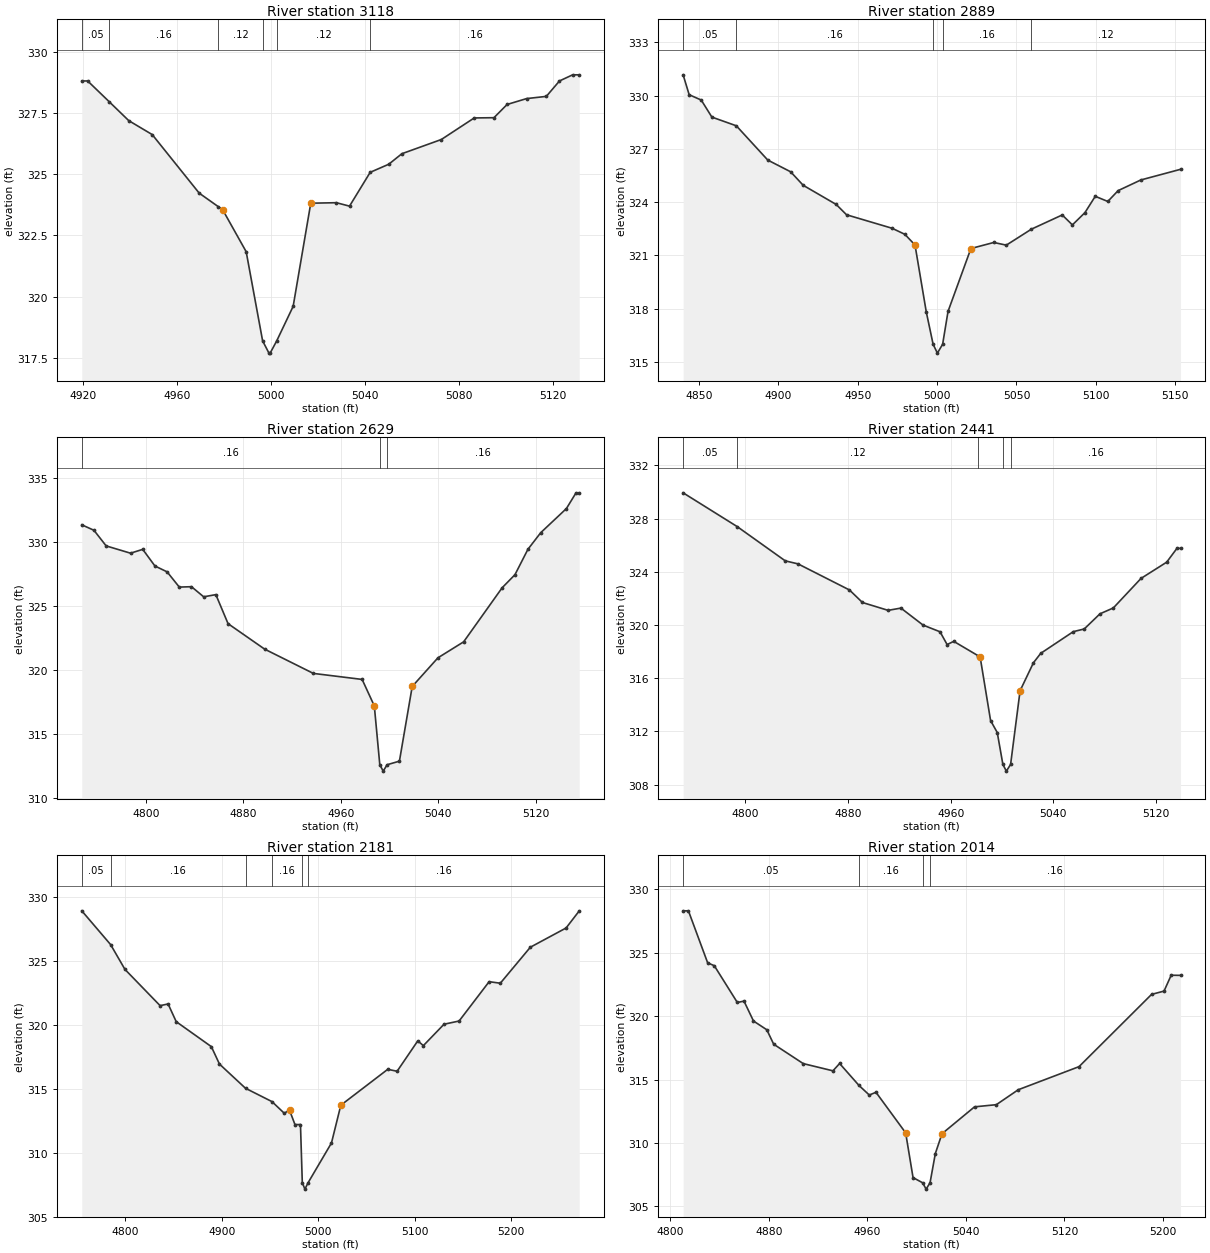
Type RM Length L Ch R = 1 ,3118    ,229,229,229
BEGIN DESCRIPTION:
UNT 03320 IN LACR 6.0
END DESCRIPTION:
XS GIS Cut Line= 3
      3705399.61     10649610.18      3705399.61     10649510.19
      3705349.61     10649410.19
#Sta/Elev= 29
  4919.3   328.8  4921.8   328.8    4931  327.95  4939.3  327.18  4949.3  326.61
  4969.3  324.22  4977.4  323.67  4979.3  323.54  4989.3  321.83  4996.3  318.19
    4999  317.69  4999.5  317.69  5002.3  318.19  5009.3   319.6  5016.8  323.81
  5027.7  323.83  5033.3  323.69  5042.1  325.07    5050   325.4  5055.6  325.83
  5072.4  326.41  5086.4  327.29  5094.8   327.3  5100.4  327.84  5108.7  328.08
  5117.1  328.17  5122.7   328.8  5128.3  329.05  5131.1  329.05
#Mann= 6 ,-1 , 0
  4919.3     .05       0    4931     .16       0  4977.4     .12       0
  4996.3     .07       0  5002.3     .12       0  5042.1     .16       0
Bank Sta=4979.3,5016.8
XS Rating Curve= 0 ,0
Exp/Cntr=0.3,0.1

Type RM Length L Ch R = 1 ,2889    ,260,260,260
BEGIN DESCRIPTION:
Mapping XS a6620967
END DESCRIPTION:
XS GIS Cut Line= 2
      3705656.25     10649539.02      3705458.75     10649295.94
#Sta/Elev= 30
  4840.1  331.17  4843.9  330.05  4851.5  329.75  4858.2  328.79  4873.6   328.3
  4893.4  326.37  4907.8  325.71  4915.7  324.95  4936.5  323.87    4943  323.29
  4971.7  322.53  4979.7  322.19  4986.1  321.59  4993.2  317.82  4997.5     316
  5000.2   315.5  5003.5     316  5006.9  317.85  5021.3  321.39  5035.7  321.73
  5043.6  321.58  5059.4  322.48  5078.8  323.28  5085.2  322.72  5093.1  323.41
  5099.6  324.33  5107.5  324.04    5114  324.65  5128.3  325.25  5153.3  325.85
#Mann= 5 ,-1 , 0
  4840.1     .05       0  4873.6     .16       0  4997.5     .07       0
  5003.5     .16       0  5059.4     .12       0
Bank Sta=4986.1,5021.3
XS Rating Curve= 0 ,0
Exp/Cntr=0.3,0.1

Type RM Length L Ch R = 1 ,2629    ,188,188,188
BEGIN DESCRIPTION:
UNT 03320 IN LACR 5.0
END DESCRIPTION:
XS GIS Cut Line= 3
      3705749.61     10649510.22      3705749.61     10649260.19
      3705699.62     10649110.23
#Sta/Elev= 30
  4747.4  331.34  4757.4  330.91  4767.4  329.69  4787.4  329.12  4797.4  329.42
  4807.4  328.12  4817.4  327.66  4827.4  326.47  4837.4   326.5  4847.4  325.71
  4857.4  325.88  4867.4  323.61  4897.4  321.62  4937.4  319.72  4977.4  319.25
  4987.4  317.18  4991.9  312.58  4994.7  312.08  4997.9  312.58    5008  312.86
  5018.5   318.7  5039.6  320.94  5060.7  322.19  5092.3  326.42  5102.8  327.44
  5113.4  329.42  5123.9  330.72    5145  332.61  5152.9  333.84  5155.5  333.84
#Mann= 3 ,-1 , 0
  4747.4     .16       0  4991.9     .07       0  4997.9     .16       0
Bank Sta=4987.4,5018.5
XS Rating Curve= 0 ,0
Exp/Cntr=0.3,0.1

Type RM Length L Ch R = 1 ,2441    ,260,260,260
BEGIN DESCRIPTION:
Mapping XS 0d9fb7f2
END DESCRIPTION:
XS GIS Cut Line= 3
      3705962.23     10649469.61      3705949.21     10649280.76
      3705894.96     10649089.81
#Sta/Elev= 30
  4751.4  329.93  4793.6  327.39    4831  324.82    4841  324.59  4881.1  322.63
  4891.2  321.69  4911.2   321.1  4921.2  321.27  4938.5  319.99  4951.7  319.49
  4957.2  318.53  4962.4  318.77  4981.2   317.7  4982.9  317.63  4991.1  312.82
  4996.3  311.92  5000.7  309.52  5003.4  309.02  5006.7  309.52  5014.1  315.06
  5024.5  317.16  5030.2  317.87  5055.6   319.5  5064.1   319.7  5076.4  320.84
  5086.8  321.28  5108.4   323.5  5128.4  324.72  5136.4  325.76  5139.2  325.76
#Mann= 5 ,-1 , 0
  4751.4     .05       0  4793.6     .12       0  4981.2     .16       0
  5000.7     .07       0  5006.7     .16       0
Bank Sta=4982.9,5014.1
XS Rating Curve= 0 ,0
Exp/Cntr=0.3,0.1

Type RM Length L Ch R = 1 ,2181    ,167,167,167
BEGIN DESCRIPTION:
UNT 03320 IN LACR 4.0
END DESCRIPTION:
XS GIS Cut Line= 3
      3706299.61     10649460.19      3706199.61     10649260.19
      3706049.59     10649010.15
#Sta/Elev= 30
  4755.1  328.89    4785  326.25  4799.8  324.32  4836.2  321.49  4844.5  321.62
  4852.9  320.24  4889.3  318.29  4897.7  316.93  4924.7  315.04  4952.1     314
  4964.7   313.1  4970.3  313.32  4975.9  312.21  4981.6  312.21  4983.5  307.67
  4986.2  307.17  4989.5  307.67  5013.7  310.77  5023.4  313.72    5072  316.52
  5081.7  316.37  5103.1  318.74  5108.9  318.37  5130.3  320.04  5145.9  320.29
    5177  323.36  5188.6  323.24  5219.7  326.05  5256.7  327.55  5270.3  328.88
#Mann= 6 ,-1 , 0
  4755.1     .05       0    4785     .16       0  4924.7     .12       0
  4952.1     .16       0  4983.5     .07       0  4989.5     .16       0
Bank Sta=4970.3,5023.4
XS Rating Curve= 0 ,0
Exp/Cntr=0.3,0.1

Type RM Length L Ch R = 1 ,2014    ,148,148,148
BEGIN DESCRIPTION:
Mapping XS 3b523309
END DESCRIPTION:
XS GIS Cut Line= 3
      3706422.29     10649413.12      3706333.32     10649193.95
      3706250.85     10649048.55
#Sta/Elev= 30
  4810.5  328.31  4814.8  328.31  4830.4  324.21  4835.8  323.98  4854.5  321.08
  4859.9  321.19  4867.6  319.62  4878.4  318.93    4884  317.79    4908  316.26
  4932.1  315.69  4937.5  316.27  4953.2  314.54  4961.6  313.78    4967     314
  4991.1   310.8  4997.1  307.27  5004.9  306.86  5007.7  306.36  5010.9  306.86
  5015.2  309.17  5020.6  310.73    5047  312.85  5064.7  313.02  5082.5   314.2
  5131.8  316.02  5190.7  321.72  5200.8  321.98  5206.6  323.23  5214.2  323.22
#Mann= 4 ,-1 , 0
  4810.5     .05       0  4953.2     .16       0  5004.9     .07       0
  5010.9     .16       0
Bank Sta=4991.1,5020.6
XS Rating Curve= 0 ,0
Exp/Cntr=0.3,0.1

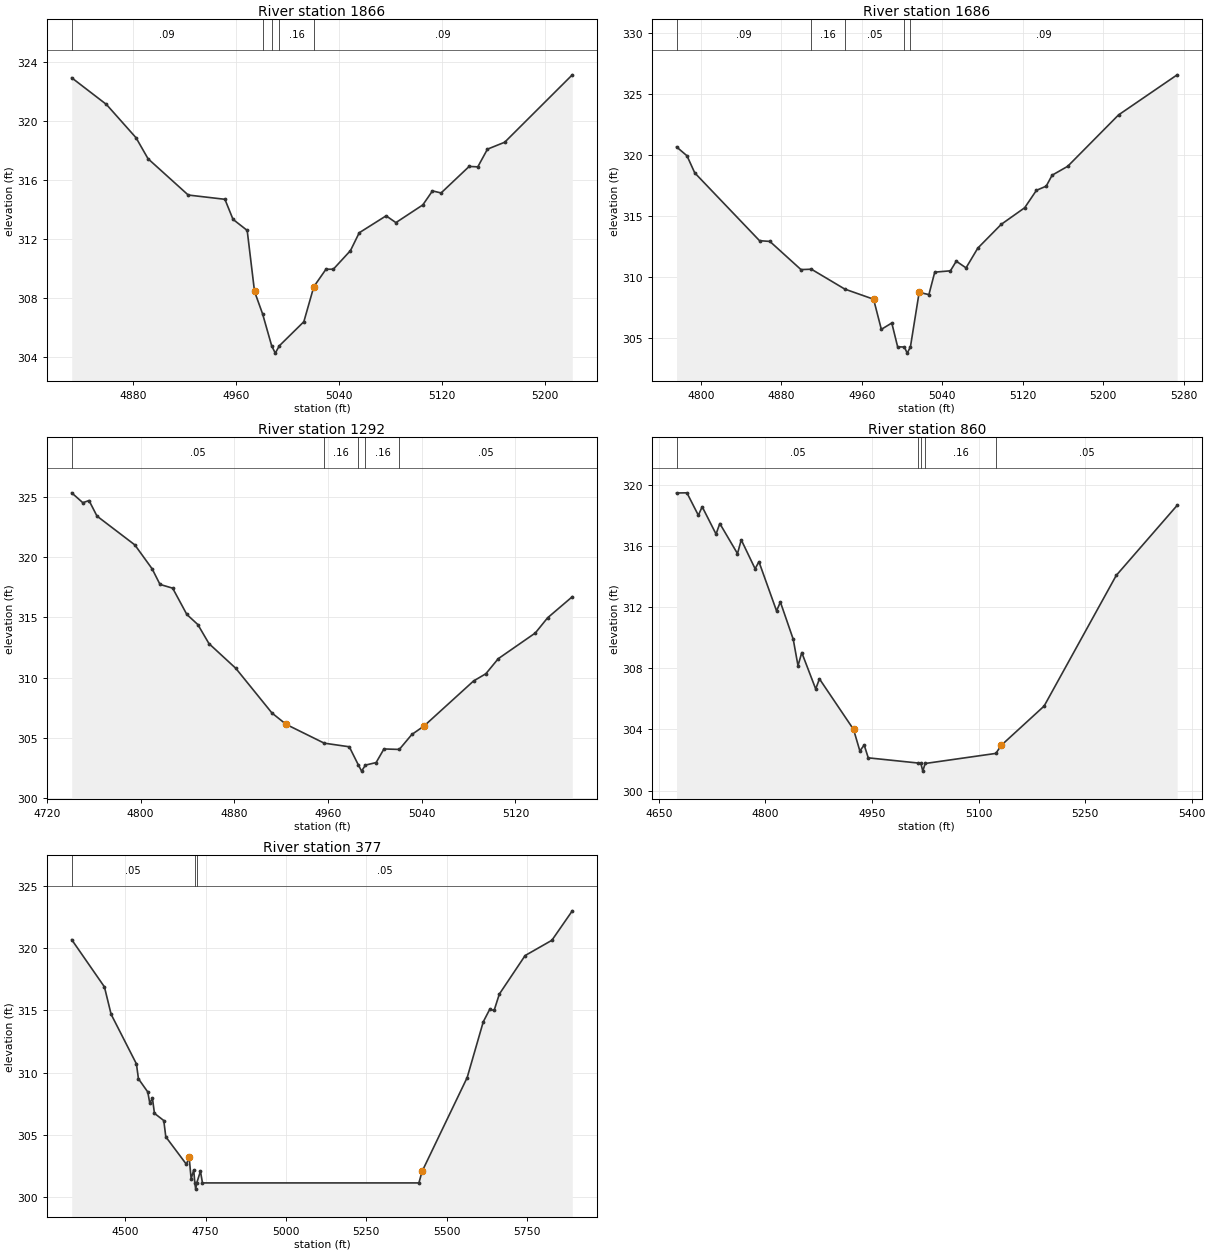
Type RM Length L Ch R = 1 ,1866    ,180,180,180
BEGIN DESCRIPTION:
Mapping XS 9cb0a3bb
END DESCRIPTION:
XS GIS Cut Line= 3
      3706543.82     10649324.14      3706461.36     10649144.04
      3706335.47     10649000.78
#Sta/Elev= 30
  4832.2  322.93  4859.2  321.12  4882.2  318.86  4891.5  317.44  4922.7  314.98
  4951.2  314.69  4957.5  313.33  4968.5  312.58  4974.2  308.44  4980.5  306.91
  4987.5  304.76  4990.3  304.26  4993.5  304.76  5012.5  306.39  5020.2  308.75
  5020.6  308.81  5029.7  309.95  5035.4  309.95  5048.7  311.21  5055.5  312.42
  5076.4  313.57    5084  313.11  5104.9  314.31  5112.4  315.26  5119.1  315.12
  5140.9  316.92  5147.6  316.89  5155.1  318.09  5168.5  318.56    5221  323.13
#Mann= 5 ,-1 , 0
  4832.2     .09       0  4980.5     .16       0  4987.5     .07       0
  4993.5     .16       0  5020.6     .09       0
Bank Sta=4974.2,5020.2
XS Rating Curve= 0 ,0
Exp/Cntr=0.3,0.1

Type RM Length L Ch R = 1 ,1686    ,394,394,394
BEGIN DESCRIPTION:
UNT 03320 IN LACR 3.0
END DESCRIPTION:
XS GIS Cut Line= 3
      3706649.62     10649260.23      3706599.61     10649060.19
      3706349.65     10648910.21
#Sta/Elev= 30
  4775.9  320.66  4786.3  319.93    4794  318.53  4858.4  312.97  4868.7  312.91
  4899.6   310.6    4910  310.63  4943.2     309  4971.8  308.17  4979.5   305.7
  4989.9  306.22  4995.7  304.27  5002.4  304.25  5005.2  303.75  5008.4  304.25
  5017.1  308.73  5026.8  308.55  5032.6  310.39  5048.2   310.5    5054  311.29
  5063.7  310.74  5075.4  312.36  5098.7  314.31    5122  315.67  5133.7   317.1
  5143.4  317.44  5149.3  318.34  5164.8  319.07  5215.3  323.28  5273.6  326.57
#Mann= 5 ,-1 , 0
  4775.9     .09       0    4910     .16       0  4943.2     .05       0
  5002.4     .03       0  5008.4     .09       0
Bank Sta=4971.8,5017.1
XS Rating Curve= 0 ,0
Exp/Cntr=0.3,0.1

Type RM Length L Ch R = 1 ,1292    ,432,432,432
BEGIN DESCRIPTION:
UNT 03320 IN LACR 2.0
END DESCRIPTION:
XS GIS Cut Line= 3
      3706999.64      10648810.2      3706749.61     10648710.19
      3706599.62     10648660.19
#Sta/Elev= 30
  4741.2  325.34  4750.7  324.52    4756   324.7  4762.8  323.41  4795.1  321.02
  4809.9  319.03  4816.6  317.74  4827.4  317.43  4839.5  315.25  4848.9  314.41
  4858.4  312.83  4881.3  310.78  4912.2  307.07  4924.3  306.13  4956.8  304.57
  4978.2  304.27    4986  302.75  4988.7  302.25    4992  302.75  5001.1  302.96
  5007.8  304.09  5020.9  304.05  5031.6  305.29  5042.1     306  5084.3  309.73
  5094.8  310.33  5105.4  311.58    5137  313.71  5147.5  314.97  5168.6  316.72
#Mann= 5 ,-1 , 0
  4741.2     .05       0  4956.8     .16       0    4986     .07       0
    4992     .16       0  5020.9     .05       0
Bank Sta=4924.3,5042.1
XS Rating Curve= 0 ,0
Exp/Cntr=0.3,0.1

Type RM Length L Ch R = 1 ,860     ,483,483,483
BEGIN DESCRIPTION:
Mapping XS c316f039
END DESCRIPTION:
XS GIS Cut Line= 3
      3707033.75     10648683.88      3707120.54     10648453.89
      3706713.54     10648241.73
#Sta/Elev= 30
  4674.8  319.48  4689.4  319.49  4705.5  318.02  4710.9  318.58  4730.4  316.79
  4735.7  317.48  4760.6  315.51  4765.9  316.41  4785.4  314.52  4790.8  314.98
  4815.6  311.76    4821  312.34  4839.1   309.9  4845.8  308.17  4851.1  309.03
  4870.7  306.65    4876  307.31    4924     304  4932.9  302.59    4939  302.98
  4944.7  302.14    5015   301.8  5018.8  301.77  5021.5  301.27  5024.8  301.77
  5124.3  302.43  5132.2  302.97  5192.3  305.53  5293.8  314.08  5379.6  318.67
#Mann= 5 ,-1 , 0
  4674.8     .05       0    5015     .16       0  5018.8     .03       0
  5024.8     .16       0  5124.3     .05       0
Bank Sta=4924,5132.2
XS Rating Curve= 0 ,0
Exp/Cntr=0.3,0.1

Type RM Length L Ch R = 1 ,377     ,0,0,0
BEGIN DESCRIPTION:
UNT 03320 IN LACR 1.0
END DESCRIPTION:
XS GIS Cut Line= 4
      3707068.48     10648670.87       3707428.7     10648206.49
      3707398.31     10648015.52      3706623.01     10648058.83
#Sta/Elev= 30
  4333.3   320.7  4435.1   316.9    4456  314.69  4534.7   310.7    4541   309.5
    4570  308.44  4576.3  307.54  4584.5  307.94  4590.8  306.72  4619.8  306.14
  4626.1  304.83  4690.4  302.61  4698.6  303.23  4704.9  301.45    4713  302.16
  4716.4  301.12  4719.1  300.62  4722.4  301.12  4733.9  302.06  4740.2  301.12
  5413.6  301.12  5423.6  302.05  5563.8   309.6  5613.9  314.09  5633.9  315.09
  5647.6     315  5663.9  316.32  5744.1  319.42  5827.4  320.65  5890.9  323.02
#Mann= 3 ,-1 , 0
  4333.3     .05       0  4716.4    .033       0  4722.4     .05       0
Bank Sta=4698.6,5423.6
XS Rating Curve= 0 ,0
Exp/Cntr=0.3,0.1

Chan Stop Cuts=-1
Use User Specified Reach Order=0
Composite Channel Slope=5