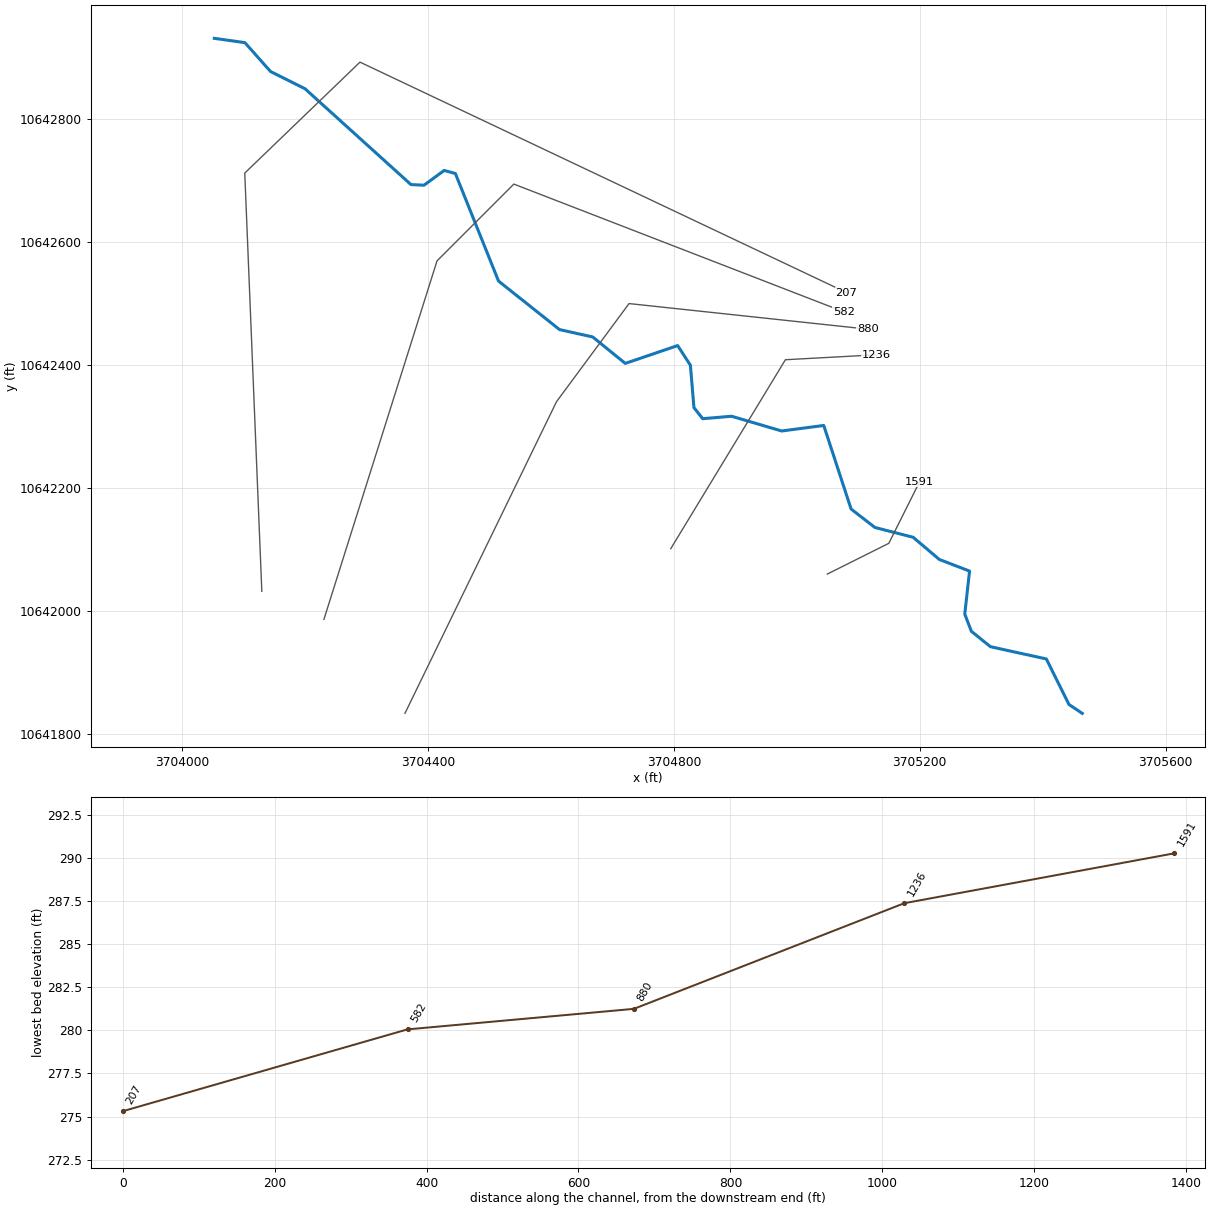
--- UNT 03325 IN LACR.prj (project) ---

Proj Title=UNT 03325 IN LACR Base Level Engineering
Current Plan=p01
Default Exp/Contr=0.3,0.1
English Units
Geom File=g01
Flow File=f01
Plan File=p01
BEGIN DESCRIPTION:
UNT 03325 IN LACR
END DESCRIPTION:

--- UNT 03325 IN LACR.p01 (plan) ---

Plan Title=Multiple Run
Short Identifier=Multiple
Geom File=g01
Flow File=f01
Subcritical Flow
K Sum by GR= 0
Std Step Tol= 0.01
Critical Tol= 0.01
Num of Std Step Trials= 20
Max Error Tol= 0.3
Flow Tol Ratio= 0.001
Split Flow NTrial= 30
Split Flow Tol= 0.02
Split Flow Ratio= 0.02
Log Output Level= 0
Friction Slope Method= 1
Unsteady Friction Slope Method= 2
Unsteady Bridges Friction Slope Method= 1
Parabolic Critical Depth
Global Vel Dist=  1 , 1 , 1
Global Log Level= 0
CheckData=True
Encroach Param= -1, 0, 0, 0
BEGIN DESCRIPTION:
Multiple Run
END DESCRIPTION:

--- UNT 03325 IN LACR.f01 (steady flow) ---

Flow Title=Multiple
Number of Profiles=7
Profile Names=10-year,25-year,50-year,1pct_min,100-year,1pct_plu,500-year
River Rch & RM= UNT 03325 IN LAC,Reach-1,1591
     169     211     243     207     280     379     372
Boundary for River Rch & Prof#=UNT 03325 IN LAC,Reach-1,1
Up Type=0
Dn Type=3
Dn Slope=0.005
Boundary for River Rch & Prof#=UNT 03325 IN LAC,Reach-1,2
Up Type=0
Dn Type=3
Dn Slope=0.005
Boundary for River Rch & Prof#=UNT 03325 IN LAC,Reach-1,3
Up Type=0
Dn Type=3
Dn Slope=0.005
Boundary for River Rch & Prof#=UNT 03325 IN LAC,Reach-1,4
Up Type=0
Dn Type=3
Dn Slope=0.005
Boundary for River Rch & Prof#=UNT 03325 IN LAC,Reach-1,5
Up Type=0
Dn Type=3
Dn Slope=0.005
Boundary for River Rch & Prof#=UNT 03325 IN LAC,Reach-1,6
Up Type=0
Dn Type=3
Dn Slope=0.005
Boundary for River Rch & Prof#=UNT 03325 IN LAC,Reach-1,7
Up Type=0
Dn Type=3
Dn Slope=0.005

--- UNT 03325 IN LACR.g01 (geometry) ---

Geom Title=Existing Conditions

River Reach=UNT 03325 IN LAC,Reach-1
Reach XY= 30
      3705464.42     10641833.46      3705442.75     10641848.00
      3705406.00     10641922.00      3705315.00     10641942.00
      3705284.00     10641967.00      3705273.25     10641995.00
      3705281.00     10642065.00      3705231.75     10642084.00
      3705189.25     10642120.00      3705127.00     10642136.00
      3705088.25     10642166.00      3705043.75     10642302.00
      3704975.25     10642293.00      3704893.75     10642317.00
      3704846.75     10642313.00      3704832.50     10642331.00
      3704826.75     10642400.00      3704806.00     10642432.00
      3704720.75     10642403.00      3704667.75     10642446.00
      3704613.75     10642458.00      3704514.50     10642537.00
      3704444.25     10642712.00      3704426.00     10642717.00
      3704393.25     10642693.00      3704372.00     10642694.00
      3704199.50     10642850.00      3704143.50     10642878.00
      3704101.75     10642925.00      3704052.00     10642932.00

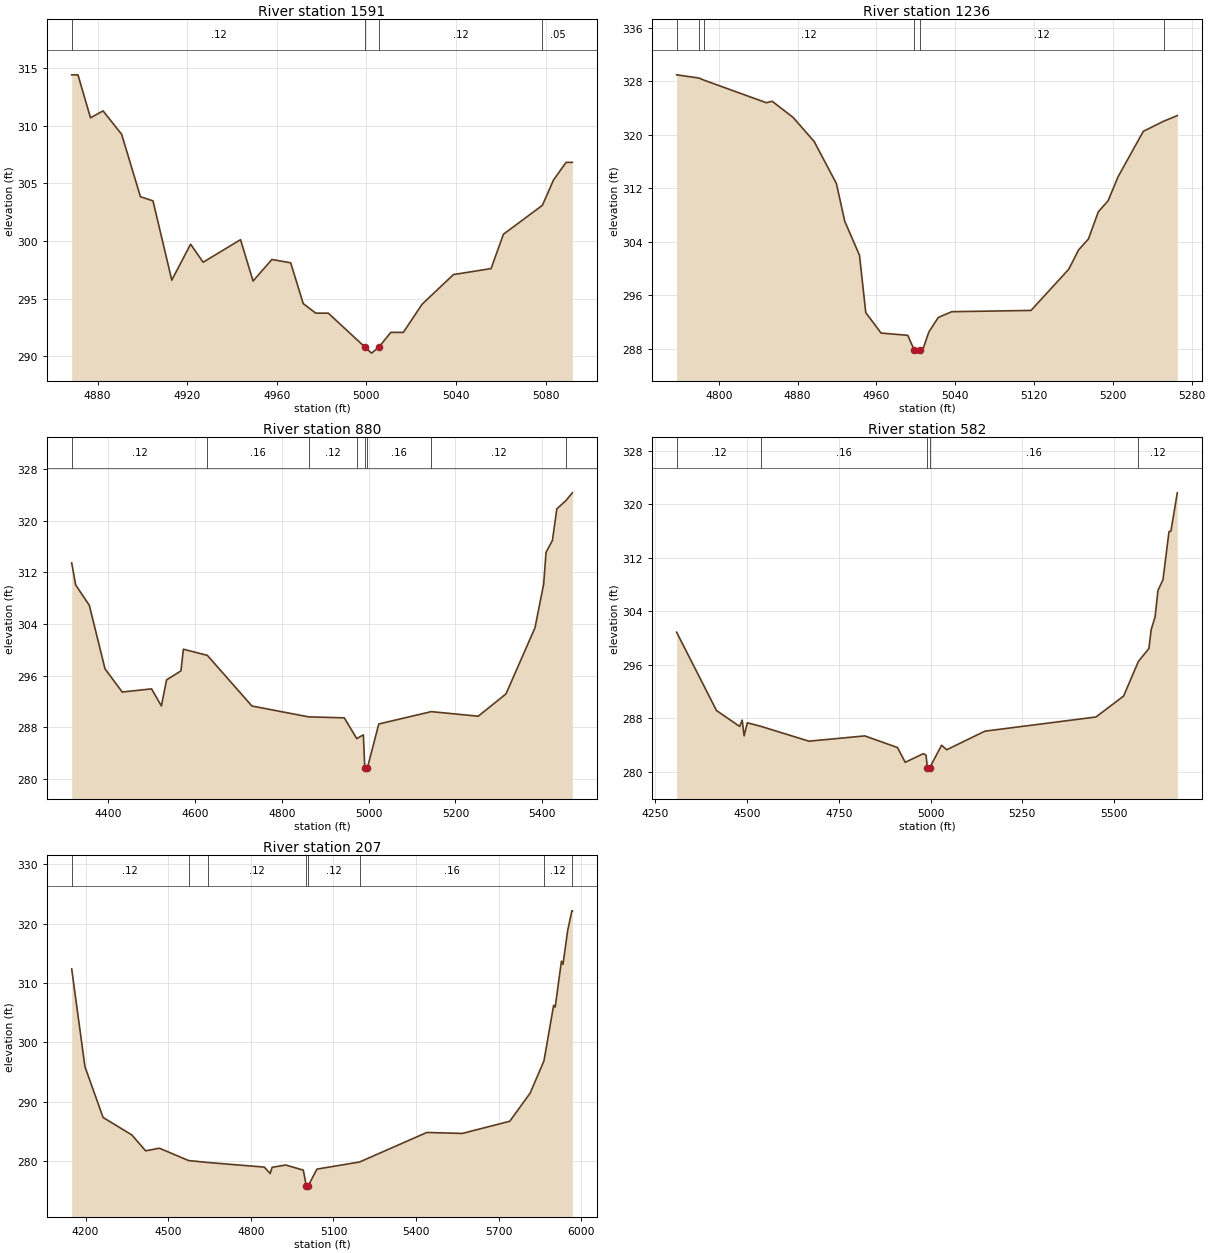
Type RM Length L Ch R = 1,1591,355,355,355
BEGIN DESCRIPTION:
UNT 03325 IN LACR 2.0
END DESCRIPTION:
XS GIS Cut Line= 3
      3705049.63     10642060.20      3705149.61     10642110.19
      3705199.61     10642210.20
#Sta/Elev= 30
  4868.4  314.43  4871.2  314.43  4876.8  310.70  4882.4  311.30  4890.7  309.27
  4899.1  303.85  4904.7  303.49  4913.1  296.61  4921.5  299.73  4927.1  298.16
  4943.8  300.12  4949.4  296.53  4957.8  298.40  4966.2  298.11  4971.8  294.57
  4977.4  293.74  4983.0  293.74  4999.5  290.77  5002.3  290.27  5005.5  290.77
  5010.9  292.07  5016.5  292.07  5024.9  294.52  5038.9  297.09  5055.7  297.61
  5061.2  300.59  5078.6  303.10  5083.6  305.31  5089.2  306.83  5092.0  306.83
#Mann=4,-1,0
  4868.4    0.12       0  4999.5    0.07       0  5005.5    0.12       0
  5078.6    0.05       0
Bank Sta=4999.5,5005.5
Exp/Cntr=0.3,0.1

Type RM Length L Ch R = 1,1236,356,356,356
BEGIN DESCRIPTION:
Mapping XS ff43112e
END DESCRIPTION:
XS GIS Cut Line= 3
      3704794.78     10642101.48      3704981.35     10642408.97
      3705129.66     10642417.03
#Sta/Elev= 30
  4757.2  328.96  4779.9  328.48  4785.0  328.16  4848.3  324.79  4854.2  325.01
  4875.5  322.59  4896.9  318.98  4919.4  312.71  4927.8  307.10  4942.8  302.01
  4949.2  293.43  4964.7  290.38  4991.8  290.04  4998.3  287.88  5001.1  287.38
  5004.3  287.88  5007.3  288.00  5013.2  290.54  5022.8  292.71  5036.4  293.57
  5116.9  293.76  5155.2  299.91  5165.2  302.80  5175.2  304.44  5185.2  308.49
  5195.2  310.16  5205.3  313.74  5230.9  320.52  5251.4  322.02  5265.4  322.87
#Mann=6,-1,0
  4757.2    0.16       0  4779.9    0.05       0  4785.0    0.12       0
  4998.3    0.07       0  5004.3    0.12       0  5251.4    0.05       0
Bank Sta=4998.3,5004.3
Exp/Cntr=0.3,0.1

Type RM Length L Ch R = 1,880,298,298,298
BEGIN DESCRIPTION:
Mapping XS a5855553
END DESCRIPTION:
XS GIS Cut Line= 4
      3704362.29     10641833.67      3704608.83     10642340.64
      3704726.89     10642500.36      3705115.22     10642458.75
#Sta/Elev= 30
  4316.4  313.44  4325.5  310.04  4357.0  306.89  4393.1  297.07  4432.7  293.48
  4500.3  293.97  4522.9  291.33  4534.9  295.36  4568.0  296.75  4573.5  300.10
  4628.8  299.15  4731.4  291.32  4861.8  289.64  4944.1  289.49  4972.8  286.28
  4988.0  286.86  4991.3  281.75  4994.0  281.25  4997.3  281.75  5023.5  288.54
  5144.4  290.45  5252.5  289.74  5316.4  293.19  5383.2  303.41  5403.3  310.22
  5408.6  315.07  5423.4  316.93  5433.5  321.80  5454.0  323.05  5469.3  324.28
#Mann=8,-1,0
  4316.4    0.12       0  4628.8    0.16       0  4861.8    0.12       0
  4972.8    0.16       0  4991.3    0.07       0  4997.3    0.16       0
  5144.4    0.12       0  5454.0    0.05       0
Bank Sta=4991.3,4997.3
Exp/Cntr=0.3,0.1

Type RM Length L Ch R = 1,582,375,375,375
BEGIN DESCRIPTION:
Mapping XS 0da328fe
END DESCRIPTION:
XS GIS Cut Line= 4
      3704230.36     10641986.49      3704414.39     10642569.81
      3704539.39     10642694.81      3705076.05     10642487.06
#Sta/Elev= 30
  4308.4  300.84  4417.1  289.12  4480.1  286.75  4487.0  287.69  4492.2  285.35
  4501.0  287.29  4537.5  286.77  4668.8  284.54  4821.0  285.33  4910.0  283.59
  4931.1  281.38  4980.6  282.68  4987.7  282.45  4991.7  280.56  4994.5  280.06
  4997.7  280.56  5030.1  283.93  5044.2  283.26  5148.2  286.04  5450.7  288.16
  5526.0  291.29  5566.3  296.47  5595.0  298.41  5601.1  301.24  5611.8  303.13
  5619.6  307.10  5633.2  308.68  5649.6  315.88  5654.9  315.98  5672.3  321.70
#Mann=5,-1,0
  4308.4    0.12       0  4537.5    0.16       0  4991.7    0.07       0
  4997.7    0.16       0  5566.3    0.12       0
Bank Sta=4991.7,4997.7
Exp/Cntr=0.3,0.1

Type RM Length L Ch R = 1,207,0,0,0
BEGIN DESCRIPTION:
UNT 03325 IN LACR 1.0
END DESCRIPTION:
XS GIS Cut Line= 4
      3704129.28     10642032.13      3704101.51     10642712.71
      3704289.01     10642893.27      3705080.64     10642518.28
#Sta/Elev= 30
  4149.9  312.38  4198.0  295.93  4263.8  287.38  4368.1  284.44  4418.2  281.76
  4468.2  282.20  4574.4  280.12  4645.4  279.79  4849.1  279.02  4870.2  277.94
  4877.4  278.98  4926.8  279.37  4990.6  278.51  5001.8  275.81  5004.5  275.31
  5007.8  275.81  5040.0  278.68  5195.0  279.88  5438.9  284.85  5567.8  284.69
  5740.1  286.74  5813.9  291.47  5864.1  296.90  5899.3  306.26  5904.9  305.97
  5927.6  313.69  5933.2  313.16  5950.4  318.90  5965.5  322.17  5967.3  322.17
#Mann=8,-1,0
  4149.9    0.12       0  4574.4    0.16       0  4645.4    0.12       0
  5001.8    0.07       0  5007.8    0.12       0  5195.0    0.16       0
  5864.1    0.12       0  5965.5    0.05       0
Bank Sta=5001.8,5007.8
Exp/Cntr=0.3,0.1

Chan Stop Cuts=-1