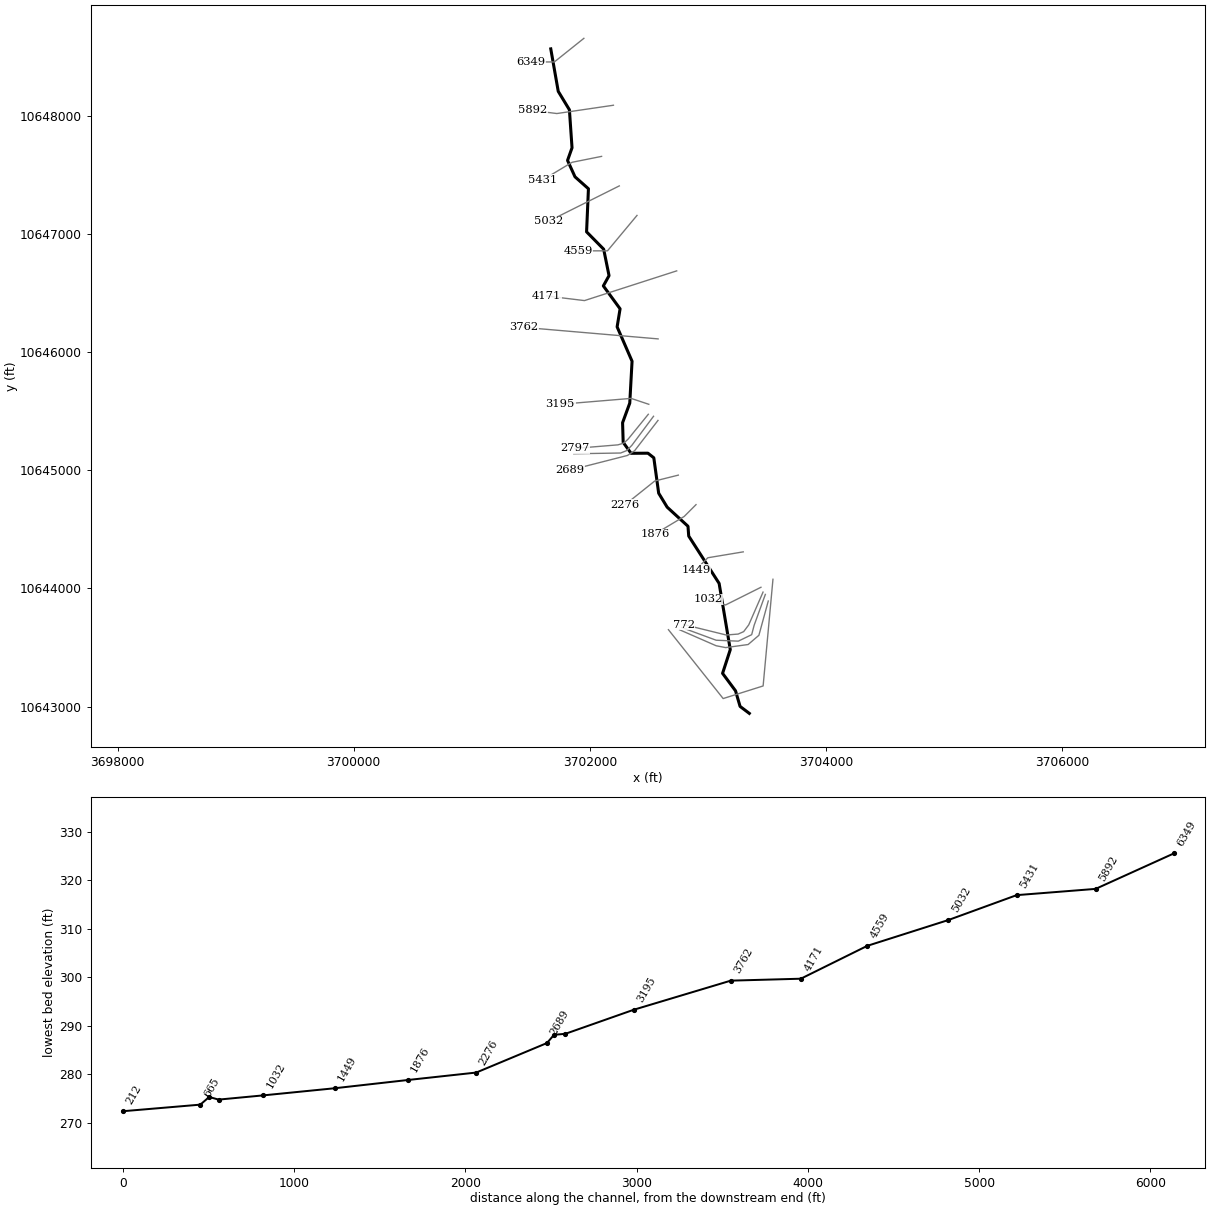
--- UNT 03326 IN LACR.prj (project) ---

Proj Title=UNT 03326 IN LACR Base Level Engineering
Current Plan=p01
Default Exp/Contr=0.3,0.1
English Units
Geom File=g01
Flow File=f01
Plan File=p01
Y Axis Title=Elevation
X Axis Title(PF)=Main Channel Distance
X Axis Title(XS)=Station
BEGIN DESCRIPTION:
UNT 03326 IN LACR
END DESCRIPTION:
DSS Export Rating Curves= 0
DSS Export Rating Curve Sorted= 0
DSS Export Volume Flow Curves= 0
DXF OffsetX= 0
DXF OffsetY= 0
DXF ScaleX= 1
DXF ScaleY= 10

--- UNT 03326 IN LACR.p01 (plan) ---

Plan Title=Multiple Run
Short Identifier=Multiple
Geom File=g01
Flow File=f01
Subcritical Flow
K Sum by GR= 0
Std Step Tol= 0.01
Critical Tol= 0.01
Num of Std Step Trials= 20
Max Error Tol= 0.3
Flow Tol Ratio= 0.001
Split Flow NTrial= 30
Split Flow Tol= 0.02
Split Flow Ratio= 0.02
Log Output Level= 0
Friction Slope Method= 1
Unsteady Friction Slope Method= 2
Unsteady Bridges Friction Slope Method= 1
Parabolic Critical Depth
Global Vel Dist=  1 , 1 , 1
Global Log Level= 0
CheckData=True
Encroach Param= -1, 0, 0, 0
BEGIN DESCRIPTION:
Multiple Run
END DESCRIPTION:

--- UNT 03326 IN LACR.f01 (steady flow) ---

Flow Title=Multiple
Program Version=4.10
Number of Profiles= 7
Profile Names=10-year,25-year,50-year,1pct_min,100-year,1pct_plu,500-year
River Rch & RM=UNT 03326 IN LAC,Reach-1         ,6349
     454     607     731     649     878    1187    1268
Boundary for River Rch & Prof#=UNT 03326 IN LAC,Reach-1         , 1
Up Type= 0
Dn Type= 3
Dn Slope=0.003
Boundary for River Rch & Prof#=UNT 03326 IN LAC,Reach-1         , 2
Up Type= 0
Dn Type= 3
Dn Slope=0.003
Boundary for River Rch & Prof#=UNT 03326 IN LAC,Reach-1         , 3
Up Type= 0
Dn Type= 3
Dn Slope=0.003
Boundary for River Rch & Prof#=UNT 03326 IN LAC,Reach-1         , 4
Up Type= 0
Dn Type= 3
Dn Slope=0.003
Boundary for River Rch & Prof#=UNT 03326 IN LAC,Reach-1         , 5
Up Type= 0
Dn Type= 3
Dn Slope=0.003
Boundary for River Rch & Prof#=UNT 03326 IN LAC,Reach-1         , 6
Up Type= 0
Dn Type= 3
Dn Slope=0.003
Boundary for River Rch & Prof#=UNT 03326 IN LAC,Reach-1         , 7
Up Type= 0
Dn Type= 3
Dn Slope=0.003
DSS Import GetInterval= 0
DSS Import GetPeak= 0
DSS Import FillOption= 0

--- UNT 03326 IN LACR.g01 (geometry) ---

Geom Title=Existing Conditions
Program Version=4.10

River Reach=UNT 03326 IN LAC,Reach-1
Reach XY= 30
      3701669.15     10648570.85       3701732.5       10648211.
        3701827.       10648055.      3701849.25       10647733.
      3701811.25       10647626.       3701874.5       10647487.
      3701988.25       10647386.      3701972.49      10647021.1
      3702117.25       10646874.      3702162.75       10646650.
       3702114.5       10646563.      3702256.25       10646369.
      3702231.25       10646216.      3702357.75       10645925.
      3702338.25       10645570.       3702277.5       10645404.
       3702282.5       10645238.       3702349.5       10645145.
      3702492.25       10645146.        3702542.       10645107.
      3702583.25       10644807.        3702655.       10644689.
       3702831.5       10644527.      3702837.75       10644444.
      3703095.25       10644043.      3703189.75       10643482.
       3703124.5       10643281.      3703234.25       10643133.
      3703272.75       10643001.        3703351.       10642942.

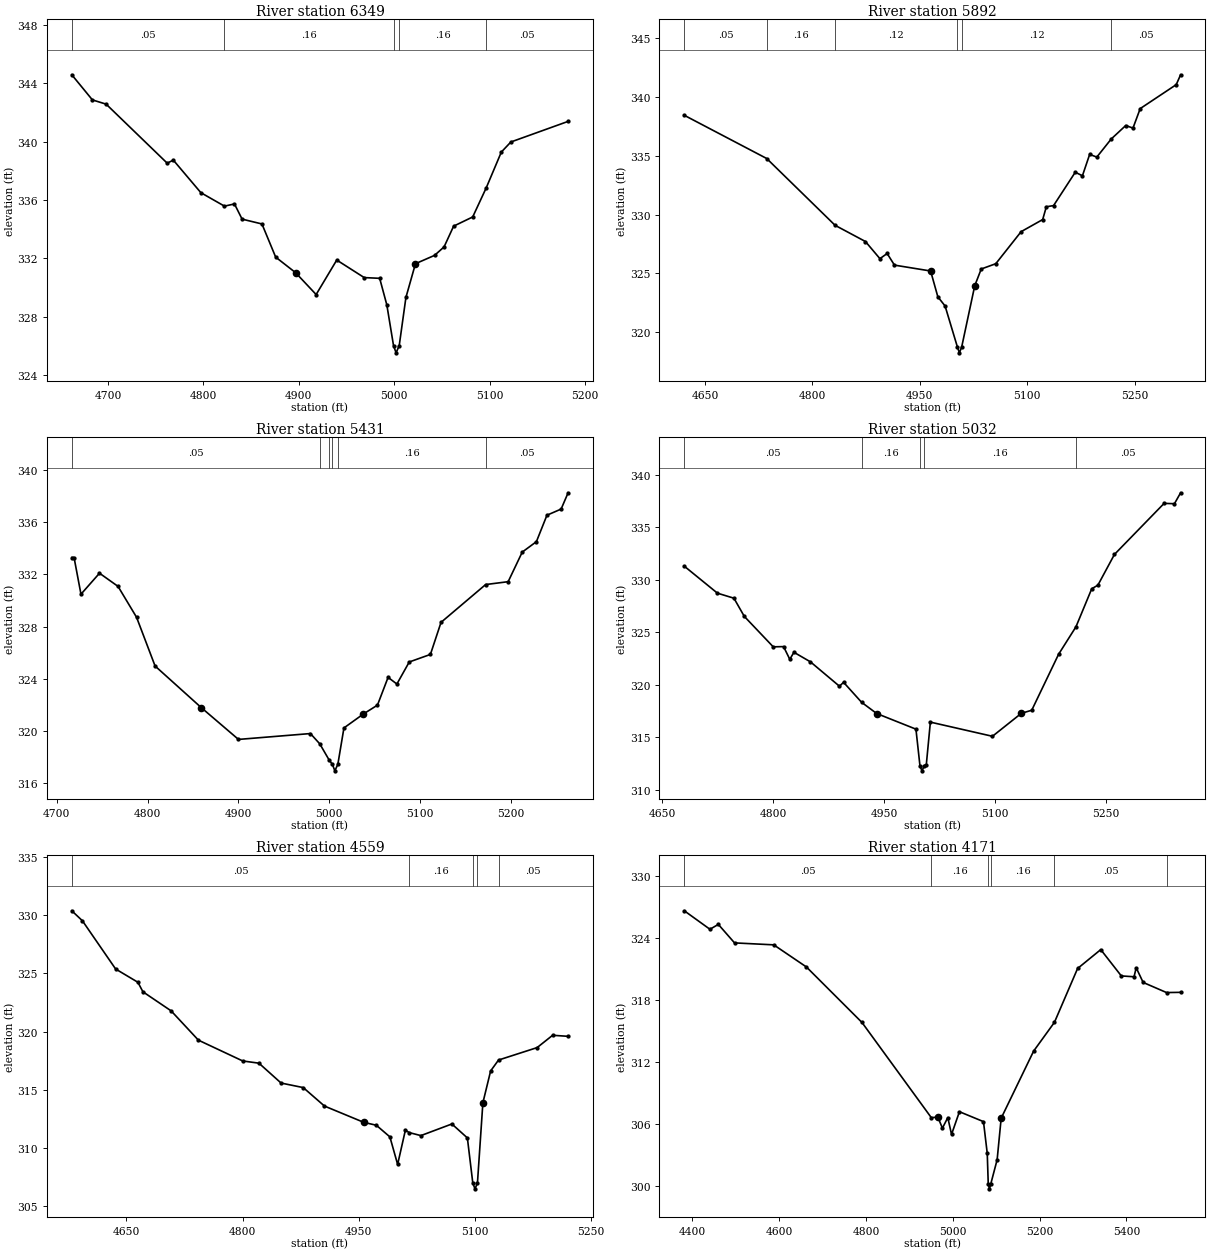
Type RM Length L Ch R = 1 ,6349    ,457,457,457
BEGIN DESCRIPTION:
UNT 03326 IN LACR 14.0
END DESCRIPTION:
XS GIS Cut Line= 3
      3701949.61     10648660.19      3701699.61     10648460.19
      3701499.56     10648460.19
#Sta/Elev= 30
    4662  344.57  4683.6  342.85    4698  342.56    4762  338.52  4768.4  338.73
  4797.3   336.5    4822  335.58  4832.5  335.73  4840.5  334.69  4861.3  334.36
  4875.7  332.09  4896.5  331.03  4918.1  329.53  4939.7  331.89  4968.5  330.69
  4984.7  330.64  4992.2  328.82  4999.2  326.04  5001.9  325.54  5005.2  326.04
  5012.2  329.33  5022.2  331.64  5042.2  332.21  5052.2  332.79  5062.2  334.21
  5082.2  334.84  5096.5  336.85  5112.2  339.28  5122.2  339.97  5182.2  341.38
#Mann= 5 ,-1 , 0
    4662     .05       0    4822     .16       0  4999.2     .07       0
  5005.2     .16       0  5096.5     .05       0
Bank Sta=4896.5,5022.2
XS Rating Curve= 0 ,0
Exp/Cntr=0.3,0.1

Type RM Length L Ch R = 1 ,5892    ,461,461,461
BEGIN DESCRIPTION:
UNT 03326 IN LACR 13.0
END DESCRIPTION:
XS GIS Cut Line= 3
      3702199.95     10648093.48      3701720.82     10648023.18
       3701513.6     10648049.08
#Sta/Elev= 30
    4621  338.45  4736.1  334.77  4831.6  329.08    4874   327.7  4894.2  326.24
  4904.3  326.68  4914.5  325.69    4965  325.19  4975.1  322.99  4985.2  322.21
  5002.4  318.72  5005.2  318.22  5008.4  318.72  5026.6  323.93  5035.7  325.36
    5056  325.81  5091.4  328.54  5121.5  329.57  5126.6  330.66  5136.7  330.76
    5167   333.6    5177   333.3  5187.1  335.12  5197.1  334.89  5217.2  336.43
  5237.5  337.58  5247.6  337.36  5257.7  339.02    5308  341.06  5314.1   341.9
#Mann= 6 ,-1 , 0
    4621     .05       0  4736.1     .16       0  4831.6     .12       0
  5002.4     .07       0  5008.4     .12       0  5217.2     .05       0
Bank Sta=4965,5026.6
XS Rating Curve= 0 ,0
Exp/Cntr=0.3,0.1

Type RM Length L Ch R = 1 ,5431    ,399,399,399
BEGIN DESCRIPTION:
UNT 03326 IN LACR 12.0
END DESCRIPTION:
XS GIS Cut Line= 3
      3702099.56     10647660.18      3701849.61     10647610.19
      3701599.65     10647460.21
#Sta/Elev= 30
  4716.6  333.29  4719.1  333.29  4726.7  330.48  4747.1  332.09  4767.5  331.08
  4787.9  328.71  4808.3  324.97  4859.3  321.77  4900.1  319.34  4979.3  319.79
  4989.6     319    5000  317.75  5003.5  317.43  5006.2  316.93  5009.5  317.43
  5016.2  320.22  5037.6  321.29  5053.1  321.97  5064.8   324.1  5074.5  323.59
  5088.1  325.28  5111.4  325.86  5123.1  328.32  5172.2  331.22    5197  331.44
  5212.5  333.71  5228.1  334.51  5239.7  336.54  5255.3  337.01    5263  338.26
#Mann= 6 ,-1 , 0
  4716.6     .05       0  4989.6     .12       0    5000     .16       0
  5003.5     .07       0  5009.5     .16       0  5172.2     .05       0
Bank Sta=4859.3,5037.6
XS Rating Curve= 0 ,0
Exp/Cntr=0.3,0.1

Type RM Length L Ch R = 1 ,5032    ,473,473,473
BEGIN DESCRIPTION:
UNT 03326 IN LACR 11.0
END DESCRIPTION:
XS GIS Cut Line= 3
      3702249.63      10647410.2      3701949.61     10647260.19
      3701649.65     10647110.21
#Sta/Elev= 30
  4680.2  331.28    4725  328.71  4747.3  328.23  4761.3   326.5  4800.4   323.6
  4814.4  323.62  4822.8  322.41  4828.4  323.08  4850.7  322.17  4889.9  319.85
  4895.5  320.22  4919.8  318.32  4940.2  317.25  4993.3  315.76  4998.7  312.29
  5001.4  311.79  5004.7  312.29  5007.3  312.37  5012.8  316.43  5096.7  315.08
  5135.8  317.27  5149.8  317.56  5186.1  322.89  5209.6  325.51  5230.9  329.13
  5239.2  329.47  5261.6   332.4  5328.7  337.26  5342.7  337.23    5351  338.27
#Mann= 5 ,-1 , 0
  4680.2     .05       0  4919.8     .16       0  4998.7     .07       0
  5004.7     .16       0  5209.6     .05       0
Bank Sta=4940.2,5135.8
XS Rating Curve= 0 ,0
Exp/Cntr=0.3,0.1

Type RM Length L Ch R = 1 ,4559    ,388,388,388
BEGIN DESCRIPTION:
UNT 03326 IN LACR 10.0
END DESCRIPTION:
XS GIS Cut Line= 3
      3702399.61     10647160.18      3702149.61     10646860.19
      3701899.62     10646860.19
#Sta/Elev= 30
  4579.6  330.39  4593.3  329.53  4636.2  325.38  4664.9  324.24  4671.4  323.42
  4707.8  321.78    4743  319.26  4800.2  317.47  4821.1  317.28  4849.7  315.57
  4878.3  315.18  4905.7  313.59  4956.4  312.19  4972.6  311.94  4990.1  310.94
  5000.1  308.57  5010.1  311.52    5015  311.31  5030.1  311.05  5070.1  312.05
  5090.1  310.85  5097.1  306.97  5099.9  306.47  5103.1  306.97  5110.1  313.87
  5120.1  316.61  5130.3  317.55  5180.1  318.62  5200.1  319.68  5220.1  319.59
#Mann= 5 ,-1 , 0
  4579.6     .05       0    5015     .16       0  5097.1     .03       0
  5103.1     .16       0  5130.3     .05       0
Bank Sta=4956.4,5110.1
XS Rating Curve= 0 ,0
Exp/Cntr=0.3,0.1

Type RM Length L Ch R = 1 ,4171    ,409,409,409
BEGIN DESCRIPTION:
UNT 03326 IN LACR 9.0
END DESCRIPTION:
XS GIS Cut Line= 3
      3702735.86     10646690.39      3701954.62     10646438.66
      3701633.98     10646477.65
#Sta/Elev= 30
  4381.3  326.62  4440.4  324.83  4459.8   325.3  4497.1  323.51  4587.5  323.32
  4662.7  321.18  4790.9   315.8  4950.5  306.59  4965.7  306.63  4976.2  305.57
  4988.6  306.59  4997.2  304.96  5015.4  307.16  5070.8   306.2  5079.5  303.13
  5081.8  300.19  5084.5  299.69  5087.8  300.19  5102.3  302.51  5111.6  306.53
  5186.4  313.03  5234.4  315.82  5287.7  321.03  5341.1  322.86  5388.5  320.31
  5417.8  320.23  5422.8   321.1  5438.8  319.68  5492.7   318.7  5525.1  318.72
#Mann= 6 ,-1 , 0
  4381.3     .05       0  4950.5     .16       0  5081.8     .07       0
  5087.8     .16       0  5234.4     .05       0  5492.7     .12       0
Bank Sta=4965.7,5111.6
XS Rating Curve= 0 ,0
Exp/Cntr=0.3,0.1

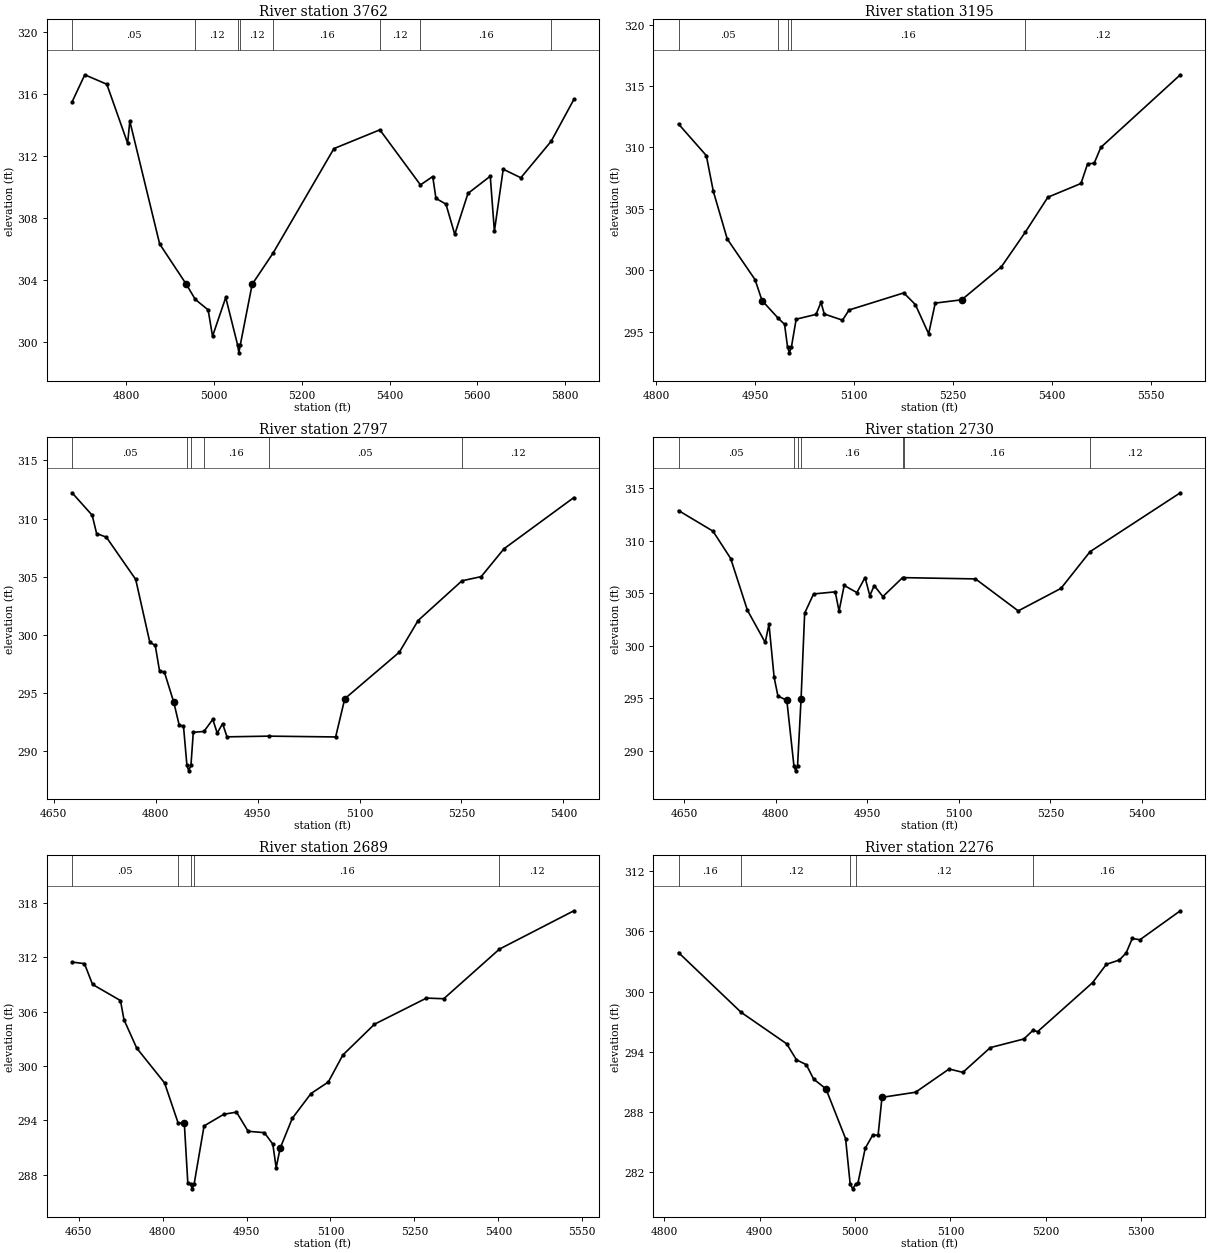
Type RM Length L Ch R = 1 ,3762    ,567,567,567
BEGIN DESCRIPTION:
UNT 03326 IN LACR 8.0
END DESCRIPTION:
XS GIS Cut Line= 2
      3702578.53     10646114.18      3701439.21     10646211.84
#Sta/Elev= 30
  4676.4  315.47  4705.4  317.22  4755.6  316.61    4803  312.81    4808  314.23
    4876  306.31  4936.3  303.73  4957.3  302.73  4986.5  302.06  4996.5  300.36
  5026.6  302.86  5053.7  299.79  5056.5  299.29  5059.7  299.79  5086.8  303.71
  5134.6  305.73  5273.1  312.46  5377.8  313.67  5470.3  310.12  5498.3  310.66
  5505.6  309.25  5528.4  308.88  5548.5  306.93  5578.6  309.57  5629.4  310.68
  5638.8  307.13  5658.9  311.13  5699.1  310.58  5768.1  312.93  5819.9  315.63
#Mann= 8 ,-1 , 0
  4676.4     .05       0  4957.3     .12       0  5053.7     .07       0
  5059.7     .12       0  5134.6     .16       0  5377.8     .12       0
  5470.3     .16       0  5768.1     .12       0
Bank Sta=4936.3,5086.8
XS Rating Curve= 0 ,0
Exp/Cntr=0.3,0.1

Type RM Length L Ch R = 1 ,3195    ,398,398,398
BEGIN DESCRIPTION:
UNT 03326 IN LACR 7.0
END DESCRIPTION:
XS GIS Cut Line= 3
      3702499.59     10645560.19      3702349.61     10645610.19
      3701749.59     10645560.19
#Sta/Elev= 30
  4834.1  311.91  4876.2  309.34  4886.8  306.43  4907.9  302.55    4950  299.24
  4960.6  297.54  4984.2  296.15  4994.7   295.6  4999.2  293.78    5002  293.28
  5005.2  293.78  5012.3  296.02  5042.4  296.41  5049.9  297.39  5054.9  296.44
  5082.5  295.94  5092.5  296.77  5175.3  298.16  5192.9  297.21    5213  294.83
    5223  297.33  5263.1   297.6  5323.3  300.29  5359.5  303.11  5393.6  305.95
  5443.8  307.07  5453.8  308.67  5463.8  308.72  5473.9  310.01  5594.3  315.92
#Mann= 5 ,-1 , 0
  4834.1     .05       0  4984.2     .16       0  4999.2     .07       0
  5005.2     .16       0  5359.5     .12       0
Bank Sta=4960.6,5263.1
XS Rating Curve= 0 ,0
Exp/Cntr=0.3,0.1

Type RM Length L Ch R = 1 ,2797    ,67,67,67
BEGIN DESCRIPTION:
Mapping XS a0b0f6f7
END DESCRIPTION:
XS GIS Cut Line= 6
      3702495.39     10645475.61      3702326.14      10645267.3
      3702292.28     10645234.75      3702268.84     10645225.63
      3702237.59     10645216.52      3701873.78     10645186.63
#Sta/Elev= 30
  4677.2  312.21  4706.8  310.28  4713.3  308.71  4727.6   308.4  4770.8  304.77
  4791.6  299.36  4799.5  299.11  4805.9   296.9    4813  296.81  4826.8  294.22
  4834.7  292.27  4841.1  292.16  4846.1  288.83  4848.8  288.33  4852.1  288.83
  4855.5  291.64  4871.1  291.71  4884.2  292.75  4890.7  291.57  4898.6  292.38
  4905.1  291.25  4966.5  291.31  5064.9  291.24  5078.3  294.52  5158.6  298.52
  5186.2  301.24  5250.7  304.65    5279  305.01  5312.5   307.4  5415.3   311.8
#Mann= 6 ,-1 , 0
  4677.2     .05       0  4846.1     .03       0  4852.1     .05       0
  4871.1     .16       0  4966.5     .05       0  5250.7     .12       0
Bank Sta=4826.8,5078.3
XS Rating Curve= 0 ,0
Exp/Cntr=0.3,0.1

Type RM Length L Ch R = 1 ,2730    ,41,41,41
BEGIN DESCRIPTION:
Mapping XS 4335def7
END DESCRIPTION:
XS GIS Cut Line= 5
      3702539.66     10645458.67      3702356.08     10645212.61
      3702313.12     10645168.34      3702261.03     10645147.51
      3701864.27       10645141.
#Sta/Elev= 30
    4641  312.86  4697.4   310.9  4726.4   308.3  4753.7  303.39  4782.9  300.32
  4789.1  302.05  4797.5  297.01  4803.7  295.23  4818.3  294.81  4829.9  288.61
  4832.7  288.11  4835.9  288.61  4841.6  294.91  4847.5   303.1  4862.1  304.93
  4897.6  305.13  4903.8   303.3  4912.2  305.74    4933  305.06  4946.4  306.49
  4954.2  304.77  4961.4  305.72  4975.6  304.68    5008  306.49  5010.9  306.48
  5127.2  306.36  5197.2  303.32  5267.2  305.46  5314.8  308.95  5462.6  314.55
#Mann= 7 ,-1 , 0
    4641     .05       0  4829.9     .07       0  4835.9     .05       0
  4841.6     .16       0    5008     .05       0  5010.9     .16       0
  5314.8     .12       0
Bank Sta=4818.3,4841.6
XS Rating Curve= 0 ,0
Exp/Cntr=0.3,0.1

Type RM Length L Ch R = 1 ,2689    ,413,413,413
BEGIN DESCRIPTION:
UNT 03326 IN LACR 6.0
END DESCRIPTION:
XS GIS Cut Line= 4
      3702577.46     10645423.58      3702379.52     10645167.04
      3702318.32     10645126.67       3701834.3     10645003.06
#Sta/Elev= 30
  4638.1  311.48  4660.2  311.31  4674.7  309.01  4724.6  307.23  4730.9  305.11
  4753.6  301.98  4803.4  298.13  4827.7  293.69  4838.7  293.69    4845  287.05
  4850.2  286.92  4852.9  286.42  4856.2  286.92    4874  293.37  4909.3  294.66
    4932   294.9  4952.8  292.78  4981.8  292.63  4996.9  291.36  5002.9  288.75
  5009.9  290.89  5031.7  294.21  5065.1  296.95    5096  298.22  5122.1  301.21
  5178.6  304.61  5271.5   307.5  5302.5  307.43  5401.9  312.91    5535  317.15
#Mann= 5 ,-1 , 0
  4638.1     .05       0  4827.7     .16       0  4850.2     .07       0
  4856.2     .16       0  5401.9     .12       0
Bank Sta=4838.7,5009.9
XS Rating Curve= 0 ,0
Exp/Cntr=0.3,0.1

Type RM Length L Ch R = 1 ,2276    ,400,400,400
BEGIN DESCRIPTION:
UNT 03326 IN LACR 5.0
END DESCRIPTION:
XS GIS Cut Line= 3
       3702749.6     10644960.19      3702549.61     10644910.19
      3702299.61     10644710.19
#Sta/Elev= 30
  4814.8  303.88  4880.4  297.93  4928.2  294.79  4938.5  293.19  4948.8  292.71
  4956.5  291.27  4969.4   290.3    4990  285.34  4994.8  280.83  4997.5  280.33
  5000.8  280.83  5002.9  280.88  5010.6  284.37  5018.4  285.68  5024.1  285.68
  5028.2  289.45  5063.4  289.96  5098.6  292.28    5113  291.94  5141.8  294.41
    5177  295.27  5186.5  296.13  5191.4     296  5249.1  300.89  5263.5  302.71
  5277.1  303.14  5284.3  303.85  5290.7  305.29  5298.7  305.16  5341.1  308.05
#Mann= 5 ,-1 , 0
  4814.8     .16       0  4880.4     .12       0  4994.8     .07       0
  5000.8     .12       0  5186.5     .16       0
Bank Sta=4969.4,5028.2
XS Rating Curve= 0 ,0
Exp/Cntr=0.3,0.1

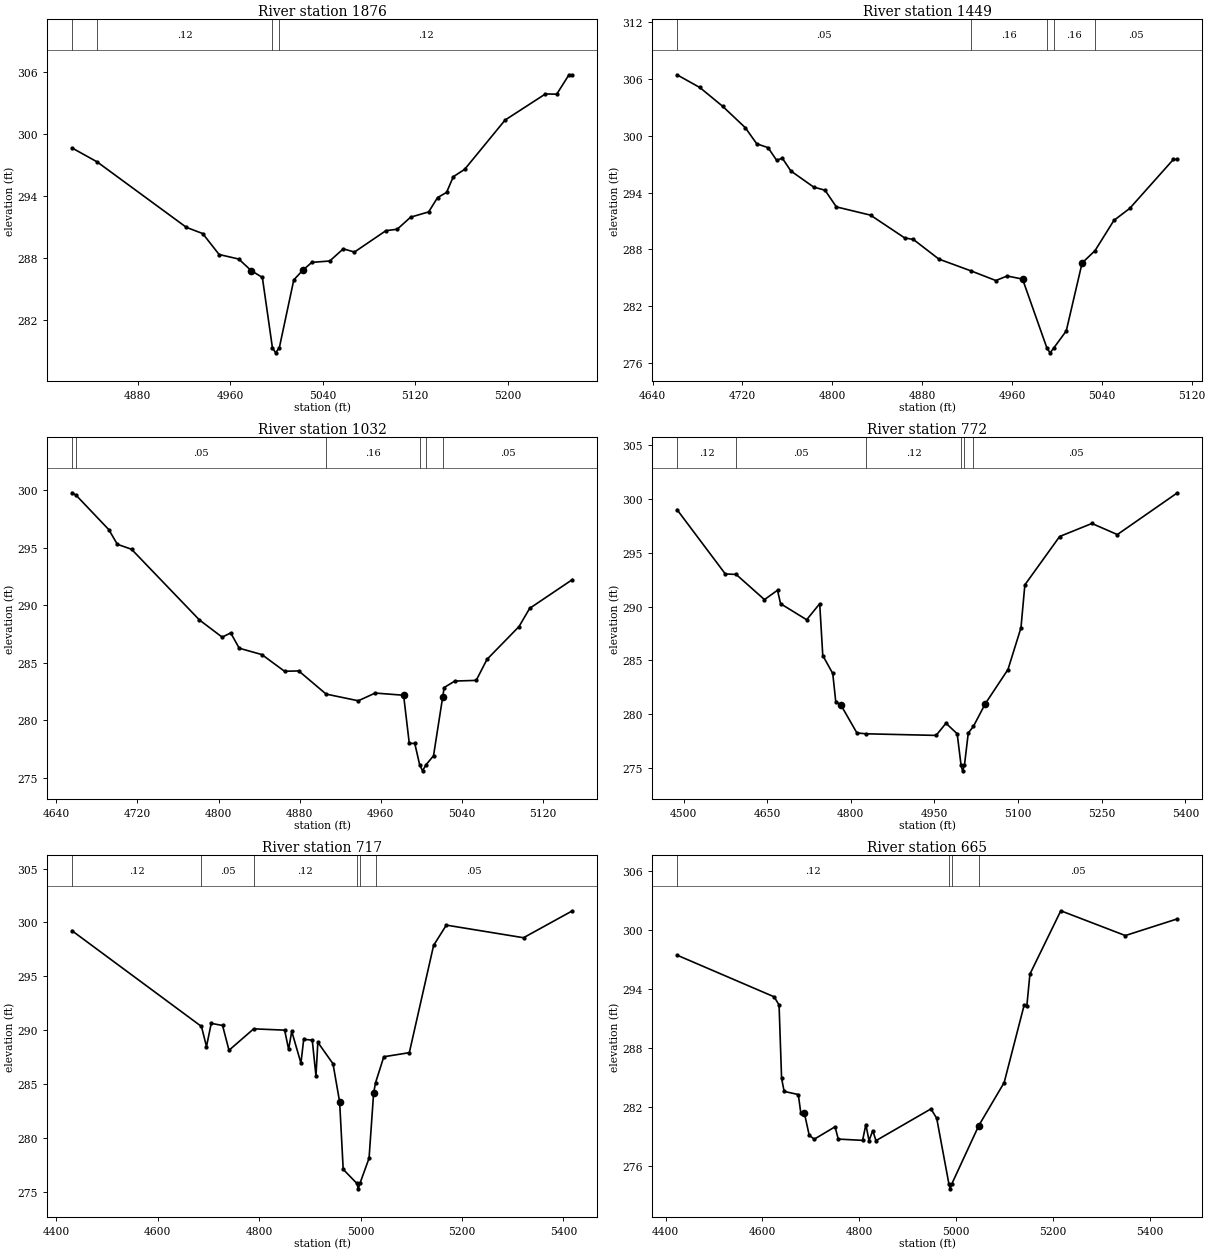
Type RM Length L Ch R = 1 ,1876    ,427,427,427
BEGIN DESCRIPTION:
UNT 03326 IN LACR 4.0
END DESCRIPTION:
XS GIS Cut Line= 3
       3702899.6     10644710.18      3702799.61     10644610.19
      3702549.58     10644460.17
#Sta/Elev= 30
  4823.1  298.65  4844.8   297.3  4922.1  290.95  4936.2  290.35  4950.4  288.32
  4967.4  287.88  4978.1  286.76  4987.8   286.1  4996.5  279.29  4999.3  278.79
  5002.5  279.29    5015  285.86  5022.8   286.8  5030.6  287.56  5046.1  287.69
  5057.8  288.87  5067.5  288.56  5094.7  290.63  5104.5  290.77  5116.1  291.94
  5131.7  292.45  5139.4  293.84  5147.2  294.34    5153  295.86  5162.8  296.57
  5197.8  301.35  5232.7  303.88  5242.5  303.86  5253.1  305.74  5256.1  305.74
#Mann= 4 ,-1 , 0
  4823.1     .16       0  4844.8     .12       0  4996.5     .07       0
  5002.5     .12       0
Bank Sta=4978.1,5022.8
XS Rating Curve= 0 ,0
Exp/Cntr=0.3,0.1

Type RM Length L Ch R = 1 ,1449    ,417,417,417
BEGIN DESCRIPTION:
UNT 03326 IN LACR 3.0
END DESCRIPTION:
XS GIS Cut Line= 3
      3703299.61     10644310.19      3702999.61     10644260.19
      3702899.58     10644160.16
#Sta/Elev= 30
  4661.7  306.43    4682  305.09  4702.3  303.11  4722.5  300.85  4732.7  299.15
  4742.8  298.74  4750.4  297.41  4755.5  297.63  4763.1  296.28  4783.4  294.58
  4793.5  294.25  4803.6  292.49    4834  291.62  4864.5  289.21  4872.1  289.06
  4894.9  286.98  4923.2  285.75  4945.6  284.72  4955.7   285.2  4969.4  284.87
  4991.1  277.59  4993.9  277.09  4997.1  277.59  5008.3   279.4  5022.4  286.57
  5033.9  287.87  5050.7  291.06  5064.8  292.33  5103.7   297.5  5107.3   297.5
#Mann= 5 ,-1 , 0
  4661.7     .05       0  4923.2     .16       0  4991.1     .07       0
  4997.1     .16       0  5033.9     .05       0
Bank Sta=4969.4,5022.4
XS Rating Curve= 0 ,0
Exp/Cntr=0.3,0.1

Type RM Length L Ch R = 1 ,1032    ,260,260,260
BEGIN DESCRIPTION:
UNT 03326 IN LACR 2.0
END DESCRIPTION:
XS GIS Cut Line= 3
      3703449.57     10644010.17      3703149.61     10643860.19
       3702999.6     10643910.19
#Sta/Elev= 30
  4655.5  299.75  4659.5  299.54  4691.8  296.55  4700.2  295.28  4714.2  294.85
  4781.2  288.71  4803.6  287.22    4812  287.59  4820.4  286.26  4842.7  285.71
  4865.1  284.26  4879.1  284.29  4906.1  282.28  4937.8   281.7  4954.5  282.37
  4982.5  282.18  4988.1     278  4993.5     278  4998.4  276.12  5001.2  275.62
  5004.4  276.12    5012  276.93  5021.1  282.06  5022.5  282.85    5033  283.41
  5054.1  283.47  5064.7  285.29  5096.3  288.14  5106.8  289.72    5149  292.22
#Mann= 6 ,-1 , 0
  4655.5     .12       0  4659.5     .05       0  4906.1     .16       0
  4998.4     .07       0  5004.4     .16       0  5021.1     .05       0
Bank Sta=4982.5,5021.1
XS Rating Curve= 0 ,0
Exp/Cntr=0.3,0.1

Type RM Length L Ch R = 1 ,772     ,55,55,55
BEGIN DESCRIPTION:
Mapping XS 4f7a6089
END DESCRIPTION:
XS GIS Cut Line= 6
      3703467.31     10643969.21      3703346.23     10643691.89
      3703303.26      10643634.6      3703256.38     10643613.76
      3703154.82     10643605.95      3702795.48     10643694.48
#Sta/Elev= 30
  4488.1  299.01  4574.8  293.03  4594.2  292.99    4645  290.65  4668.4  291.52
  4673.9  290.27  4720.7  288.78  4744.1  290.27  4749.6  285.46  4767.5  283.79
    4773  281.12  4781.6  280.91  4810.8  278.27    4827  278.19  4952.9  278.04
  4970.6  279.17  4990.7  278.19  4997.7  275.25  5000.4  274.75  5003.7  275.25
  5010.6  278.26  5019.8  278.88  5041.1  280.98  5081.8  284.16  5105.1  288.03
  5112.1  292.02  5174.5  296.51  5232.4  297.72    5278  296.69  5385.8  300.57
#Mann= 6 ,-1 , 0
  4488.1     .12       0  4594.2     .05       0    4827     .12       0
  4997.7     .07       0  5003.7     .12       0  5019.8     .05       0
Bank Sta=4781.6,5041.1
XS Rating Curve= 0 ,0
Exp/Cntr=0.3,0.1

Type RM Length L Ch R = 1 ,717     ,52,52,52
BEGIN DESCRIPTION:
Mapping XS ddf2a8e3
END DESCRIPTION:
XS GIS Cut Line= 6
      3703486.85     10643949.71       3703391.8     10643687.98
      3703370.96     10643608.55      3703257.68     10643553.87
      3703070.18     10643561.68      3702777.24     10643669.74
#Sta/Elev= 30
    4431  299.23  4686.3  290.35  4696.2  288.49  4705.6  290.64  4727.9  290.44
  4740.6  288.14  4789.3  290.13  4850.3  290.01  4858.2  288.23  4864.3   289.9
  4882.5  286.95  4887.9  289.16  4904.8  289.08  4912.1  285.76  4915.8  288.88
  4945.7  286.89  4958.8  283.35  4965.8   277.1  4992.8  275.79  4995.5  275.29
  4998.8  275.79  5016.8  278.13  5025.8  284.18  5029.6  285.13  5045.9  287.54
  5096.2  287.92  5144.1  297.87  5169.2  299.75  5321.4  298.58  5417.9  301.08
#Mann= 6 ,-1 , 0
    4431     .12       0  4686.3     .05       0  4789.3     .12       0
  4992.8     .07       0  4998.8     .12       0  5029.6     .05       0
Bank Sta=4958.8,5025.8
XS Rating Curve= 0 ,0
Exp/Cntr=0.3,0.1

Type RM Length L Ch R = 1 ,665     ,453,453,453
BEGIN DESCRIPTION:
Mapping XS eda016e4
END DESCRIPTION:
XS GIS Cut Line= 6
       3703511.6     10643893.74      3703432.16     10643603.35
      3703341.02     10643525.22      3703150.91     10643499.18
      3703070.18      10643514.8      3702760.31     10643650.21
#Sta/Elev= 30
  4423.6  297.48  4624.3  293.24  4634.5  292.41  4639.7  284.95    4645  283.62
  4674.2   283.3  4679.4  281.44  4686.5  281.47  4696.8  279.16  4707.2  278.76
  4750.2  280.02  4756.8  278.77  4807.1  278.64  4813.8  280.25  4820.4  278.61
  4828.1  279.63  4834.7  278.61  4948.3  281.84  4960.2  280.89  4985.4  274.21
  4988.1  273.71  4991.4  274.21  5047.1  280.14  5099.6  284.52  5140.9   292.4
  5146.4  292.29  5152.8  295.55  5216.6  301.99  5349.9  299.47  5457.6  301.17
#Mann= 4 ,-1 , 0
  4423.6     .12       0  4985.4     .07       0  4991.4     .12       0
  5047.1     .05       0
Bank Sta=4686.5,5047.1
XS Rating Curve= 0 ,0
Exp/Cntr=0.3,0.1

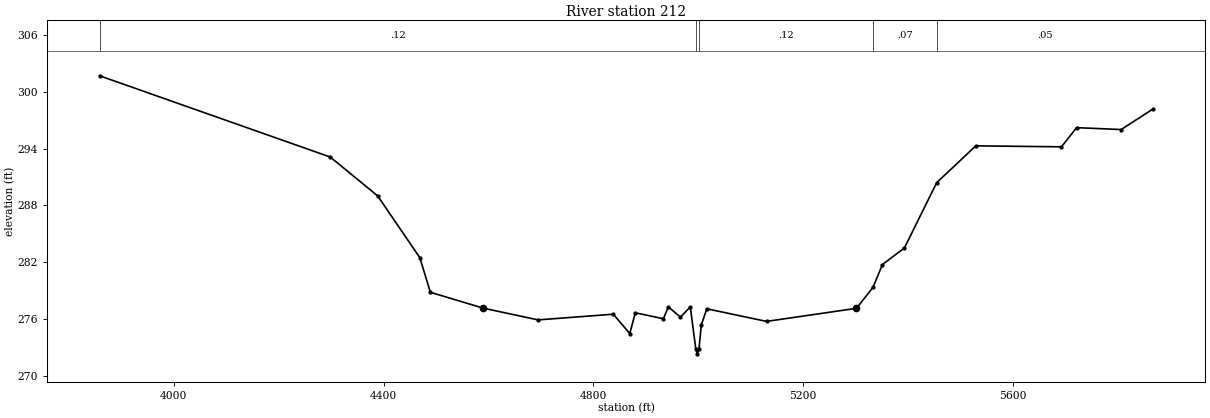
Type RM Length L Ch R = 1 ,212     ,0,0,0
BEGIN DESCRIPTION:
UNT 03326 IN LACR 1.0
END DESCRIPTION:
XS GIS Cut Line= 4
      3703551.31       10644078.      3703467.97     10643174.31
      3703129.43     10643067.54      3702665.88     10643650.88
#Sta/Elev= 30
  3858.6  301.67  4298.3   293.1  4388.7     289    4469  282.49  4489.1  278.84
  4589.7  277.17  4694.4  275.93  4837.8  276.53  4869.3  274.49  4879.7  276.68
  4933.4  276.05  4942.7  277.31  4965.8  276.22  4984.6   277.3  4995.1  272.85
  4997.9  272.35  5001.1  272.85  5005.6   275.4  5016.1   277.1  5129.9  275.77
  5301.3  277.15  5332.8  279.35  5350.9  281.77  5392.7  283.51  5454.3   290.4
  5528.8  294.28  5692.2  294.18    5721   296.2  5805.9     296  5866.2  298.15
#Mann= 5 ,-1 , 0
  3858.6     .12       0  4995.1     .07       0  5001.1     .12       0
  5332.8     .07       0  5454.3     .05       0
Bank Sta=4589.7,5301.3
XS Rating Curve= 0 ,0
Exp/Cntr=0.3,0.1

Chan Stop Cuts=-1
Use User Specified Reach Order=0
Composite Channel Slope=5