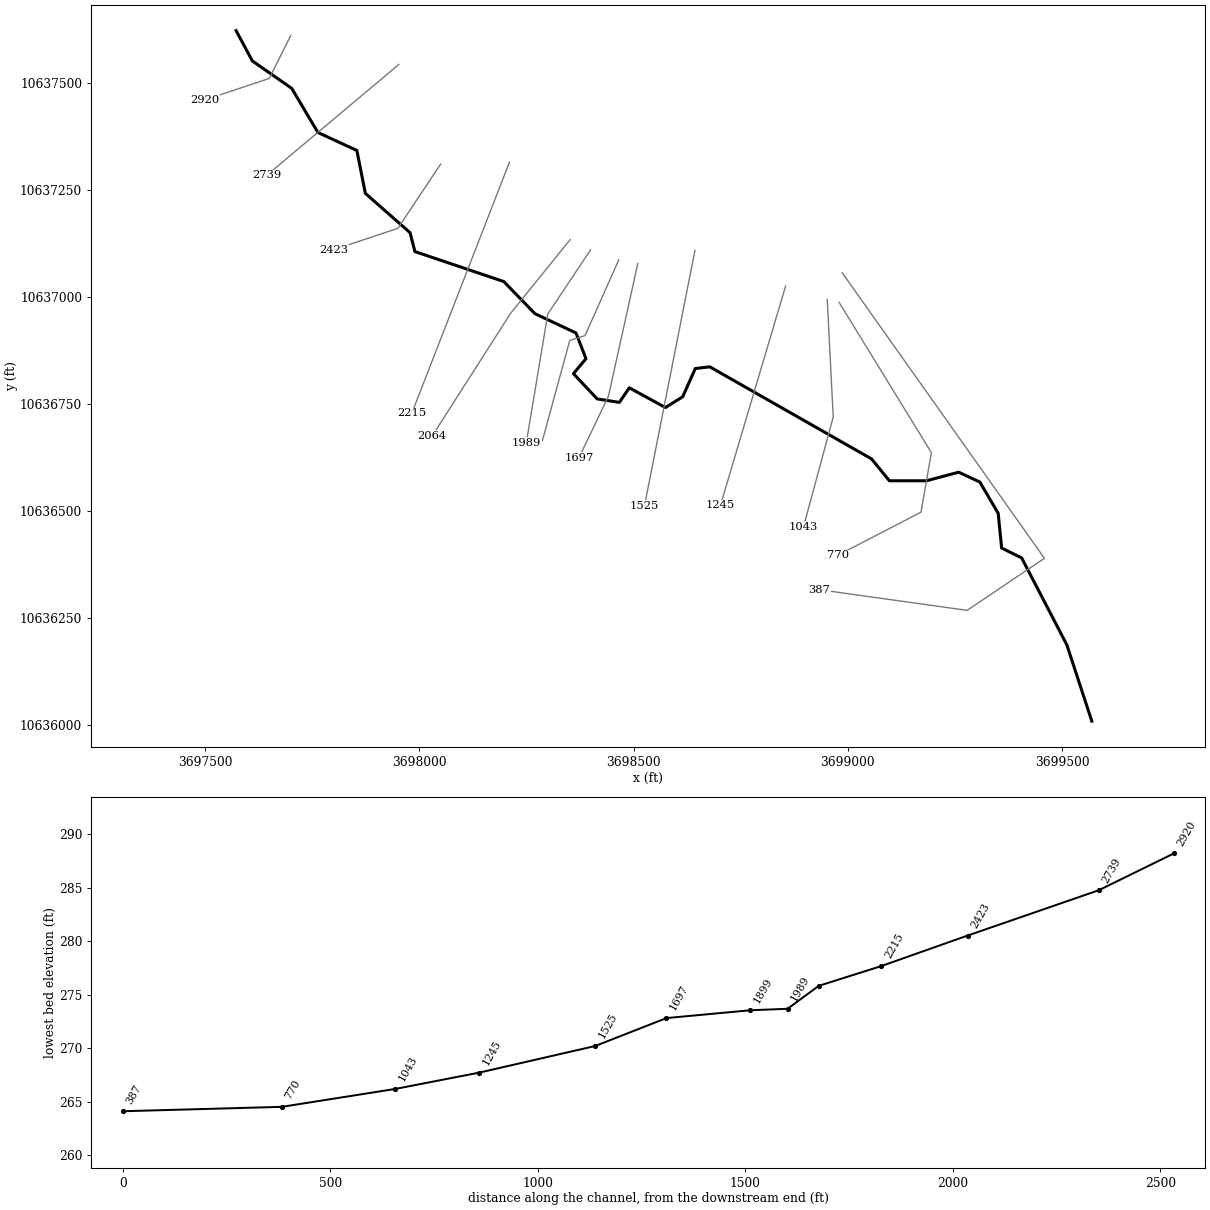
--- UNT 03338 IN LACR.prj (project) ---

Proj Title=UNT 03338 IN LACR Base Level Engineering
Current Plan=p01
Default Exp/Contr=0.3,0.1
English Units
Geom File=g01
Flow File=f01
Plan File=p01
Y Axis Title=Elevation
X Axis Title(PF)=Main Channel Distance
X Axis Title(XS)=Station
BEGIN DESCRIPTION:
UNT 03338 IN LACR
END DESCRIPTION:
DSS Export Rating Curves= 0
DSS Export Rating Curve Sorted= 0
DSS Export Volume Flow Curves= 0
DXF OffsetX= 0
DXF OffsetY= 0
DXF ScaleX= 1
DXF ScaleY= 10

--- UNT 03338 IN LACR.p01 (plan) ---

Plan Title=Multiple Run
Short Identifier=Multiple
Geom File=g01
Flow File=f01
Subcritical Flow
K Sum by GR= 0
Std Step Tol= 0.01
Critical Tol= 0.01
Num of Std Step Trials= 20
Max Error Tol= 0.3
Flow Tol Ratio= 0.001
Split Flow NTrial= 30
Split Flow Tol= 0.02
Split Flow Ratio= 0.02
Log Output Level= 0
Friction Slope Method= 1
Unsteady Friction Slope Method= 2
Unsteady Bridges Friction Slope Method= 1
Parabolic Critical Depth
Global Vel Dist=  1 , 1 , 1
Global Log Level= 0
CheckData=True
Encroach Param= -1, 0, 0, 0
BEGIN DESCRIPTION:
Multiple Run
END DESCRIPTION:

--- UNT 03338 IN LACR.f01 (steady flow) ---

Flow Title=Multiple
Program Version=4.10
Number of Profiles= 7
Profile Names=10-year,25-year,50-year,1pct_min,100-year,1pct_plu,500-year
River Rch & RM=UNT 03338 IN LAC,Reach-1         ,2920
     204     259     302     260     351     475     476
Boundary for River Rch & Prof#=UNT 03338 IN LAC,Reach-1         , 1
Up Type= 0
Dn Type= 3
Dn Slope=0.0009
Boundary for River Rch & Prof#=UNT 03338 IN LAC,Reach-1         , 2
Up Type= 0
Dn Type= 3
Dn Slope=0.0009
Boundary for River Rch & Prof#=UNT 03338 IN LAC,Reach-1         , 3
Up Type= 0
Dn Type= 3
Dn Slope=0.0009
Boundary for River Rch & Prof#=UNT 03338 IN LAC,Reach-1         , 4
Up Type= 0
Dn Type= 3
Dn Slope=0.0009
Boundary for River Rch & Prof#=UNT 03338 IN LAC,Reach-1         , 5
Up Type= 0
Dn Type= 3
Dn Slope=0.0009
Boundary for River Rch & Prof#=UNT 03338 IN LAC,Reach-1         , 6
Up Type= 0
Dn Type= 3
Dn Slope=0.0009
Boundary for River Rch & Prof#=UNT 03338 IN LAC,Reach-1         , 7
Up Type= 0
Dn Type= 3
Dn Slope=0.0009
DSS Import GetInterval= 0
DSS Import GetPeak= 0
DSS Import FillOption= 0

--- UNT 03338 IN LACR.g01 (geometry) ---

Geom Title=Existing Conditions
Program Version=4.10

River Reach=UNT 03338 IN LAC,Reach-1
Reach XY= 30
      3697572.04     10637621.82        3697610.       10637551.
        3697702.       10637487.        3697763.       10637384.
        3697854.       10637342.      3697873.75       10637242.
      3697978.25       10637150.       3697989.5       10637106.
        3698197.       10637036.      3698269.75       10636961.
       3698365.5       10636916.      3698388.75       10636856.
       3698359.5       10636821.       3698414.9     10636762.11
      3698466.75       10636754.        3698490.       10636788.
      3698574.25       10636742.       3698614.5       10636767.
        3698644.       10636833.      3698677.75       10636837.
       3699055.5       10636622.        3699097.       10636571.
       3699183.5       10636571.      3699258.75       10636591.
      3699308.25       10636568.        3699351.       10636495.
        3699359.       10636414.      3699405.75       10636391.
      3699511.25       10636188.       3699569.5       10636010.

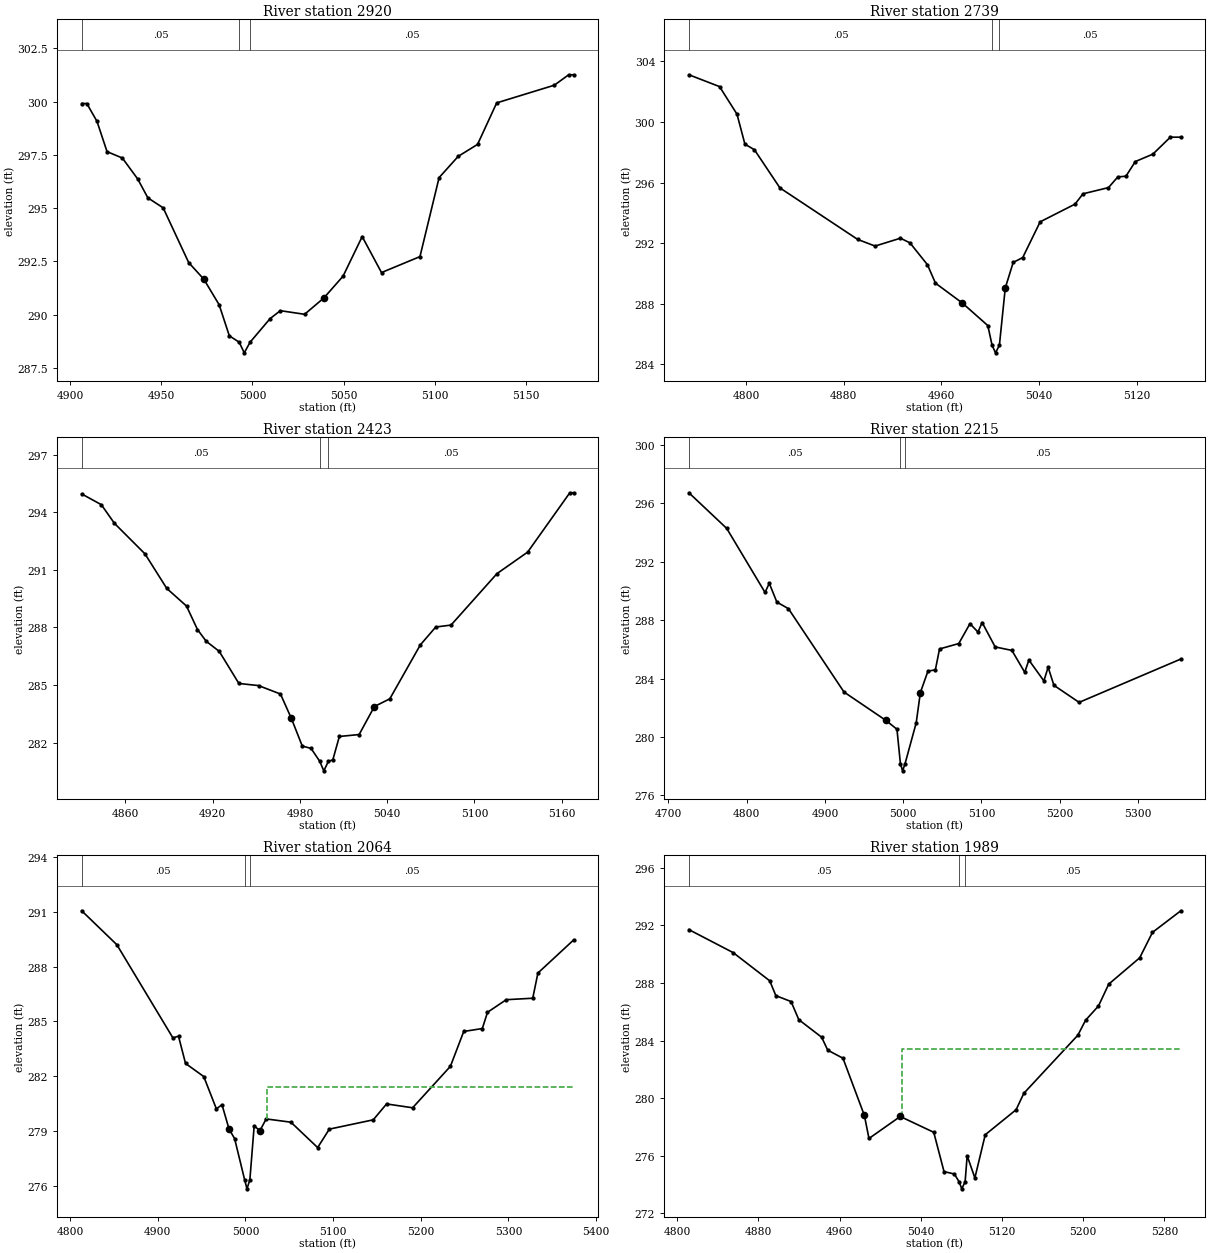
Type RM Length L Ch R = 1 ,2920    ,181,181,181
BEGIN DESCRIPTION:
UNT 03338 IN LACR 5.0
END DESCRIPTION:
XS GIS Cut Line= 3
      3697699.59     10637610.16      3697649.61     10637510.19
      3697499.59     10637460.18
#Sta/Elev= 30
  4906.3  299.91  4909.1  299.91  4914.7  299.07  4920.2  297.65  4928.6  297.35
    4937  296.37  4942.6  295.48    4951  295.01    4965  292.44  4973.3  291.66
  4981.7  290.46  4987.3     289  4992.7   288.7  4995.5   288.2  4998.7   288.7
  5009.7  289.81  5015.3  290.18  5028.6  290.01  5039.2  290.78  5049.7   291.8
  5060.2  293.66  5070.8  291.97  5091.9  292.72  5102.4  296.43  5112.9  297.43
  5123.5  297.99    5134  299.94  5165.6  300.77  5173.5  301.26  5176.2  301.26
#Mann= 3 ,-1 , 0
  4906.3     .05       0  4992.7     .03       0  4998.7     .05       0
Bank Sta=4973.3,5039.2
XS Rating Curve= 0 ,0
Exp/Cntr=0.3,0.1

Type RM Length L Ch R = 1 ,2739    ,316,316,316
BEGIN DESCRIPTION:
Mapping XS 41b237c9
END DESCRIPTION:
XS GIS Cut Line= 2
      3697952.04     10637542.85      3697643.18     10637283.66
#Sta/Elev= 30
  4753.1  303.12  4778.2  302.34  4792.5  300.52    4799  298.54  4806.8  298.17
  4827.7  295.65  4891.4  292.25  4905.7  291.81  4926.5  292.33  4934.3  292.02
  4948.6  290.58  4955.2  289.36  4977.2  288.05  4998.1  286.56  5001.6  285.26
  5004.4  284.76  5007.6  285.26  5012.4  289.04  5018.9  290.73  5026.7  291.05
    5041  293.41  5069.6  294.58  5076.1  295.26    5097  295.67  5104.7  296.38
  5111.3  296.42    5119  297.39  5133.4  297.88  5147.7     299  5156.3     299
#Mann= 3 ,-1 , 0
  4753.1     .05       0  5001.6     .03       0  5007.6     .05       0
Bank Sta=4977.2,5012.4
XS Rating Curve= 0 ,0
Exp/Cntr=0.3,0.1

Type RM Length L Ch R = 1 ,2423    ,208,208,208
BEGIN DESCRIPTION:
UNT 03338 IN LACR 4.0
END DESCRIPTION:
XS GIS Cut Line= 3
      3698049.58     10637310.15      3697949.61     10637160.19
      3697799.65      10637110.2
#Sta/Elev= 30
  4829.9  294.95  4843.4  294.39  4852.4  293.42  4873.4  291.83  4888.4  290.03
    4902  289.11  4909.5  287.89  4915.5  287.28  4924.5  286.75    4938  285.08
  4951.5  284.97  4966.6  284.53  4974.1  283.26  4981.6  281.82  4987.6   281.7
  4993.6  281.03  4996.4  280.53  4999.6  281.03  5002.6   281.1  5007.1  282.32
  5020.7  282.42  5031.2  283.88  5041.8  284.28  5062.8  287.09  5073.4  288.02
  5083.9  288.12  5115.5   290.8  5136.6  291.92  5165.6  295.01  5168.2  295.01
#Mann= 3 ,-1 , 0
  4829.9     .05       0  4993.6     .03       0  4999.6     .05       0
Bank Sta=4974.1,5031.2
XS Rating Curve= 0 ,0
Exp/Cntr=0.3,0.1

Type RM Length L Ch R = 1 ,2215    ,151,151,151
BEGIN DESCRIPTION:
Mapping XS cb676b80
END DESCRIPTION:
XS GIS Cut Line= 2
      3698210.26     10637314.94      3697982.39     10636728.99
#Sta/Elev= 30
  4726.2  296.73  4774.5  294.29  4823.5   289.9  4828.9  290.53  4838.6  289.24
  4853.4  288.79  4924.4  283.08  4978.1  281.13  4992.1  280.53  4996.5  278.18
  4999.3  277.68  5002.5  278.18  5016.7  280.97    5022  283.04  5031.7  284.51
  5041.2   284.6  5046.5  286.03  5071.1   286.4  5085.4  287.76  5095.6  287.19
    5101  287.84  5117.6  286.17    5139  285.93  5155.4  284.43  5160.7  285.27
  5179.9  283.84  5185.3  284.78  5192.7  283.54  5224.9  282.37  5354.9  285.34
#Mann= 3 ,-1 , 0
  4726.2     .05       0  4996.5     .03       0  5002.5     .05       0
Bank Sta=4978.1,5022
XS Rating Curve= 0 ,0
Exp/Cntr=0.3,0.1

Type RM Length L Ch R = 1 ,2064    ,75,75,75
BEGIN DESCRIPTION:
Mapping XS cc35468c
END DESCRIPTION:
XS GIS Cut Line= 3
      3698351.81     10637133.83      3698212.94     10636961.98
      3698029.76     10636675.48
#Sta/Elev= 30
  4813.3  291.06  4853.4   289.2  4917.3   284.1  4923.7  284.19  4931.7   282.7
  4952.5  281.98  4966.9  280.21  4973.3  280.44  4981.3  279.11  4987.7  278.58
  4999.1  276.33  5001.8  275.83  5005.1  276.33    5010  279.28  5016.5  279.01
  5023.7  279.66  5051.9  279.48  5082.4  278.09  5095.7   279.1  5145.8  279.61
    5161  280.48  5190.7  280.27  5233.8  282.54    5249  284.45  5270.2  284.61
  5276.1   285.5  5297.5  286.19  5327.7  286.27  5333.6  287.65  5374.3  289.46
#Mann= 3 ,-1 , 0
  4813.3     .05       0  4999.1     .03       0  5005.1     .05       0
#XS Ineff= 2 , 0
                         5024.37          281.41
Permanent Ineff=
       F       F
Bank Sta=4981.3,5016.5
XS Rating Curve= 0 ,0
Exp/Cntr=0.3,0.1

Type RM Length L Ch R = 1 ,1989    ,90,90,90
BEGIN DESCRIPTION:
UNT 03338 IN LACR 3.0
END DESCRIPTION:
XS GIS Cut Line= 3
       3698399.6     10637110.18      3698299.61     10636960.19
      3698249.61     10636660.19
#Sta/Elev= 30
  4811.7  291.71  4855.3  290.11  4891.3  288.15  4897.3  287.12  4912.3  286.71
  4919.9  285.45  4942.4  284.23  4948.4  283.33  4963.4  282.77  4984.5  278.79
    4989  277.19  5019.8  278.72  5052.8  277.62  5062.9  274.89  5073.1  274.72
  5077.7  274.19  5080.4  273.69  5083.7  274.19  5085.7  275.99  5093.3  274.45
  5103.5  277.45  5133.9  279.19  5141.5  280.33  5194.7  284.37  5202.3  285.41
    5215   286.4  5225.1  287.92  5255.6  289.75  5268.2  291.52  5296.1  293.02
#Mann= 3 ,-1 , 0
  4811.7     .05       0  5077.7     .03       0  5083.7     .05       0
#XS Ineff= 2 , 0
                         5021.62          283.38
Permanent Ineff=
       F       F
Bank Sta=4984.5,5019.8
XS Rating Curve= 0 ,0
Exp/Cntr=0.3,0.1

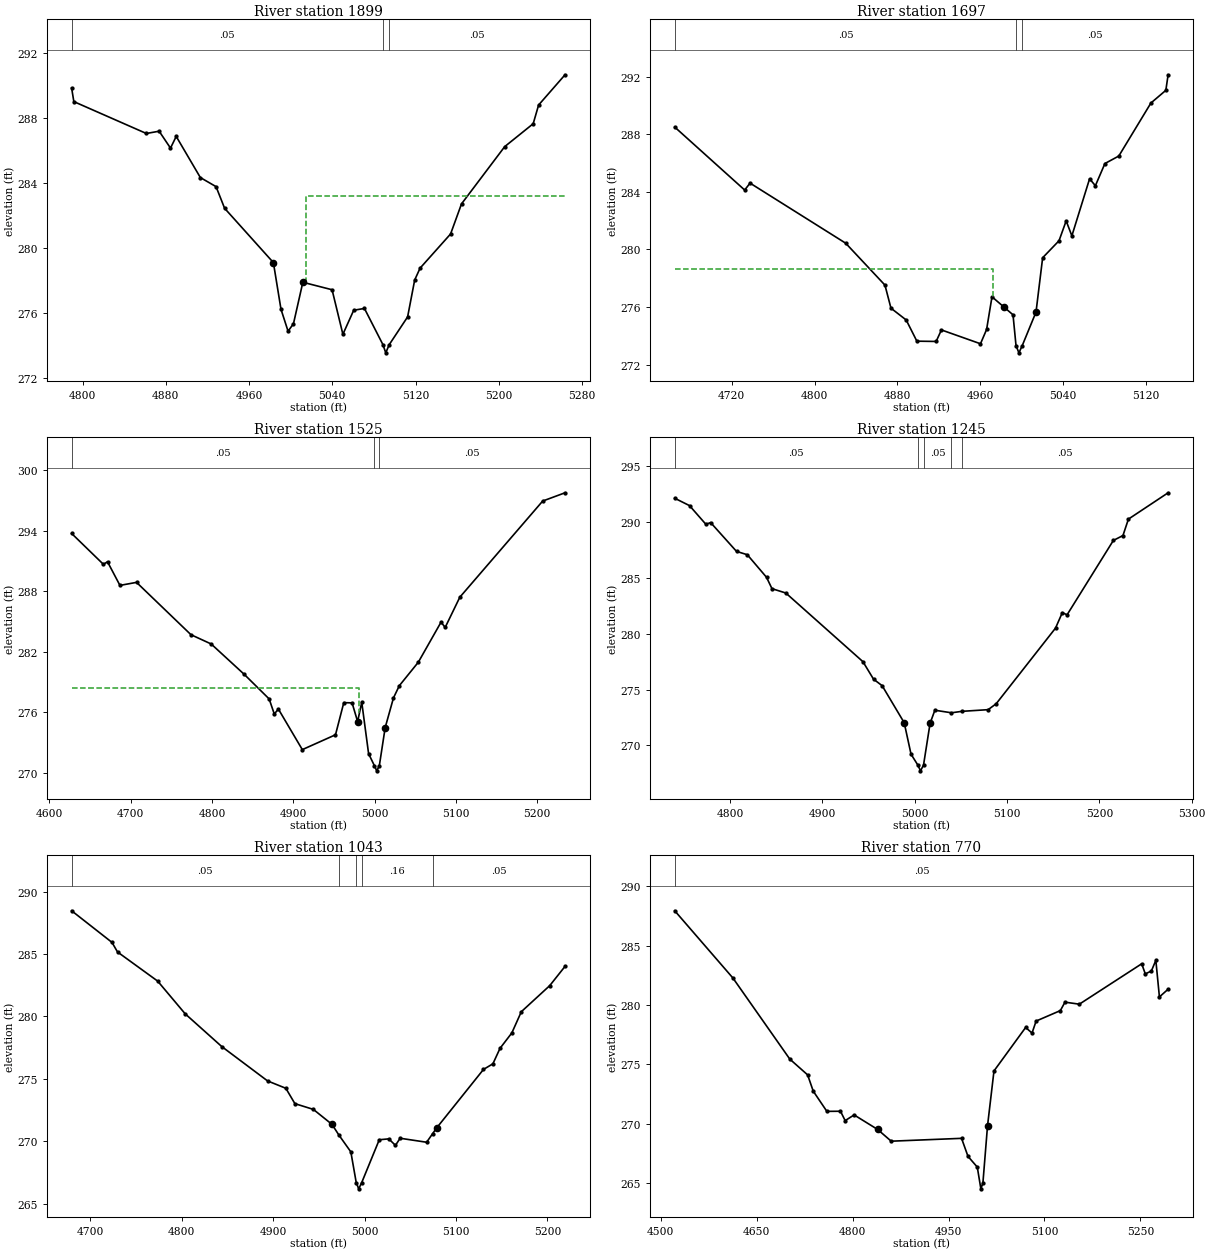
Type RM Length L Ch R = 1 ,1899    ,202,202,202
BEGIN DESCRIPTION:
Mapping XS c8e6294a
END DESCRIPTION:
XS GIS Cut Line= 4
      3698465.55     10637086.98      3698386.56      10636909.9
      3698350.97     10636898.61      3698286.97     10636664.23
#Sta/Elev= 30
  4789.5  289.83  4791.6     289  4861.3  287.04  4873.6  287.18  4884.5  286.14
    4890  286.86  4913.2  284.33  4928.3  283.77  4936.5  282.44  4983.4   279.1
  4990.7  276.23  4997.5  274.88  5002.7  275.34  5011.7  277.89  5039.8  277.43
  5050.2  274.69  5060.6  276.17  5070.9  276.28  5088.7  274.05  5091.4  273.55
  5094.7  274.05  5112.4  275.76  5119.2  278.03  5124.4  278.76  5153.7  280.86
  5164.2  282.71  5205.7  286.23  5233.1  287.64  5238.3  288.79  5263.7  290.65
#Mann= 3 ,-1 , 0
  4789.5     .05       0  5088.7     .03       0  5094.7     .05       0
#XS Ineff= 2 , 0
                          5014.7           283.2
Permanent Ineff=
       F       F
Bank Sta=4983.4,5011.7
XS Rating Curve= 0 ,0
Exp/Cntr=0.3,0.1

Type RM Length L Ch R = 1 ,1697    ,172,172,172
BEGIN DESCRIPTION:
Mapping XS 35b14f84
END DESCRIPTION:
XS GIS Cut Line= 3
      3698509.83     10637078.33      3698441.24      10636768.4
      3698372.68     10636625.19
#Sta/Elev= 30
  4665.1  288.49  4732.6  284.12  4737.8   284.6  4830.1  280.43    4868  277.52
  4873.8  275.92  4888.5   275.1  4898.8  273.63  4917.4  273.61  4922.5  274.41
  4960.2  273.45  4966.1  274.44  4971.3  276.71  4982.5  276.02  4991.6  275.46
  4994.5  273.32  4997.3  272.82  5000.5  273.32  5013.8  275.65  5020.2  279.42
    5036   280.6  5042.9  281.98  5048.4  280.94  5065.5   284.9  5071.1  284.42
  5080.3  285.96  5093.7  286.48  5124.7  290.16  5139.1  291.04  5141.3  292.12
#Mann= 3 ,-1 , 0
  4665.1     .05       0  4994.5     .03       0  5000.5     .05       0
#XS Ineff= 2 , 0
       0 4972.04  278.66               0
Permanent Ineff=
       F       F
Bank Sta=4982.5,5013.8
XS Rating Curve= 0 ,0
Exp/Cntr=0.3,0.1

Type RM Length L Ch R = 1 ,1525    ,280,280,280
BEGIN DESCRIPTION:
UNT 03338 IN LACR 2.0
END DESCRIPTION:
XS GIS Cut Line= 2
      3698643.16      10637108.5      3698525.49     10636513.22
#Sta/Elev= 30
  4627.4  293.71  4666.4  290.66  4671.5  290.91  4686.8  288.57  4707.2  288.87
  4774.1  283.69    4799  282.77  4839.7  279.76  4870.3  277.33  4876.6  275.84
  4881.7  276.32  4911.1  272.31  4951.9  273.78  4962.1  276.96  4972.3  276.94
  4979.1  275.09  4984.2     277  4992.6  271.91  4999.8  270.71  5002.6  270.21
  5005.8  270.71    5013  274.49  5023.2  277.43  5030.4  278.64  5053.8  280.97
  5081.7  284.93  5086.8  284.41  5104.8   287.4  5206.7  296.92  5234.2  297.74
#Mann= 3 ,-1 , 0
  4627.4     .05       0  4999.8     .03       0  5005.8     .05       0
#XS Ineff= 2 , 0
         4981.36  278.44
Permanent Ineff=
       F       F
Bank Sta=4979.1,5013
XS Rating Curve= 0 ,0
Exp/Cntr=0.3,0.1

Type RM Length L Ch R = 1 ,1245    ,202,202,202
BEGIN DESCRIPTION:
Mapping XS 0d102daf
END DESCRIPTION:
XS GIS Cut Line= 2
      3698854.81     10637025.51      3698702.55     10636513.36
#Sta/Elev= 30
  4740.2  292.14  4756.2  291.48  4773.9  289.81  4779.1  289.96  4807.1  287.38
  4818.8  287.08  4839.6  285.06  4845.5  284.04  4860.5  283.65    4944   277.5
  4955.5  275.93  4964.8  275.35  4988.7  272.03  4996.1  269.21  5003.6  268.22
  5006.3  267.72  5009.6  268.22  5016.7  271.97  5021.9  273.15  5039.9  272.92
  5051.1  273.05  5079.6   273.2  5088.3  273.73  5152.6  280.51  5159.9  281.89
  5165.1   281.7  5215.2  288.36  5225.6   288.8  5231.5  290.27  5274.5  292.63
#Mann= 5 ,-1 , 0
  4740.2     .05       0  5003.6     .03       0  5009.6     .05       0
  5039.9     .16       0  5051.1     .05       0
Bank Sta=4988.7,5016.7
XS Rating Curve= 0 ,0
Exp/Cntr=0.3,0.1

Type RM Length L Ch R = 1 ,1043    ,273,273,273
BEGIN DESCRIPTION:
Mapping XS 6650e2ce
END DESCRIPTION:
XS GIS Cut Line= 3
      3698952.02     10636994.21      3698965.91     10636719.91
      3698896.75     10636464.04
#Sta/Elev= 30
  4679.5  288.46  4723.6  285.93  4729.7  285.16  4773.6  282.83  4803.7  280.21
  4843.7  277.59  4893.8  274.84  4913.8  274.25  4923.7  273.02  4943.9  272.56
  4964.3  271.36  4971.7  270.52  4984.9  269.16  4990.8   266.7  4993.5   266.2
  4996.8   266.7    5016  270.13  5026.4   270.2  5033.7  269.68  5038.8  270.25
  5067.8  269.93  5074.3  270.61  5078.7  271.07    5130  275.76  5140.3  276.21
  5148.1  277.45    5161  278.68  5171.4  280.38  5202.5  282.47  5219.2  284.01
#Mann= 5 ,-1 , 0
  4679.5     .05       0  4971.7     .16       0  4990.8     .07       0
  4996.8     .16       0  5074.3     .05       0
Bank Sta=4964.3,5078.7
XS Rating Curve= 0 ,0
Exp/Cntr=0.3,0.1

Type RM Length L Ch R = 1 ,770     ,383,383,383
BEGIN DESCRIPTION:
Mapping XS 10b3f451
END DESCRIPTION:
XS GIS Cut Line= 4
      3698979.77     10636987.31      3699195.07     10636636.57
      3699170.77     10636497.68      3698976.33       10636397.
#Sta/Elev= 30
  4521.9  287.93  4612.9  282.27  4701.8  275.45  4729.7  274.12  4738.5  272.75
  4759.8  271.05  4781.1  271.06  4788.4  270.27  4802.4  270.75  4839.1  269.53
  4860.4  268.54  4970.4  268.78  4980.5  267.26    4995  266.36  5000.6  264.53
  5003.8  265.03    5011  269.83  5021.1  274.45  5070.6  278.11  5080.6  277.64
    5087  278.65  5124.9  279.53  5132.1  280.24  5154.6  280.07  5252.1  283.47
  5257.7  282.62  5267.2  282.86  5274.2  283.76  5279.8  280.68  5293.4  281.33
#Mann= 1 ,-1 , 0
  4521.9     .05       0
Bank Sta=4839.1,5011
XS Rating Curve= 0 ,0
Exp/Cntr=0.3,0.1

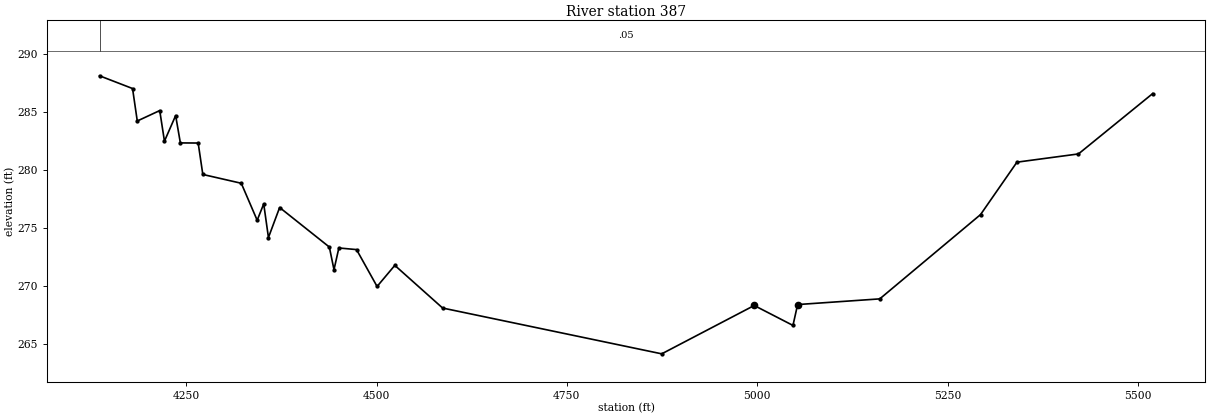
Type RM Length L Ch R = 1 ,387     ,0,0,0
BEGIN DESCRIPTION:
UNT 03338 IN LACR 1.0
END DESCRIPTION:
XS GIS Cut Line= 4
      3698986.73     10637056.73      3699458.96     10636390.05
      3699278.41     10636268.52      3698932.91     10636316.89
#Sta/Elev= 30
  4136.1   288.1  4179.5     287  4185.7   284.2  4215.2   285.1  4221.4  282.46
  4236.1  284.67  4242.3  282.31  4265.7   282.3  4271.8  279.59  4322.3  278.83
  4343.2  275.64  4351.8  277.05    4358  274.15  4372.7  276.74    4438  273.33
  4444.1  271.38  4450.5  273.25  4473.7  273.11  4500.7  269.93    4524  271.75
  4586.8  268.07  4874.6  264.12  4996.1  268.29    5047  266.57  5053.1  268.37
    5161  268.86  5293.4  276.13  5341.2  280.65    5422  281.36  5519.6  286.57
#Mann= 1 ,-1 , 0
  4136.1     .05       0
Bank Sta=4996.1,5053.1
XS Rating Curve= 0 ,0
Exp/Cntr=0.3,0.1

Chan Stop Cuts=-1
Use User Specified Reach Order=0
Composite Channel Slope=5