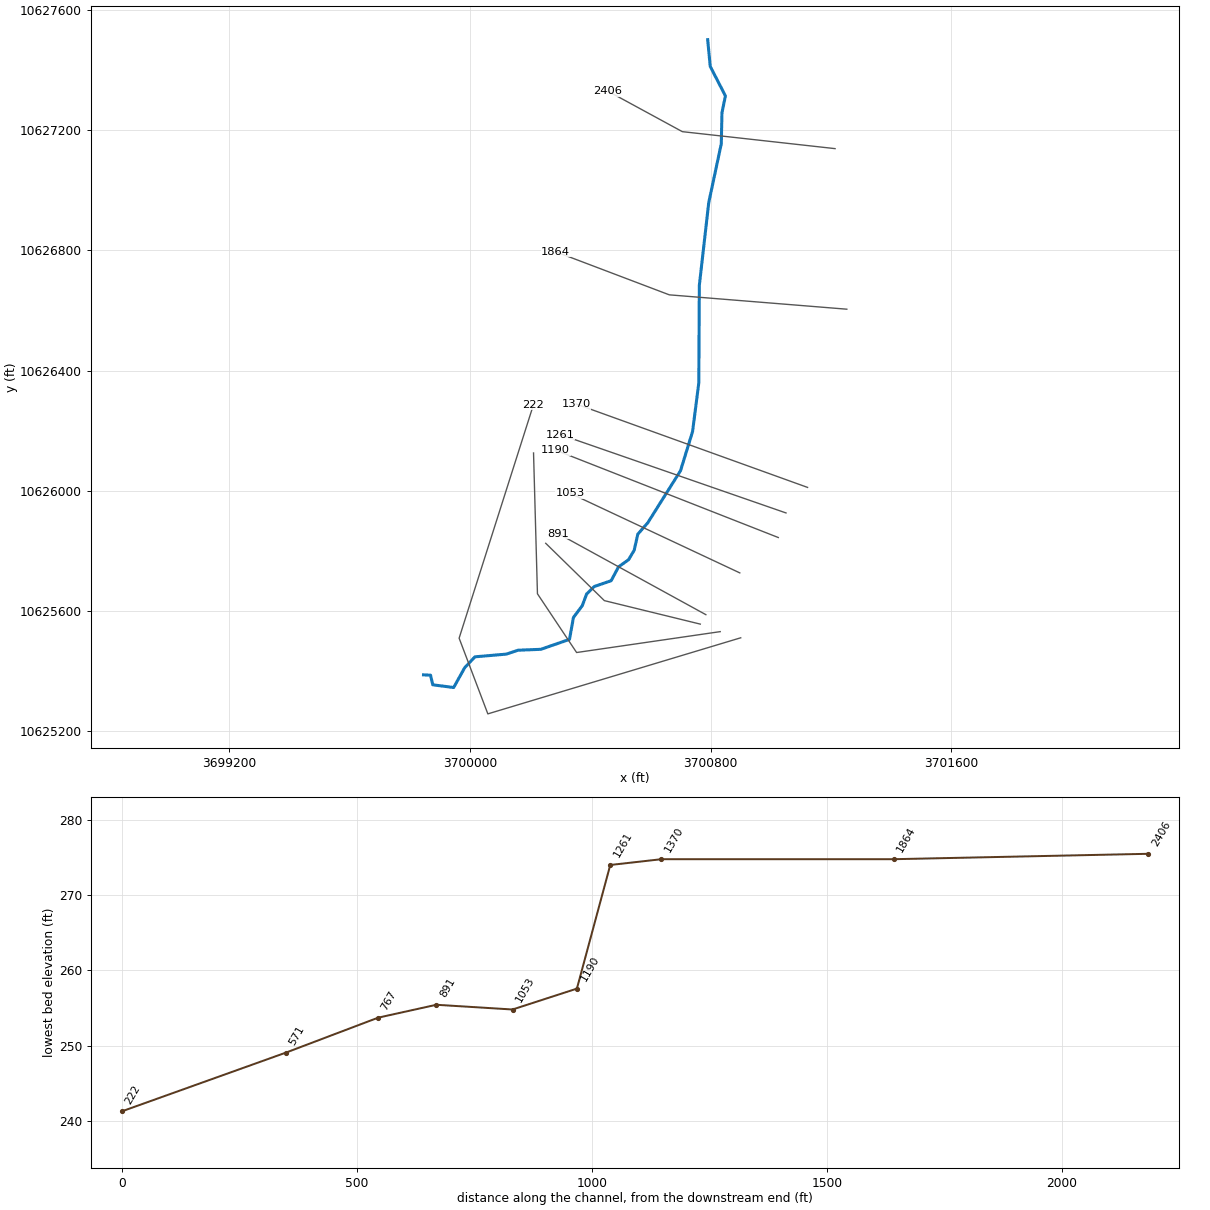
--- UNT 03345 IN LACR.prj (project) ---

Proj Title=UNT 03345 IN LACR Base Level Engineering
Current Plan=p01
Default Exp/Contr=0.3,0.1
English Units
Geom File=g01
Flow File=f01
Plan File=p01
Y Axis Title=Elevation
X Axis Title(PF)=Main Channel Distance
X Axis Title(XS)=Station
BEGIN DESCRIPTION:
UNT 03345 IN LACR
END DESCRIPTION:
DSS Export Rating Curves= 0
DSS Export Rating Curve Sorted= 0
DSS Export Volume Flow Curves= 0
DXF OffsetX= 0
DXF OffsetY= 0
DXF ScaleX= 1
DXF ScaleY= 10

--- UNT 03345 IN LACR.p01 (plan) ---

Plan Title=Multiple Run
Short Identifier=Multiple
Geom File=g01
Flow File=f01
Subcritical Flow
K Sum by GR= 0
Std Step Tol= 0.01
Critical Tol= 0.01
Num of Std Step Trials= 20
Max Error Tol= 0.3
Flow Tol Ratio= 0.001
Split Flow NTrial= 30
Split Flow Tol= 0.02
Split Flow Ratio= 0.02
Log Output Level= 0
Friction Slope Method= 1
Unsteady Friction Slope Method= 2
Unsteady Bridges Friction Slope Method= 1
Parabolic Critical Depth
Global Vel Dist=  1 , 1 , 1
Global Log Level= 0
CheckData=True
Encroach Param= -1, 0, 0, 0
BEGIN DESCRIPTION:
Multiple Run
END DESCRIPTION:

--- UNT 03345 IN LACR.f01 (steady flow) ---

Flow Title=Multiple
Program Version=4.10
Number of Profiles= 7
Profile Names=10-year,25-year,50-year,1pct_min,100-year,1pct_plu,500-year
River Rch & RM=UNT 03345 IN LAC,Reach-1         ,2406
     107     129     145     121     164     221     207
Boundary for River Rch & Prof#=UNT 03345 IN LAC,Reach-1         , 1
Up Type= 0
Dn Type= 3
Dn Slope=0.02
Boundary for River Rch & Prof#=UNT 03345 IN LAC,Reach-1         , 2
Up Type= 0
Dn Type= 3
Dn Slope=0.02
Boundary for River Rch & Prof#=UNT 03345 IN LAC,Reach-1         , 3
Up Type= 0
Dn Type= 3
Dn Slope=0.02
Boundary for River Rch & Prof#=UNT 03345 IN LAC,Reach-1         , 4
Up Type= 0
Dn Type= 3
Dn Slope=0.02
Boundary for River Rch & Prof#=UNT 03345 IN LAC,Reach-1         , 5
Up Type= 0
Dn Type= 3
Dn Slope=0.02
Boundary for River Rch & Prof#=UNT 03345 IN LAC,Reach-1         , 6
Up Type= 0
Dn Type= 3
Dn Slope=0.02
Boundary for River Rch & Prof#=UNT 03345 IN LAC,Reach-1         , 7
Up Type= 0
Dn Type= 3
Dn Slope=0.02
DSS Import GetInterval= 0
DSS Import GetPeak= 0
DSS Import FillOption= 0

--- UNT 03345 IN LACR.g01 (geometry) ---

Geom Title=Existing Conditions
Program Version=4.10

River Reach=UNT 03345 IN LAC,Reach-1
Reach XY= 30
      3700790.25       10627500.      3700798.75       10627411.
      3700849.25       10627313.      3700837.75       10627257.
       3700835.5       10627154.      3700793.75       10626958.
       3700762.5       10626683.      3700760.75       10626359.
        3700740.       10626197.        3700700.       10626067.
      3700591.25       10625894.        3700558.       10625856.
      3700545.75       10625802.      3700527.25       10625771.
      3700493.75       10625747.      3700469.25       10625701.
       3700413.5       10625682.      3700387.75       10625657.
      3700373.25       10625618.        3700344.       10625579.
      3700330.75       10625506.       3700235.5       10625473.
       3700159.5       10625470.       3700120.5       10625457.
      3700016.25       10625448.       3699982.5       10625412.
      3699945.75       10625346.      3699876.25       10625355.
      3699868.75       10625387.       3699845.5       10625388.

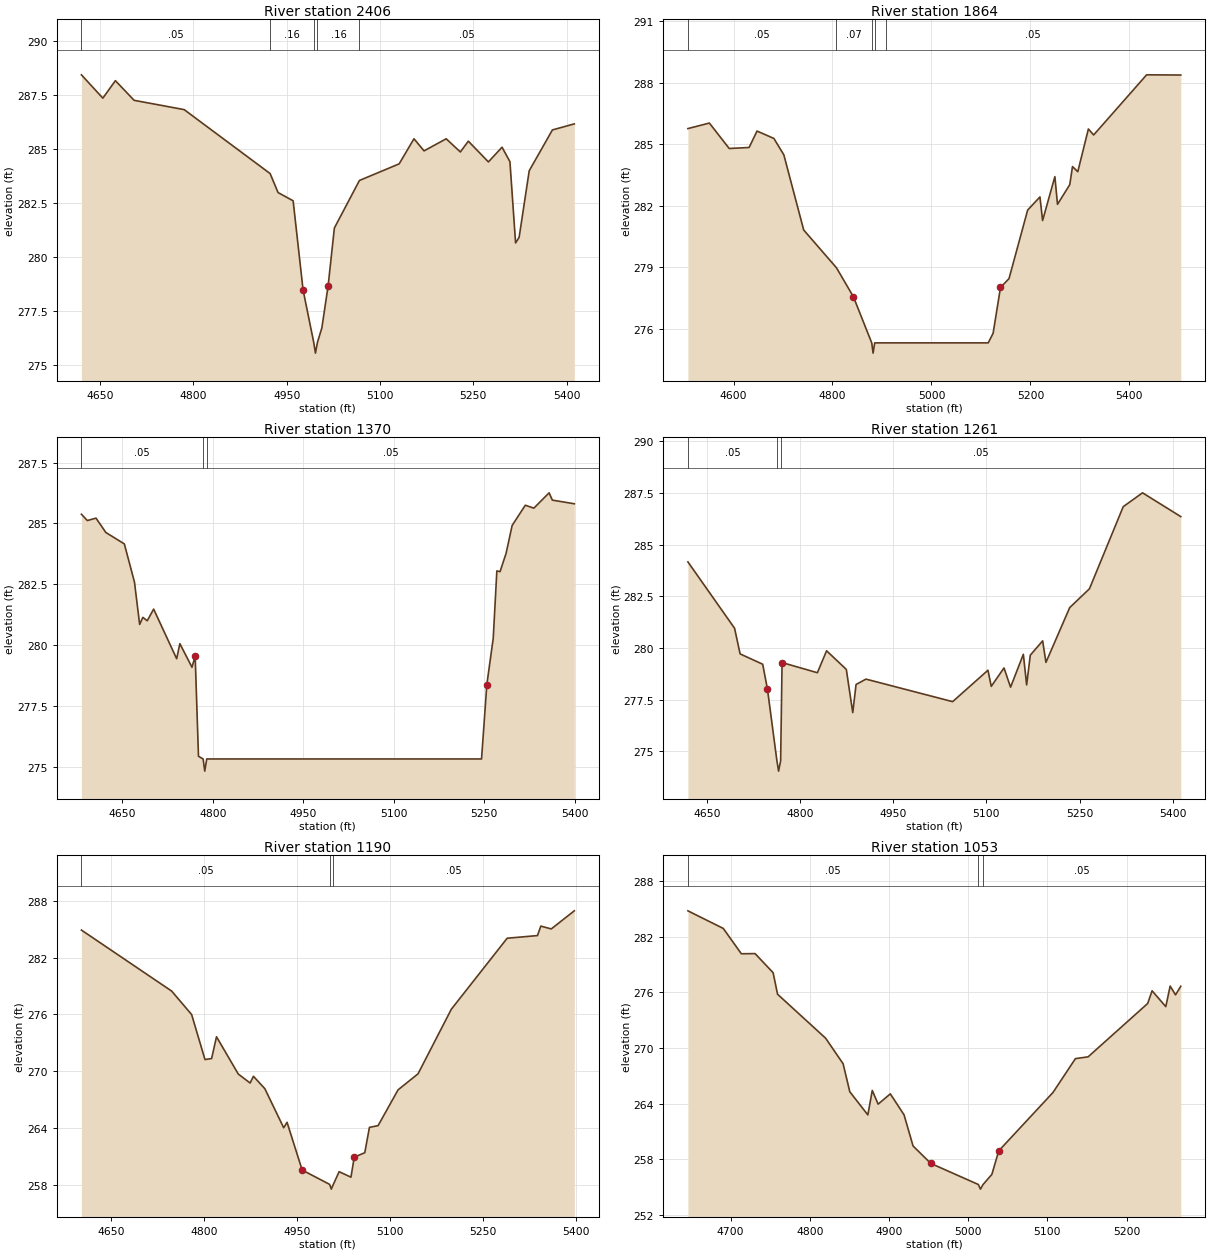
Type RM Length L Ch R = 1 ,2406    ,542,542,542
BEGIN DESCRIPTION:
UNT 03345 IN LACR 4.0
END DESCRIPTION:
XS GIS Cut Line= 3
      3701213.84      10627137.7      3700706.03     10627194.13
      3700458.68     10627328.65
#Sta/Elev= 30
  4619.9  288.42  4654.3  287.34  4674.5  288.15  4704.6  287.24  4785.1  286.81
  4923.3  283.85  4936.1  282.97  4960.3  282.59  4976.3  278.46  4993.4  276.04
  4996.2  275.54  4999.4  276.04  5006.5  276.71  5016.6  278.66  5026.6  281.33
  5066.9  283.53  5130.8   284.3  5154.6  285.46  5170.8   284.9  5206.4  285.46
  5229.2  284.85    5242  285.35  5274.3  284.39  5296.2  285.07  5308.9   284.4
    5318  280.64  5323.7   280.9  5339.9  283.98  5377.2  285.87  5412.4  286.15
#Mann= 5 ,-1 , 0
  4619.9     .05       0  4923.3     .16       0  4993.4     .07       0
  4999.4     .16       0  5066.9     .05       0
Bank Sta=4976.3,5016.6
XS Rating Curve= 0 ,0
Exp/Cntr=0.3,0.1

Type RM Length L Ch R = 1 ,1864    ,494,494,494
BEGIN DESCRIPTION:
UNT 03345 IN LACR 3.0
END DESCRIPTION:
XS GIS Cut Line= 3
      3701252.88     10626603.85      3700662.63     10626651.59
      3700285.06     10626794.81
#Sta/Elev= 30
  4507.8  285.76  4551.2  286.03  4591.3  284.79  4631.5  284.84  4647.5  285.64
  4681.6  285.28  4701.7  284.48  4741.8  280.82    4808  278.98  4842.2  277.57
  4879.3  275.32    4882  274.82  4885.3  275.32  4907.6  275.32  5114.7  275.32
  5124.6  275.79  5139.5  278.02  5156.7  278.45  5194.4  281.79  5219.2  282.43
  5224.6  281.28  5249.4  283.42  5254.7  282.07  5279.5  283.03    5285  283.91
  5295.7  283.66  5317.1  285.74  5327.8  285.45  5434.8  288.38  5503.8  288.37
#Mann= 5 ,-1 , 0
  4507.8     .05       0    4808     .07       0  4879.3    .033       0
  4885.3     .07       0  4907.6     .05       0
Bank Sta=4842.2,5139.5
XS Rating Curve= 0 ,0
Exp/Cntr=0.3,0.1

Type RM Length L Ch R = 1 ,1370    ,109,109,109
BEGIN DESCRIPTION:
UNT 03345 IN LACR 2.0
END DESCRIPTION:
XS GIS Cut Line= 2
      3701122.35     10626011.32      3700353.08     10626288.53
#Sta/Elev= 30
  4581.9  285.38  4591.7  285.12  4606.1  285.22  4622.4  284.63  4653.1  284.16
  4669.9  282.59  4678.5  280.85  4683.8  281.14  4691.1     281  4701.7  281.48
  4739.9  279.44  4745.2  280.06  4765.3  279.09  4770.6  279.55  4776.1  275.43
  4783.8  275.32  4786.5  274.82  4789.8  275.32  5245.7  275.32  5254.5  278.38
  5265.1  280.28  5271.1  283.05  5276.4  283.02  5286.4  283.77  5296.5  284.92
  5318.3  285.75  5332.5  285.63  5357.8  286.26  5363.2  285.96  5399.6  285.81
#Mann= 3 ,-1 , 0
  4581.9     .05       0  4783.8    .033       0  4789.8     .05       0
Bank Sta=4770.6,5254.5
XS Rating Curve= 0 ,0
Exp/Cntr=0.3,0.1

Type RM Length L Ch R = 1 ,1261    ,71,71,71
BEGIN DESCRIPTION:
Mapping XS 52489886
END DESCRIPTION:
XS GIS Cut Line= 2
      3701050.68     10625926.41      3700300.61     10626186.85
#Sta/Elev= 30
  4619.1  284.17  4694.3  280.96  4703.2  279.72  4739.6  279.22  4747.3  278.01
  4762.5  274.55  4765.2  274.05  4768.5  274.55  4770.8   279.3  4827.7  278.81
  4842.5  279.87  4874.3  278.97  4884.7  276.88    4890  278.24    4906   278.5
  5045.6  277.41  5102.5  278.93  5107.8  278.15  5128.3  279.04  5138.9  278.11
  5159.5   279.7  5164.8  278.22  5170.7  279.66  5190.6  280.35  5195.9  279.31
  5234.2  281.96    5266  282.87  5320.4  286.84  5351.5  287.51  5413.1  286.36
#Mann= 3 ,-1 , 0
  4619.1     .05       0  4762.5     .03       0  4768.5     .05       0
Bank Sta=4747.3,4770.8
XS Rating Curve= 0 ,0
Exp/Cntr=0.3,0.1

Type RM Length L Ch R = 1 ,1190    ,137,137,137
BEGIN DESCRIPTION:
Mapping XS 3da38845
END DESCRIPTION:
XS GIS Cut Line= 2
      3701025.08     10625844.67      3700284.96     10626135.18
#Sta/Elev= 30
  4602.4   284.9  4747.9  278.47  4780.2  275.99  4801.7  271.25  4812.4  271.35
  4820.3  273.65  4855.4  269.72  4874.5  268.77  4879.9  269.48  4898.3  268.17
  4928.7  264.05  4934.1  264.63  4958.5  259.59  5002.8  258.08  5005.5  257.58
  5008.8  258.08  5018.1  259.42  5037.2  258.84  5042.5  260.95  5059.5  261.42
    5067  264.09    5081  264.28  5113.2  268.05  5145.4  269.74  5199.1  276.55
  5289.2  284.04  5338.1  284.32  5343.5  285.32  5360.3  285.02  5397.5  286.93
#Mann= 3 ,-1 , 0
  4602.4     .05       0  5002.8     .03       0  5008.8     .05       0
Bank Sta=4958.5,5042.5
XS Rating Curve= 0 ,0
Exp/Cntr=0.3,0.1

Type RM Length L Ch R = 1 ,1053    ,162,162,162
BEGIN DESCRIPTION:
Mapping XS 54c3b8c0
END DESCRIPTION:
XS GIS Cut Line= 2
      3700897.01     10625727.11      3700333.65     10625991.45
#Sta/Elev= 30
  4646.2   284.8  4690.9   282.9  4713.7  280.17    4731  280.19  4753.8  278.13
  4759.4  275.81  4820.1  271.07  4842.2  268.31  4850.6   265.3  4873.4   262.8
    4879  265.44  4886.4  263.96  4901.8  265.07  4919.1  262.81  4930.5  259.45
  4952.9  257.57  5012.9   255.3  5015.6   254.8  5018.9   255.3    5030  256.39
  5038.7  258.93  5107.1  265.21  5135.5  268.87  5151.5  269.06  5226.7  274.81
  5232.3  276.18  5249.6  274.47  5255.1  276.69  5261.9  275.74  5268.5  276.67
#Mann= 3 ,-1 , 0
  4646.2     .05       0  5012.9     .03       0  5018.9     .05       0
Bank Sta=4952.9,5038.7
XS Rating Curve= 0 ,0
Exp/Cntr=0.3,0.1

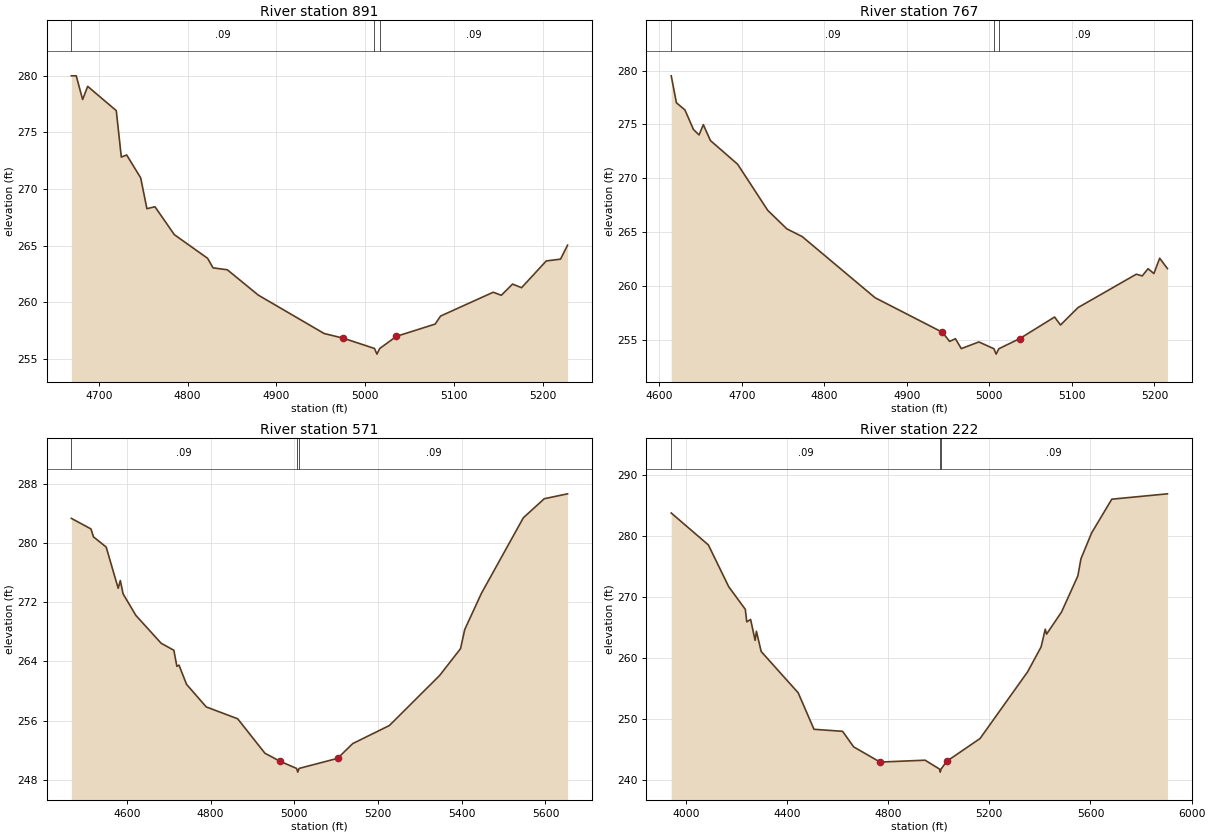
Type RM Length L Ch R = 1 ,891     ,124,124,124
BEGIN DESCRIPTION:
Mapping XS 904c8e7c
END DESCRIPTION:
XS GIS Cut Line= 2
      3700784.19      10625588.2       3700294.2     10625857.05
#Sta/Elev= 30
  4669.1  279.98  4674.6  279.98  4681.8  277.89  4687.5  279.05  4719.7  276.91
  4725.4  272.81  4731.4     273  4747.2  270.98  4754.2  268.26  4763.3  268.43
  4785.1  265.97  4822.6  263.88  4828.7  263.04  4844.8  262.87  4879.6  260.64
  4953.8  257.25  4975.6  256.83  5010.5  255.93  5013.3  255.43  5016.5  255.93
  5035.3     257  5078.9  258.08    5085  258.79  5144.3  260.89  5153.4  260.62
  5166.1  261.61  5176.2  261.29    5204  263.65  5220.1  263.81    5228  265.04
#Mann= 3 ,-1 , 0
  4669.1     .09       0  5010.5     .06       0  5016.5     .09       0
Bank Sta=4975.6,5035.3
XS Rating Curve= 0 ,0
Exp/Cntr=0.3,0.1

Type RM Length L Ch R = 1 ,767     ,196,196,196
BEGIN DESCRIPTION:
Mapping XS 05486494
END DESCRIPTION:
XS GIS Cut Line= 3
      3700765.74     10625556.77      3700446.72     10625634.89
      3700251.77     10625825.51
#Sta/Elev= 30
  4614.6  279.51  4620.9  277.01  4631.2  276.35  4641.5  274.54  4648.3  274.03
  4653.5  274.98  4662.1  273.51  4695.1  271.31  4731.5  267.04  4754.7  265.32
  4773.2  264.61  4861.5  258.94    4943  255.74  4951.9  254.89  4958.9  255.14
    4966  254.22  4987.2  254.84  5005.5  254.21  5008.2  253.71  5011.5  254.21
  5036.8  255.15    5079  257.15  5086.2  256.41  5107.3  258.02    5178  261.12
  5185.2  260.96  5192.2  261.63  5199.3  261.18  5206.3   262.6  5215.7  261.64
#Mann= 3 ,-1 , 0
  4614.6     .09       0  5005.5     .06       0  5011.5     .09       0
Bank Sta=4943,5036.8
XS Rating Curve= 0 ,0
Exp/Cntr=0.3,0.1

Type RM Length L Ch R = 1 ,571     ,349,349,349
BEGIN DESCRIPTION:
Mapping XS 3e6b197e
END DESCRIPTION:
XS GIS Cut Line= 4
      3700831.93      10625531.8      3700354.47     10625462.35
      3700224.26     10625657.67      3700211.26     10626125.77
#Sta/Elev= 30
  4467.3  283.31  4514.2  281.88  4520.2  280.81  4550.5  279.44  4579.2  273.87
  4584.3  274.92  4590.9  273.13  4621.2  270.23  4681.9  266.45  4712.2  265.51
  4719.4  263.34  4724.5   263.5  4742.5  260.91  4789.6  257.86  4864.7  256.26
  4929.8  251.61  4966.4  250.51  5005.4  249.56  5008.2  249.06  5011.4  249.56
  5103.4  250.92  5139.5  252.91  5227.1  255.35  5347.1   262.1  5397.1  265.72
  5407.1   268.3  5447.1   273.2  5547.2  283.39  5597.2  285.96  5652.8  286.62
#Mann= 3 ,-1 , 0
  4467.3     .09       0  5005.4     .06       0  5011.4     .09       0
Bank Sta=4966.4,5103.4
XS Rating Curve= 0 ,0
Exp/Cntr=0.3,0.1

Type RM Length L Ch R = 1 ,222     ,0,0,0
BEGIN DESCRIPTION:
UNT 03345 IN LACR 1.0
END DESCRIPTION:
XS GIS Cut Line= 4
      3700900.11     10625511.32      3700059.33     10625258.36
      3699963.84      10625510.1      3700210.94     10626286.06
#Sta/Elev= 30
  3942.6  283.78  4089.3  278.55  4169.9  271.68  4235.5  267.96  4241.2  265.91
  4256.4  266.31  4274.2  262.87  4279.4  264.36  4298.2  261.04  4444.4  254.27
    4507  248.27    4620  247.94  4663.7  245.39  4768.1  242.89  4946.1   243.2
  5003.4  241.74  5006.2  241.24  5009.4  241.74  5031.2     243  5163.5  246.76
  5351.5  257.71  5404.8   261.8  5421.2   264.7  5426.5   263.9  5485.7  267.54
  5550.1  273.45  5562.2  276.25  5604.2  280.49  5684.2  286.05  5904.2  286.93
#Mann= 3 ,-1 , 0
  3942.6     .09       0  5003.4     .06       0  5009.4     .09       0
Bank Sta=4768.1,5031.2
XS Rating Curve= 0 ,0
Exp/Cntr=0.3,0.1

Chan Stop Cuts=-1
Use User Specified Reach Order=0
Composite Channel Slope=5