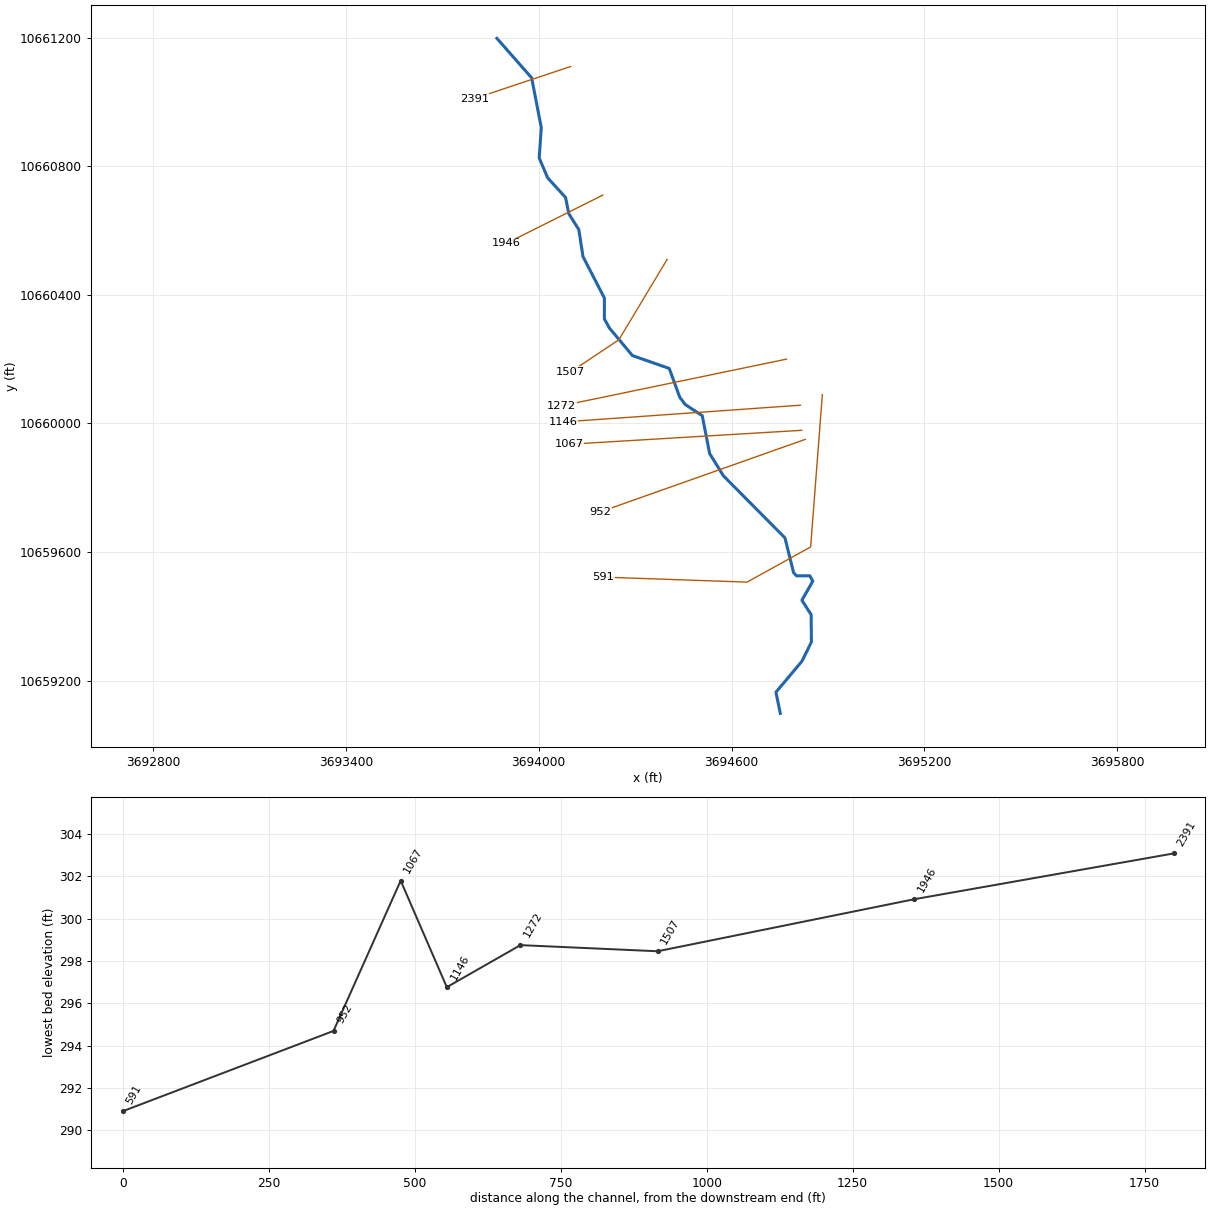
--- UNT 03367 IN LACR.prj (project) ---

Proj Title=UNT 03367 IN LACR Base Level Engineering
Current Plan=p01
Default Exp/Contr=0.3,0.1
English Units
Geom File=g01
Flow File=f01
Plan File=p01
BEGIN DESCRIPTION:
UNT 03367 IN LACR
END DESCRIPTION:

--- UNT 03367 IN LACR.p01 (plan) ---

Plan Title=Multiple Run
Short Identifier=Multiple
Geom File=g01
Flow File=f01
Subcritical Flow
K Sum by GR= 0
Std Step Tol= 0.01
Critical Tol= 0.01
Num of Std Step Trials= 20
Max Error Tol= 0.3
Flow Tol Ratio= 0.001
Split Flow NTrial= 30
Split Flow Tol= 0.02
Split Flow Ratio= 0.02
Log Output Level= 0
Friction Slope Method= 1
Unsteady Friction Slope Method= 2
Unsteady Bridges Friction Slope Method= 1
Parabolic Critical Depth
Global Vel Dist=  1 , 1 , 1
Global Log Level= 0
CheckData=True
Encroach Param= -1, 0, 0, 0
BEGIN DESCRIPTION:
Multiple Run
END DESCRIPTION:

--- UNT 03367 IN LACR.f01 (steady flow) ---

Flow Title=Multiple
Number of Profiles=7
Profile Names=10-year,25-year,50-year,1pct_min,100-year,1pct_plu,500-year
River Rch & RM= UNT 03367 IN LAC,Reach-1,2391
     394     521     623     549     742    1004    1055
Boundary for River Rch & Prof#=UNT 03367 IN LAC,Reach-1,1
Up Type=0
Dn Type=3
Dn Slope=0.005
Boundary for River Rch & Prof#=UNT 03367 IN LAC,Reach-1,2
Up Type=0
Dn Type=3
Dn Slope=0.005
Boundary for River Rch & Prof#=UNT 03367 IN LAC,Reach-1,3
Up Type=0
Dn Type=3
Dn Slope=0.005
Boundary for River Rch & Prof#=UNT 03367 IN LAC,Reach-1,4
Up Type=0
Dn Type=3
Dn Slope=0.005
Boundary for River Rch & Prof#=UNT 03367 IN LAC,Reach-1,5
Up Type=0
Dn Type=3
Dn Slope=0.005
Boundary for River Rch & Prof#=UNT 03367 IN LAC,Reach-1,6
Up Type=0
Dn Type=3
Dn Slope=0.005
Boundary for River Rch & Prof#=UNT 03367 IN LAC,Reach-1,7
Up Type=0
Dn Type=3
Dn Slope=0.005

--- UNT 03367 IN LACR.g01 (geometry) ---

Geom Title=Existing Conditions

River Reach=UNT 03367 IN LAC,Reach-1
Reach XY= 30
      3693870.16     10661197.88      3693978.25     10661075.00
      3694008.25     10660920.00      3694001.75     10660826.00
      3694028.00     10660764.00      3694083.75     10660703.00
      3694094.00     10660652.00      3694125.00     10660603.00
      3694138.00     10660519.00      3694204.50     10660390.00
      3694204.50     10660325.00      3694220.00     10660297.00
      3694291.75     10660211.00      3694406.25     10660171.00
      3694438.75     10660082.00      3694455.75     10660059.00
      3694509.00     10660024.00      3694532.00     10659906.00
      3694574.75     10659837.00      3694766.25     10659644.00
      3694793.00     10659536.00      3694802.00     10659526.00
      3694843.75     10659526.00      3694852.75     10659509.00
      3694819.00     10659450.00      3694847.75     10659405.00
      3694848.50     10659320.00      3694819.00     10659260.00
      3694738.25     10659164.00      3694751.75     10659098.00

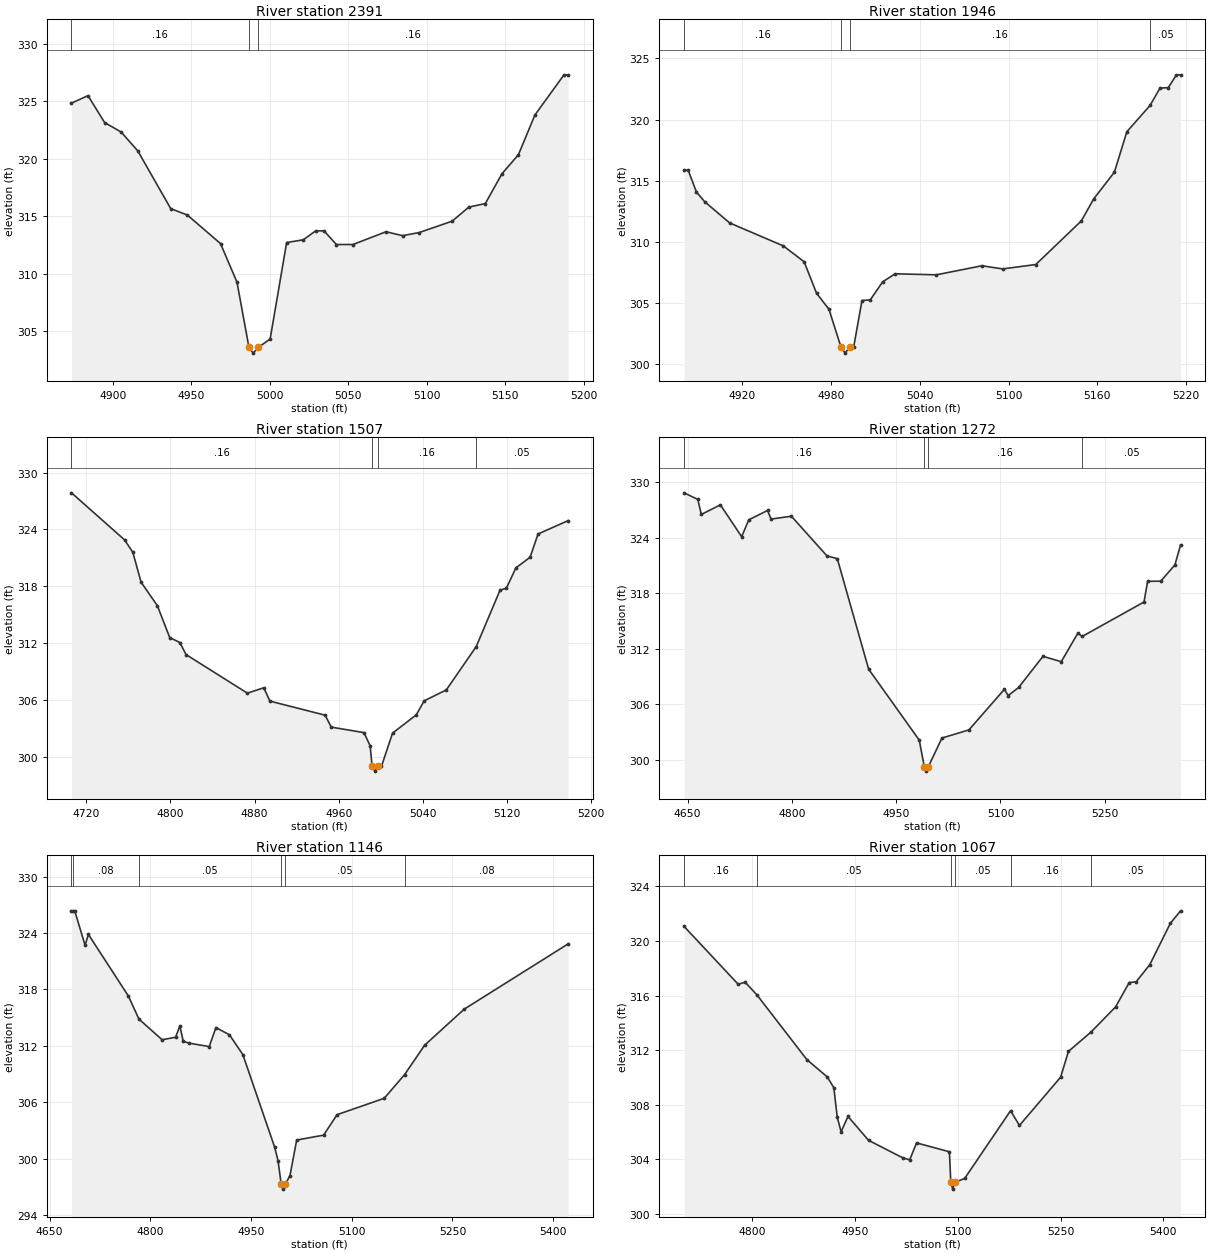
Type RM Length L Ch R = 1,2391,445,445,445
BEGIN DESCRIPTION:
UNT 03367 IN LACR 5.0
END DESCRIPTION:
XS GIS Cut Line= 3
      3694099.61     10661110.19      3693949.61     10661060.19
      3693799.64     10661010.20
#Sta/Elev= 30
  4873.7  324.82  4884.2  325.47  4894.8  323.13  4905.3  322.31  4915.9  320.67
  4936.9  315.65  4947.5  315.09  4968.6  312.61  4979.1  309.25  4986.7  303.59
  4989.4  303.09  4992.7  303.59  5000.2  304.32  5010.7  312.70  5021.3  312.94
  5029.2  313.72  5034.5  313.72  5042.4  312.53  5052.9  312.53  5074.0  313.64
  5084.5  313.30  5095.1  313.57  5116.1  314.56  5126.7  315.78  5137.2  316.09
  5147.8  318.68  5158.3  320.34  5168.8  323.79  5187.3  327.28  5189.9  327.28
#Mann=3,-1,0
  4873.7    0.16       0  4986.7    0.07       0  4992.7    0.16       0
Bank Sta=4986.7,4992.7
Exp/Cntr=0.3,0.1

Type RM Length L Ch R = 1,1946,439,439,439
BEGIN DESCRIPTION:
UNT 03367 IN LACR 4.0
END DESCRIPTION:
XS GIS Cut Line= 3
      3694199.63     10660710.20      3694099.61     10660660.19
      3693899.64     10660560.20
#Sta/Elev= 30
  4880.8  315.87  4883.6  315.87  4889.2  314.08  4894.8  313.29  4911.6  311.56
  4947.9  309.68  4961.9  308.39  4970.3  305.82  4978.7  304.50  4986.8  301.42
  4989.6  300.92  4992.8  301.42  4995.4  301.42  5001.0  305.22  5006.6  305.27
  5015.0  306.75  5023.4  307.40  5051.3  307.32  5082.1  308.06  5096.0  307.80
  5118.4  308.16  5149.2  311.73  5157.5  313.52  5171.5  315.71  5179.9  319.01
  5195.6  321.16  5202.3  322.58  5207.9  322.61  5213.4  323.66  5216.2  323.66
#Mann=4,-1,0
  4880.8    0.16       0  4986.8    0.07       0  4992.8    0.16       0
  5195.6    0.05       0
Bank Sta=4986.8,4992.8
Exp/Cntr=0.3,0.1

Type RM Length L Ch R = 1,1507,235,235,235
BEGIN DESCRIPTION:
UNT 03367 IN LACR 3.0
END DESCRIPTION:
XS GIS Cut Line= 3
      3694399.60     10660510.17      3694249.61     10660260.19
      3694099.61     10660160.19
#Sta/Elev= 30
  4706.1  327.87  4756.6  322.89  4764.4  321.58  4772.2  318.43  4787.7  315.94
  4799.4  312.58  4809.1  312.05  4814.9  310.78  4873.2  306.70  4888.8  307.27
  4894.6  305.86  4947.1  304.37  4952.9  303.11  4984.0  302.53  4989.9  301.12
  4991.7  298.96  4994.5  298.46  4997.7  298.96  5000.6  298.96  5011.1  302.47
  5033.7  304.41  5041.2  305.89  5062.2  307.04  5090.7  311.63  5113.3  317.59
  5119.3  317.79  5128.3  319.93  5141.8  321.06  5149.4  323.52  5177.9  324.93
#Mann=4,-1,0
  4706.1    0.16       0  4991.7    0.07       0  4997.7    0.16       0
  5090.7    0.05       0
Bank Sta=4991.7,4997.7
Exp/Cntr=0.3,0.1

Type RM Length L Ch R = 1,1272,126,126,126
BEGIN DESCRIPTION:
Mapping XS 419d99a3
END DESCRIPTION:
XS GIS Cut Line= 2
      3694770.81     10660199.88      3694071.60     10660054.84
#Sta/Elev= 30
  4644.9  328.86  4664.7  328.15  4669.8  326.52  4697.2  327.56  4727.8  324.11
  4738.0  325.94  4765.0  326.95  4770.1  326.02  4799.3  326.33  4850.4  322.04
  4865.3  321.74  4910.4  309.78  4983.2  302.10  4990.4  299.25  4993.1  298.75
  4996.4  299.25  5015.8  302.33  5054.6  303.21  5105.7  307.61  5111.0  306.92
  5126.1  307.80  5161.1  311.17  5187.4  310.59  5211.3  313.68  5217.5  313.32
  5306.4  317.05  5311.6  319.29  5330.4  319.30  5350.8  321.06  5359.0  323.23
#Mann=4,-1,0
  4644.9    0.16       0  4990.4    0.07       0  4996.4    0.16       0
  5217.5    0.05       0
Bank Sta=4990.4,4996.4
Exp/Cntr=0.3,0.1

Type RM Length L Ch R = 1,1146,79,79,79
BEGIN DESCRIPTION:
UNT 03367 IN LACR 2.0
END DESCRIPTION:
XS GIS Cut Line= 2
      3694814.21     10660056.65      3694076.45     10660004.57
#Sta/Elev= 30
  4682.7  326.36  4684.2  326.36  4687.5  326.36  4702.9  322.70  4707.9  323.85
  4767.5  317.29  4783.1  314.85  4817.6  312.65  4837.7  312.91  4844.1  314.12
  4849.1  312.49  4857.7  312.29  4887.8  311.92  4897.8  313.94  4917.9  313.18
  4937.9  311.07  4985.3  301.22  4990.3  299.79  4995.1  297.26  4997.8  296.76
  5001.1  297.26  5008.1  298.20  5018.1  301.98  5058.2  302.50  5078.3  304.68
  5148.5  306.42  5178.8  308.94  5208.6  312.06  5267.6  315.90  5422.3  322.84
#Mann=6,-1,0
  4682.7    0.05       0  4684.2    0.08       0  4783.1    0.05       0
  4995.1    0.04       0  5001.1    0.05       0  5178.8    0.08       0
Bank Sta=4995.1,5001.1
Exp/Cntr=0.3,0.1

Type RM Length L Ch R = 1,1067,115,115,115
BEGIN DESCRIPTION:
Mapping XS bb7bedad
END DESCRIPTION:
XS GIS Cut Line= 2
      3694818.64     10659978.53      3694094.74     10659935.18
#Sta/Elev= 30
  4700.0  321.07  4779.2  316.82  4789.2  316.98  4806.4  316.05  4879.4  311.30
  4909.4  310.02  4918.8  309.23  4923.8  307.07  4929.4  306.01  4939.5  307.13
  4969.5  305.38  5019.6  304.09  5029.6  303.95  5039.6  305.19  5087.6  304.54
  5089.6  302.30  5092.4  301.80  5095.6  302.30  5109.8  302.58  5176.9  307.55
  5189.9  306.47  5250.0  310.01  5261.4  311.90  5294.4  313.32  5330.2  315.16
  5350.2  316.95  5360.2  317.00  5380.2  318.26  5410.3  321.30  5425.2  322.21
#Mann=6,-1,0
  4700.0    0.16       0  4806.4    0.05       0  5089.6    0.04       0
  5095.6    0.05       0  5176.9    0.16       0  5294.4    0.05       0
Bank Sta=5089.6,5095.6
Exp/Cntr=0.3,0.1

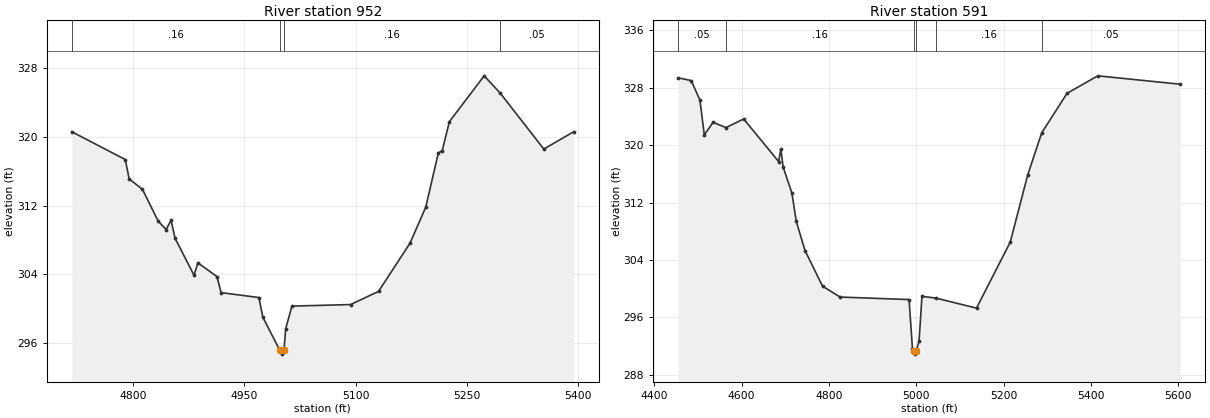
Type RM Length L Ch R = 1,952,361,361,361
BEGIN DESCRIPTION:
Mapping XS ba7f99b1
END DESCRIPTION:
XS GIS Cut Line= 2
      3694829.47     10659950.33      3694191.41     10659724.62
#Sta/Elev= 30
  4717.3  320.62  4789.4  317.38  4794.7  315.12  4812.6  313.90  4833.8  310.20
  4844.4  309.22  4851.2  310.29  4856.5  308.20  4882.1  303.89  4887.4  305.33
  4913.0  303.73  4918.7  301.86  4969.5  301.29  4974.8  299.01  4997.4  295.19
  5000.2  294.69  5003.4  295.19  5005.7  297.67  5014.1  300.29  5093.1  300.47
  5130.8  302.00  5173.3  307.63  5194.5  311.84  5211.4  318.13  5216.7  318.43
  5226.3  321.79  5273.2  327.14  5294.9  325.12  5353.6  318.60  5394.1  320.63
#Mann=4,-1,0
  4717.3    0.16       0  4997.4    0.07       0  5003.4    0.16       0
  5294.9    0.05       0
Bank Sta=4997.4,5003.4
Exp/Cntr=0.3,0.1

Type RM Length L Ch R = 1,591,0,0,0
BEGIN DESCRIPTION:
UNT 03367 IN LACR 1.0
END DESCRIPTION:
XS GIS Cut Line= 4
      3694882.61     10660089.67      3694846.15     10659615.68
      3694648.23     10659506.31      3694200.32     10659521.93
#Sta/Elev= 30
  4454.9  329.37  4484.5  328.99  4504.5  326.29  4514.6  321.43  4534.6  323.17
  4564.2  322.44  4604.8  323.64  4684.8  317.71  4689.8  319.47  4695.1  316.94
  4715.1  313.35  4725.2  309.38  4745.2  305.31  4785.3  300.36  4825.5  298.84
  4983.5  298.49  4991.2  291.67  4994.0  291.39  4996.7  290.89  5000.0  291.39
  5006.3  292.65  5013.0  298.94  5045.1  298.69  5137.9  297.30  5215.1  306.48
  5255.1  315.83  5287.2  321.71  5345.2  327.21  5415.7  329.65  5604.6  328.48
#Mann=6,-1,0
  4454.9    0.05       0  4564.2    0.16       0  4994.0    0.07       0
  5000.0    0.16       0  5045.1    0.16       0  5287.2    0.05       0
Bank Sta=4994,5000
Exp/Cntr=0.3,0.1

Chan Stop Cuts=-1