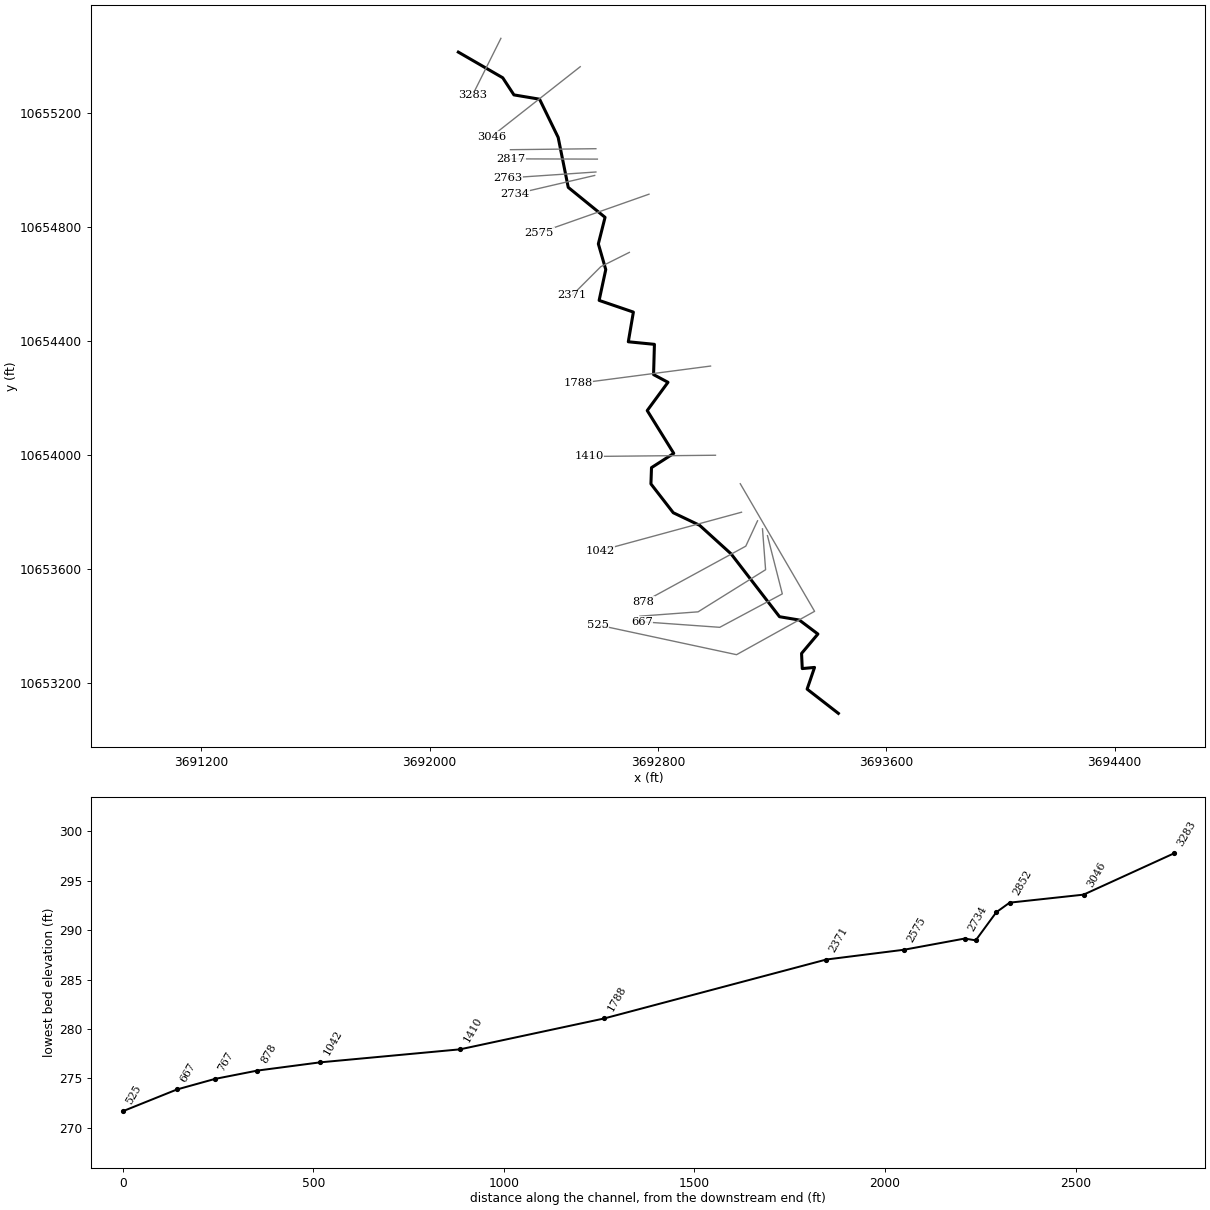
--- UNT 03372 IN LACR.prj (project) ---

Proj Title=UNT 03372 IN LACR Base Level Engineering
Current Plan=p01
Default Exp/Contr=0.3,0.1
English Units
Geom File=g01
Flow File=f01
Plan File=p01
Y Axis Title=Elevation
X Axis Title(PF)=Main Channel Distance
X Axis Title(XS)=Station
BEGIN DESCRIPTION:
UNT 03372 IN LACR
END DESCRIPTION:
DSS Export Rating Curves= 0
DSS Export Rating Curve Sorted= 0
DSS Export Volume Flow Curves= 0
DXF OffsetX= 0
DXF OffsetY= 0
DXF ScaleX= 1
DXF ScaleY= 10

--- UNT 03372 IN LACR.p01 (plan) ---

Plan Title=Multiple Run
Short Identifier=Multiple
Geom File=g01
Flow File=f01
Subcritical Flow
K Sum by GR= 0
Std Step Tol= 0.01
Critical Tol= 0.01
Num of Std Step Trials= 20
Max Error Tol= 0.3
Flow Tol Ratio= 0.001
Split Flow NTrial= 30
Split Flow Tol= 0.02
Split Flow Ratio= 0.02
Log Output Level= 0
Friction Slope Method= 1
Unsteady Friction Slope Method= 2
Unsteady Bridges Friction Slope Method= 1
Parabolic Critical Depth
Global Vel Dist=  1 , 1 , 1
Global Log Level= 0
CheckData=True
Encroach Param= -1, 0, 0, 0
BEGIN DESCRIPTION:
Multiple Run
END DESCRIPTION:

--- UNT 03372 IN LACR.f01 (steady flow) ---

Flow Title=Multiple
Program Version=4.10
Number of Profiles= 7
Profile Names=10-year,25-year,50-year,1pct_min,100-year,1pct_plu,500-year
River Rch & RM=UNT 03372 IN LAC,Reach-1         ,3283
     237     304     357     309     418     566     574
Boundary for River Rch & Prof#=UNT 03372 IN LAC,Reach-1         , 1
Up Type= 0
Dn Type= 3
Dn Slope=0.016
Boundary for River Rch & Prof#=UNT 03372 IN LAC,Reach-1         , 2
Up Type= 0
Dn Type= 3
Dn Slope=0.016
Boundary for River Rch & Prof#=UNT 03372 IN LAC,Reach-1         , 3
Up Type= 0
Dn Type= 3
Dn Slope=0.016
Boundary for River Rch & Prof#=UNT 03372 IN LAC,Reach-1         , 4
Up Type= 0
Dn Type= 3
Dn Slope=0.016
Boundary for River Rch & Prof#=UNT 03372 IN LAC,Reach-1         , 5
Up Type= 0
Dn Type= 3
Dn Slope=0.016
Boundary for River Rch & Prof#=UNT 03372 IN LAC,Reach-1         , 6
Up Type= 0
Dn Type= 3
Dn Slope=0.016
Boundary for River Rch & Prof#=UNT 03372 IN LAC,Reach-1         , 7
Up Type= 0
Dn Type= 3
Dn Slope=0.016
DSS Import GetInterval= 0
DSS Import GetPeak= 0
DSS Import FillOption= 0

--- UNT 03372 IN LACR.g01 (geometry) ---

Geom Title=Existing Conditions
Program Version=4.10

River Reach=UNT 03372 IN LAC,Reach-1
Reach XY= 30
      3692100.44     10655411.91        3692256.       10655322.
      3692295.25       10655262.        3692385.       10655247.
      3692450.25       10655113.       3692485.5       10654938.
       3692614.5       10654833.        3692591.       10654740.
        3692617.       10654650.      3692593.75       10654542.
      3692713.75       10654501.        3692696.       10654397.
       3692787.5       10654388.       3692784.5       10654282.
        3692835.       10654255.      3692762.25       10654156.
      3692855.25       10654006.      3692777.25       10653956.
      3692775.25       10653899.       3692853.5       10653798.
      3692945.75       10653754.        3693056.       10653654.
      3693225.72      10653433.7      3693295.25       10653422.
      3693360.25       10653373.        3693303.       10653305.
       3693305.5       10653252.       3693348.5       10653256.
       3693322.5       10653180.        3693432.       10653095.

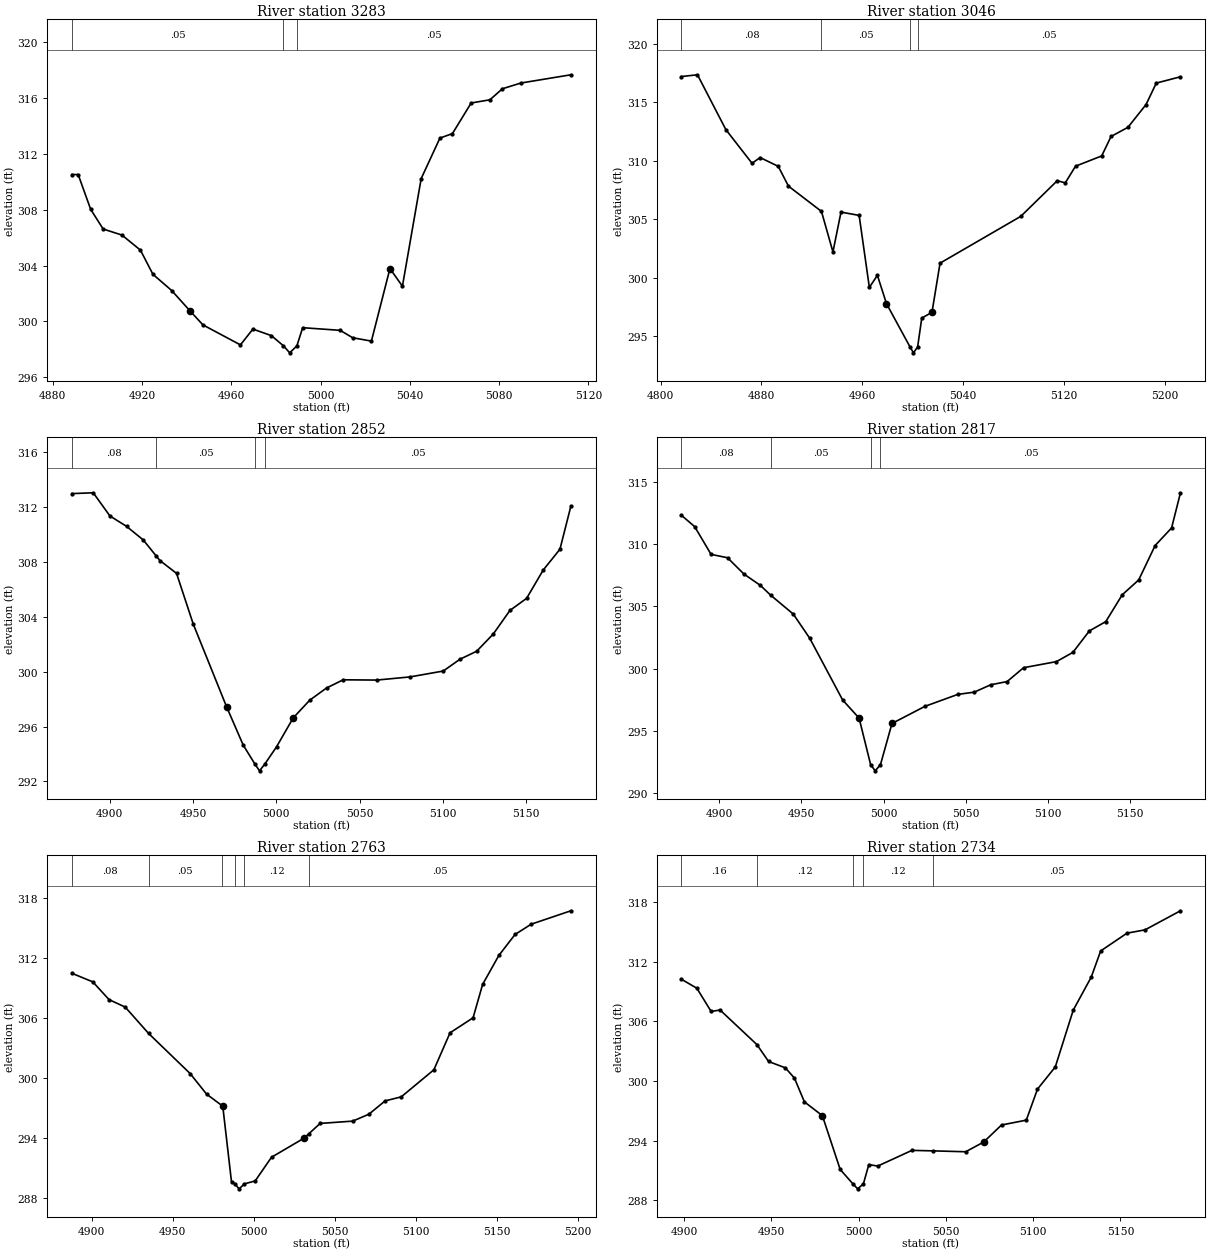
Type RM Length L Ch R = 1 ,3283    ,237,237,237
BEGIN DESCRIPTION:
UNT 03372 IN LACR 6.0
END DESCRIPTION:
XS GIS Cut Line= 3
      3692249.61     10655460.18      3692199.61     10655360.19
      3692149.61     10655260.19
#Sta/Elev= 30
  4888.6  310.51  4891.4  310.51    4897  308.02  4902.6  306.61    4911  306.18
  4919.3   305.1  4924.9  303.37  4933.3  302.21  4941.7  300.72  4947.3  299.75
  4964.1  298.32  4969.7  299.45    4978  298.98  4983.4  298.25  4986.2  297.75
  4989.4  298.25    4992  299.55  5008.8  299.36  5014.4  298.83  5022.8  298.59
  5031.1  303.78  5036.7  302.52  5045.1  310.22  5053.5  313.12  5059.1  313.44
  5067.5  315.63  5075.9  315.86  5081.5  316.65  5089.8  317.06  5112.2  317.65
#Mann= 3 ,-1 , 0
  4888.6     .05       0  4983.4     .03       0  4989.4     .05       0
Bank Sta=4941.7,5031.1
XS Rating Curve= 0 ,0
Exp/Cntr=0.3,0.1

Type RM Length L Ch R = 1 ,3046    ,194,194,194
BEGIN DESCRIPTION:
Mapping XS 52705c54
END DESCRIPTION:
XS GIS Cut Line= 2
      3692527.52     10655360.73      3692216.27      10655115.9
#Sta/Elev= 30
  4816.6  317.18  4829.3  317.33  4851.8  312.65  4872.6  309.77    4879  310.26
  4893.4  309.51  4901.5  307.82  4927.7  305.66  4936.8   302.2  4943.2   305.6
  4957.6  305.32  4965.7  299.17  4972.1   300.2  4979.3  297.78    4998  294.08
  5000.7  293.58    5004  294.08  5007.3  296.55  5015.4  297.04  5021.8  301.24
  5085.9  305.24  5114.8  308.28  5121.2   308.1  5129.3  309.52  5150.1   310.4
  5157.5  312.06  5170.9  312.84  5185.3  314.79  5193.4  316.62  5212.6  317.16
#Mann= 4 ,-1 , 0
  4816.6     .08       0  4927.7     .05       0    4998     .03       0
    5004     .05       0
Bank Sta=4979.3,5015.4
XS Rating Curve= 0 ,0
Exp/Cntr=0.3,0.1

Type RM Length L Ch R = 1 ,2852    ,35,35,35
BEGIN DESCRIPTION:
Mapping XS a52754aa
END DESCRIPTION:
XS GIS Cut Line= 2
      3692582.45     10655073.47      3692282.97     10655070.02
#Sta/Elev= 30
  4877.3  312.99  4890.1  313.05  4900.1  311.36  4910.1   310.6  4920.1  309.61
  4927.7  308.47  4930.1  308.11  4940.1  307.17  4950.1  303.48  4970.1  297.45
  4980.1  294.65  4987.1  293.27  4989.9  292.77  4993.1  293.27  5000.1  294.52
  5010.1  296.63  5020.1  297.93  5030.1  298.81  5040.1  299.41  5060.2  299.39
  5080.2  299.62  5100.2  300.05  5110.2  300.91  5120.2  301.49  5130.2  302.75
  5140.2  304.47  5150.2  305.35  5160.2  307.42  5170.2  308.93  5176.8  312.09
#Mann= 4 ,-1 , 0
  4877.3     .08       0  4927.7     .05       0  4987.1     .04       0
  4993.1     .05       0
Bank Sta=4970.1,5010.1
XS Rating Curve= 0 ,0
Exp/Cntr=0.3,0.1

Type RM Length L Ch R = 1 ,2817    ,54,54,54
BEGIN DESCRIPTION:
UNT 03372 IN LACR 5.0
END DESCRIPTION:
XS GIS Cut Line= 2
      3692587.64     10655037.01      3692284.24     10655037.88
#Sta/Elev= 30
  4877.1  312.29  4885.1  311.39  4895.1  309.16  4905.1  308.89  4915.1  307.58
  4925.1  306.67  4931.3  305.89  4945.1  304.37  4955.1  302.43  4975.1  297.48
  4985.1  296.03  4992.1   292.3  4994.9   291.8  4998.1   292.3  5005.1   295.6
  5025.1  296.97  5045.1  297.93  5055.1  298.11  5065.1   298.7  5075.1  298.96
  5085.1  300.07  5105.1  300.56  5115.1   301.3  5125.1  303.02  5135.1  303.77
  5145.1  305.92  5155.1  307.11  5165.1  309.87  5175.1  311.28  5180.5   314.1
#Mann= 4 ,-1 , 0
  4877.1     .08       0  4931.3     .05       0  4992.1     .04       0
  4998.1     .05       0
Bank Sta=4985.1,5005.1
XS Rating Curve= 0 ,0
Exp/Cntr=0.3,0.1

Type RM Length L Ch R = 1 ,2763    ,29,29,29
BEGIN DESCRIPTION:
Mapping XS 06b936d0
END DESCRIPTION:
XS GIS Cut Line= 2
      3692582.48     10654991.87      3692275.19     10654971.04
#Sta/Elev= 30
  4887.7  310.51  4900.6  309.65  4910.6  307.88  4920.6  307.13    4935   304.5
  4960.7  300.48  4970.8  298.43  4980.1  297.31  4980.8  297.23  4986.2  289.65
  4988.2  289.46  4990.9  288.96  4994.2  289.46  5000.8  289.75  5010.9  292.12
  5030.9  294.02  5033.9  294.46  5040.9   295.5    5061  295.73    5071  296.42
    5081  297.75    5091  298.16  5111.1  300.86  5121.1  304.56  5135.3  306.06
  5141.2   309.4  5151.2  312.29  5161.2  314.39  5171.2  315.42  5195.7  316.76
#Mann= 6 ,-1 , 0
  4887.7     .08       0    4935     .05       0  4980.1     .12       0
  4988.2     .07       0  4994.2     .12       0  5033.9     .05       0
Bank Sta=4980.8,5030.9
XS Rating Curve= 0 ,0
Exp/Cntr=0.3,0.1

Type RM Length L Ch R = 1 ,2734    ,159,159,159
BEGIN DESCRIPTION:
Mapping XS f581d366
END DESCRIPTION:
XS GIS Cut Line= 2
      3692578.16     10654979.73      3692299.81      10654914.9
#Sta/Elev= 30
  4898.6  310.22  4907.4  309.32  4915.6  306.98  4920.7  307.13  4941.8  303.65
  4948.5  301.95  4958.1  301.31  4963.3  300.28    4969  297.89  4979.3   296.5
  4989.5  291.09  4996.8  289.64  4999.5  289.14  5002.8  289.64  5005.9  291.58
    5011  291.43  5030.6  293.01  5042.5  292.96  5061.4  292.87  5071.7  293.85
  5081.9  295.56  5096.1  296.05  5102.5  299.17  5112.7   301.4    5123  307.12
  5133.3  310.44  5138.7  313.07  5153.8  314.86  5164.1  315.19  5184.4  317.11
#Mann= 5 ,-1 , 0
  4898.6     .16       0  4941.8     .12       0  4996.8     .07       0
  5002.8     .12       0  5042.5     .05       0
Bank Sta=4979.3,5071.7
XS Rating Curve= 0 ,0
Exp/Cntr=0.3,0.1

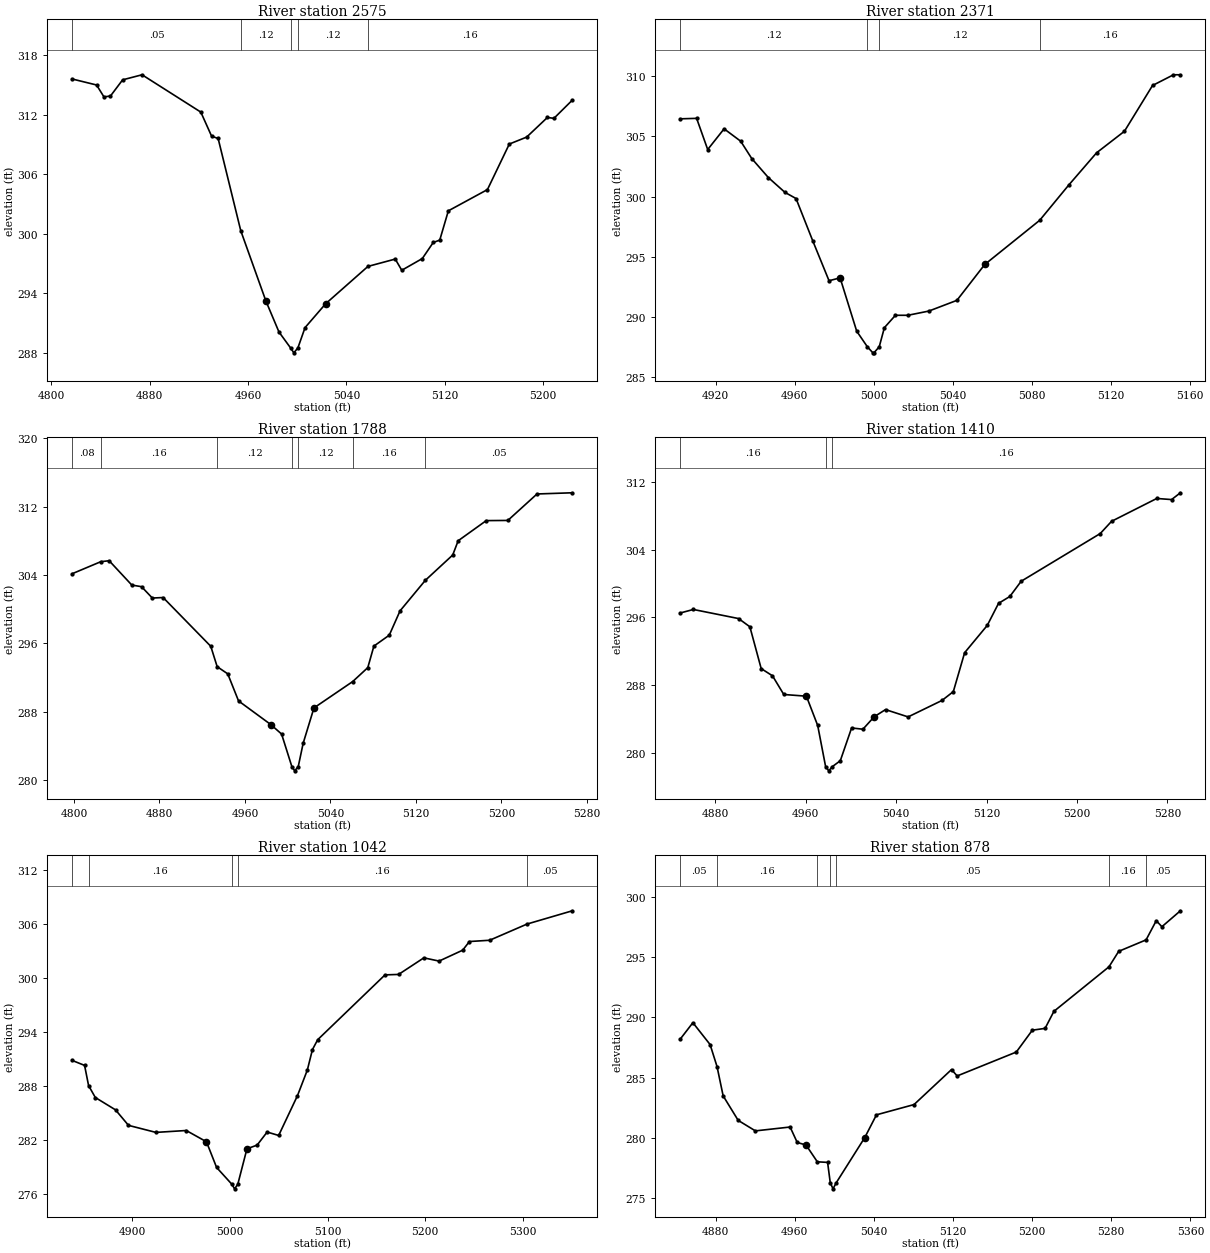
Type RM Length L Ch R = 1 ,2575    ,204,204,204
BEGIN DESCRIPTION:
Mapping XS 70e1b0fe
END DESCRIPTION:
XS GIS Cut Line= 2
      3692768.42     10654914.11      3692384.48     10654778.76
#Sta/Elev= 30
  4816.8  315.61  4836.8     315  4842.8   313.8  4848.1  313.89    4858  315.52
  4873.8  316.03  4921.6  312.27  4930.4  309.84  4935.7  309.61  4954.1  300.32
  4974.6  293.22  4985.2  290.11  4994.6  288.51  4997.3  288.01  5000.6  288.51
  5006.4  290.55  5023.2  292.96  5057.6  296.72  5079.8  297.46  5085.1  296.33
  5101.8  297.51  5110.7  299.13    5116  299.37    5123  302.32  5154.8  304.46
  5172.6  309.05  5186.7  309.75  5203.6  311.73  5208.9  311.64  5223.9  313.48
#Mann= 5 ,-1 , 0
  4816.8     .05       0  4954.1     .12       0  4994.6     .07       0
  5000.6     .12       0  5057.6     .16       0
Bank Sta=4974.6,5023.2
XS Rating Curve= 0 ,0
Exp/Cntr=0.3,0.1

Type RM Length L Ch R = 1 ,2371    ,583,583,583
BEGIN DESCRIPTION:
UNT 03372 IN LACR 4.0
END DESCRIPTION:
XS GIS Cut Line= 3
      3692699.59     10654710.18      3692599.61     10654660.19
      3692499.61     10654560.19
#Sta/Elev= 30
  4901.9  306.46  4910.3   306.5  4915.9  303.91  4924.2  305.63  4932.6   304.6
  4938.2  303.16  4946.6  301.58    4955  300.35  4960.6  299.84    4969  296.35
  4977.3  293.01  4982.9  293.25  4991.3  288.82  4996.7  287.52  4999.5  287.02
    5000  287.02  5002.7  287.52  5005.3  289.11  5010.9  290.14  5017.2  290.14
  5027.8  290.49    5042  291.38  5056.1  294.36  5083.9  298.03  5098.5  300.94
  5112.7  303.64  5126.8  305.43    5141  309.23  5151.6  310.12  5155.1  310.12
#Mann= 4 ,-1 , 0
  4901.9     .12       0  4996.7     .07       0  5002.7     .12       0
  5083.9     .16       0
Bank Sta=4982.9,5056.1
XS Rating Curve= 0 ,0
Exp/Cntr=0.3,0.1

Type RM Length L Ch R = 1 ,1788    ,378,378,378
BEGIN DESCRIPTION:
UNT 03372 IN LACR 3.0
END DESCRIPTION:
XS GIS Cut Line= 2
      3692984.15     10654311.94      3692519.71     10654251.17
#Sta/Elev= 30
  4798.1  304.14  4825.1  305.56  4832.9  305.67  4854.1  302.82  4863.2  302.63
  4873.3   301.3  4883.4  301.36    4928  295.65    4934  293.26  4943.9  292.42
    4954  289.25  4984.2  286.48  4994.3  285.37  5003.9  281.56  5006.6  281.06
  5009.9  281.56  5014.5  284.29  5024.6  288.43  5060.9  291.52    5075  293.15
  5080.7  295.67  5095.1  296.95  5105.2   299.8  5128.9  303.38  5154.5  306.34
  5159.6  308.01  5185.9  310.37  5206.1  310.39  5233.4  313.49  5266.5  313.63
#Mann= 7 ,-1 , 0
  4798.1     .08       0  4825.1     .16       0    4934     .12       0
  5003.9     .07       0  5009.9     .12       0  5060.9     .16       0
  5128.9     .05       0
Bank Sta=4984.2,5024.6
XS Rating Curve= 0 ,0
Exp/Cntr=0.3,0.1

Type RM Length L Ch R = 1 ,1410    ,368,368,368
BEGIN DESCRIPTION:
UNT 03372 IN LACR 2.0
END DESCRIPTION:
XS GIS Cut Line= 2
      3693001.41     10653999.43      3692558.73     10653995.09
#Sta/Elev= 30
  4848.8  296.52  4860.6  296.94  4900.6  295.87  4910.6   294.9  4920.6  289.98
  4930.6  289.13  4940.6  286.93  4960.6  286.73  4970.6  283.28  4977.6  278.44
  4980.4  277.94  4983.6  278.44  4990.6  279.13  5000.6  282.99  5010.6  282.84
  5020.6  284.31  5030.6  285.15  5050.6  284.29  5080.6  286.23  5090.6  287.27
  5100.6  291.85  5120.6  295.06  5130.6  297.66  5140.6  298.47  5150.6  300.26
  5220.6  305.88  5230.6  307.32  5270.6  310.01  5283.7  309.88  5291.5  310.68
#Mann= 3 ,-1 , 0
  4848.8     .16       0  4977.6     .07       0  4983.6     .16       0
Bank Sta=4960.6,5020.6
XS Rating Curve= 0 ,0
Exp/Cntr=0.3,0.1

Type RM Length L Ch R = 1 ,1042    ,164,164,164
BEGIN DESCRIPTION:
Mapping XS 78ee211b
END DESCRIPTION:
XS GIS Cut Line= 2
      3693092.63     10653799.79       3692597.8     10653665.23
#Sta/Elev= 30
    4838  290.87  4850.9  290.31    4855  288.07  4861.9  286.75  4882.6  285.38
  4895.9  283.66    4924  282.88  4955.1  283.09  4975.8  281.84  4986.2  278.99
  5001.9  277.12  5004.6  276.62  5007.9  277.12  5017.3  281.06  5027.7  281.47
    5038  282.92  5049.8  282.54  5069.1  286.96  5079.2   289.8  5084.4  292.06
  5089.8  293.16  5158.8  300.35  5172.7   300.4  5198.6  302.24  5214.2  301.88
  5238.4  303.09  5245.3  304.05    5266  304.19  5304.4  305.99  5350.8  307.46
#Mann= 5 ,-1 , 0
    4838     .05       0    4855     .16       0  5001.9     .07       0
  5007.9     .16       0  5304.4     .05       0
Bank Sta=4975.8,5017.3
XS Rating Curve= 0 ,0
Exp/Cntr=0.3,0.1

Type RM Length L Ch R = 1 ,878     ,111,111,111
BEGIN DESCRIPTION:
Mapping XS bede57f3
END DESCRIPTION:
XS GIS Cut Line= 3
      3693148.78     10653769.75      3693107.56     10653680.82
      3692749.49     10653485.51
#Sta/Elev= 30
    4844  288.17    4857  289.55  4874.4  287.74  4881.4  285.92  4887.6  283.49
  4902.8  281.46  4920.2  280.59  4955.3  280.91  4962.5  279.63  4971.4  279.42
  4982.8  278.03  4993.2  277.98  4995.9  276.29  4998.7  275.79  5001.9  276.29
  5030.8  280.04  5042.6  281.92  5080.6  282.77  5118.5  285.67  5124.2  285.14
    5184  287.12  5200.2  288.93  5213.1  289.08    5222  290.49  5277.7  294.18
  5287.5  295.46  5315.2  296.41  5325.5     298  5331.2   297.5  5349.9  298.82
#Mann= 7 ,-1 , 0
    4844     .05       0  4881.4     .16       0  4982.8     .05       0
  4995.9     .03       0  5001.9     .05       0  5277.7     .16       0
  5315.2     .05       0
Bank Sta=4971.4,5030.8
XS Rating Curve= 0 ,0
Exp/Cntr=0.3,0.1

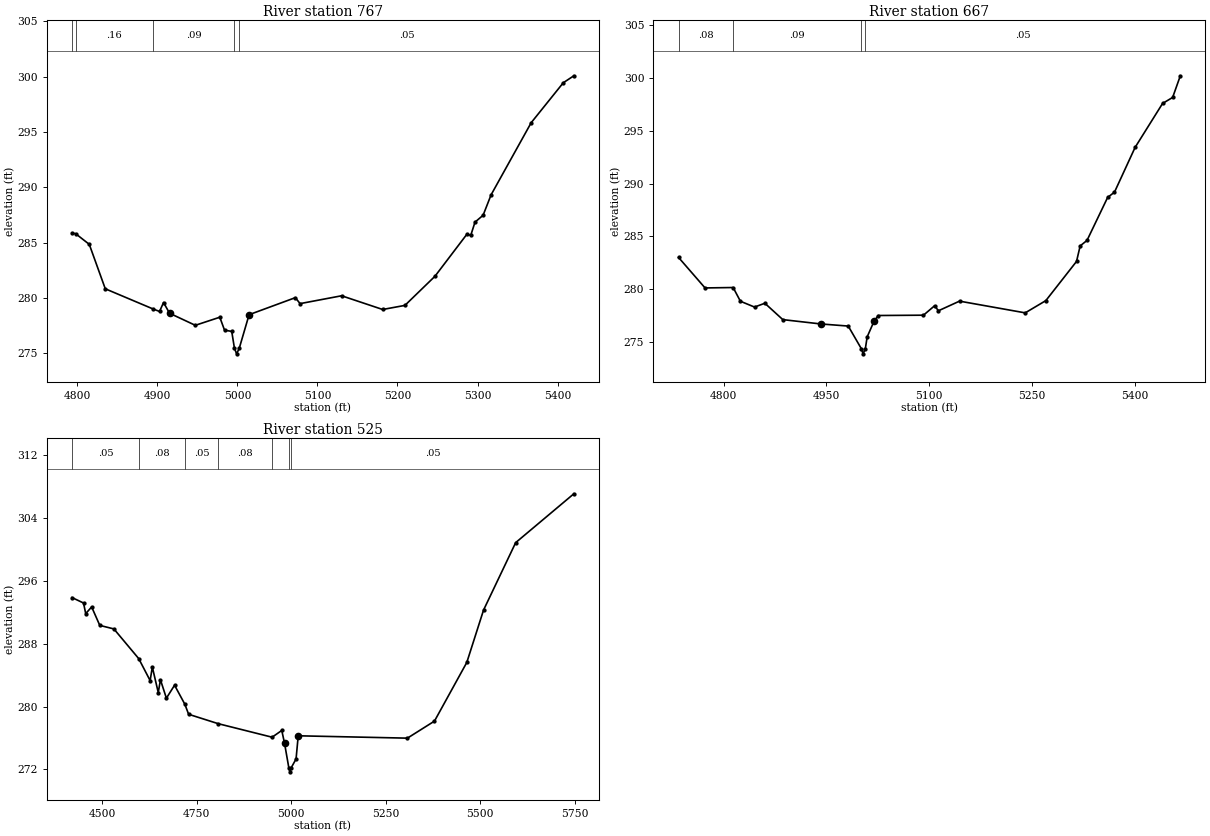
Type RM Length L Ch R = 1 ,767     ,100,100,100
BEGIN DESCRIPTION:
Mapping XS 622c7344
END DESCRIPTION:
XS GIS Cut Line= 4
      3693166.15      10653741.6      3693177.01     10653598.35
      3692940.46     10653450.78      3692736.49      10653435.6
#Sta/Elev= 30
  4793.4  285.87  4797.9  285.81  4814.9  284.85  4834.9  280.83  4894.2  279.02
  4902.7  278.78  4907.7  279.59  4915.2  278.62  4947.4  277.53    4978  278.26
  4983.9  277.09  4992.9  276.98  4996.3  275.45    4999  274.95  5002.3  275.45
  5014.6  278.49  5072.4  280.03  5078.3  279.49  5130.2   280.2  5181.5  278.96
  5209.3  279.33  5246.8  281.96  5286.6  285.75  5291.6  285.67  5296.9  286.86
    5307  287.48    5317  289.33  5367.1  295.85  5407.2  299.46  5420.4  300.09
#Mann= 5 ,-1 , 0
  4793.4     .05       0  4797.9     .16       0  4894.2     .09       0
  4996.3     .03       0  5002.3     .05       0
Bank Sta=4915.2,5014.6
XS Rating Curve= 0 ,0
Exp/Cntr=0.3,0.1

Type RM Length L Ch R = 1 ,667     ,142,142,142
BEGIN DESCRIPTION:
Mapping XS 5c570ef8
END DESCRIPTION:
XS GIS Cut Line= 4
      3693183.52     10653717.68       3693235.6     10653513.72
      3693016.42     10653396.53      3692743.76     10653416.01
#Sta/Elev= 30
  4734.1  283.01  4772.8  280.12  4813.8  280.16  4824.4  278.86    4845  278.31
  4860.1  278.67  4886.3  277.12  4941.8  276.71  4981.8  276.51  5000.8  274.38
  5003.5  273.88  5006.8  274.38  5009.4  275.48  5019.4  276.96  5025.7  277.51
  5091.6  277.54  5107.8  278.43  5113.5  277.96  5144.2  278.87  5240.1  277.76
  5270.2  278.92    5315  282.63  5320.3   284.1  5330.3  284.62  5360.4  288.69
  5370.4  289.19  5400.5  293.43  5440.6  297.59  5455.3  298.16  5466.5  300.21
#Mann= 4 ,-1 , 0
  4734.1     .08       0  4813.8     .09       0  5000.8     .03       0
  5006.8     .05       0
Bank Sta=4941.8,5019.4
XS Rating Curve= 0 ,0
Exp/Cntr=0.3,0.1

Type RM Length L Ch R = 1 ,525     ,0,0,0
BEGIN DESCRIPTION:
UNT 03372 IN LACR 1.0
END DESCRIPTION:
XS GIS Cut Line= 4
      3693088.28     10653899.58      3693348.68     10653452.56
      3693075.25     10653300.65      3692589.12     10653404.82
#Sta/Elev= 30
  4420.3  293.87  4450.6  293.18  4456.4  291.83  4472.1  292.68  4493.6  290.33
  4530.9  289.88  4596.6   286.1  4626.8   283.3  4632.6  285.02  4648.3  281.78
  4654.1   283.4  4669.8  281.06  4691.4  282.71  4718.6  280.29  4728.6  279.01
  4807.1  277.81  4949.4  276.09    4975  276.95  4982.3  275.32  4993.7  272.18
  4996.5  271.68  4999.7  272.18  5012.8  273.32  5018.5  276.27  5307.3  275.97
  5378.9  278.14  5464.4  285.61  5508.7  292.28  5593.7  300.87  5747.6  307.09
#Mann= 7 ,-1 , 0
  4420.3     .05       0  4596.6     .08       0  4718.6     .05       0
  4807.1     .08       0  4949.4     .05       0  4993.7     .03       0
  4999.7     .05       0
Bank Sta=4982.3,5018.5
XS Rating Curve= 0 ,0
Exp/Cntr=0.3,0.1

Chan Stop Cuts=-1
Use User Specified Reach Order=0
Composite Channel Slope=5