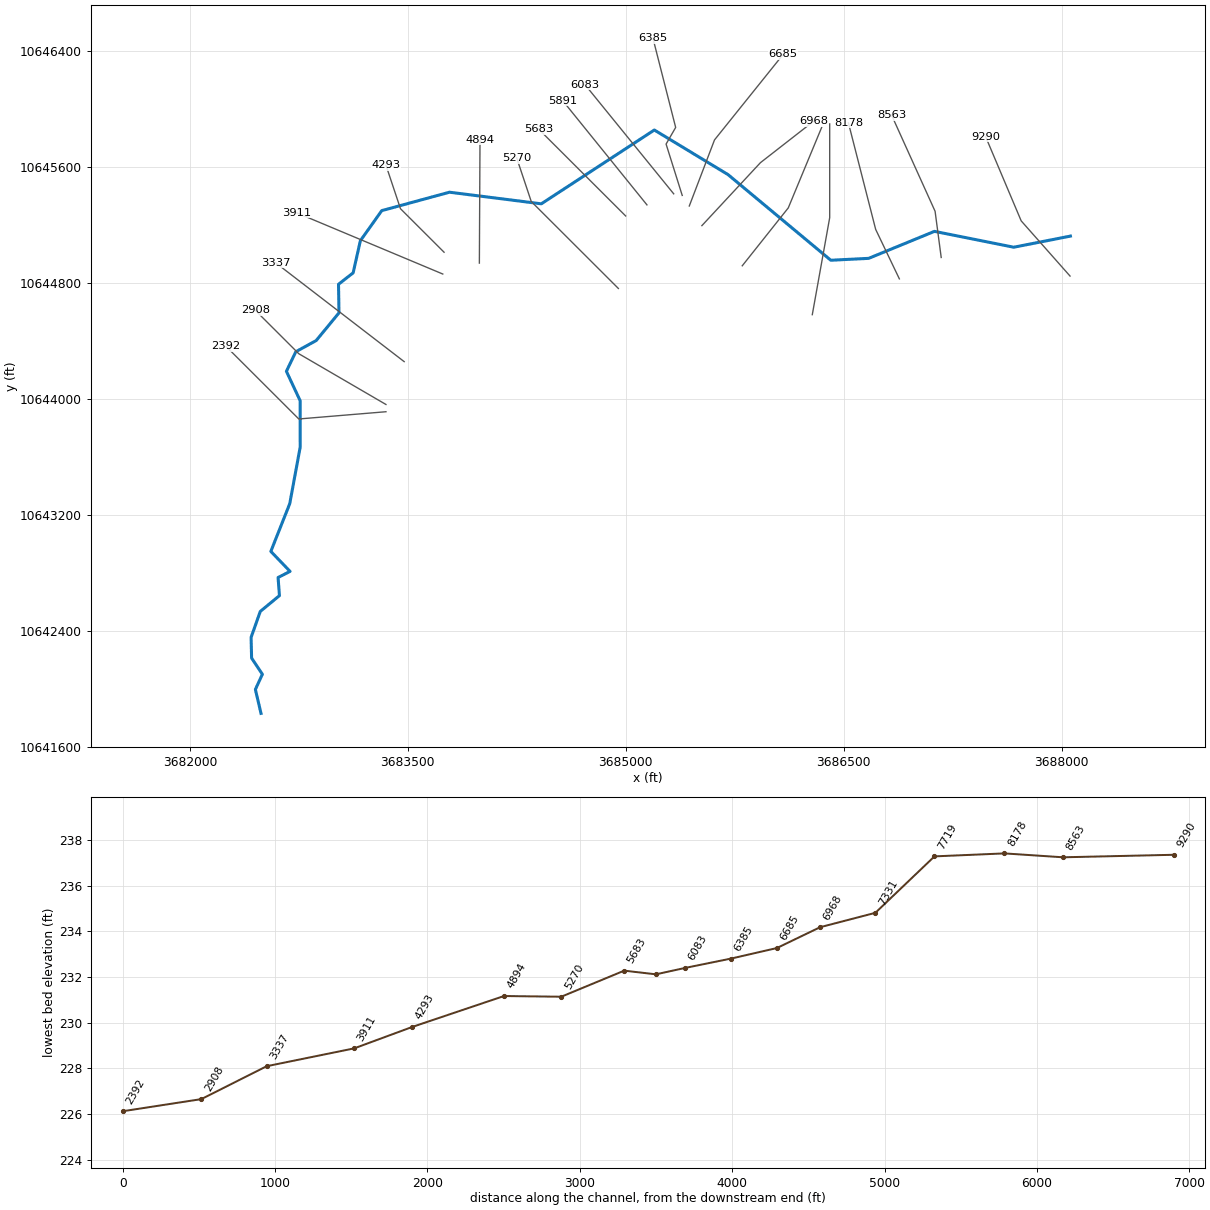
--- UNT 03388 IN LACR.prj (project) ---

Proj Title=UNT 03388 IN LACR Base Level Engineering
Current Plan=p01
Default Exp/Contr=0.3,0.1
English Units
Geom File=g01
Flow File=f01
Plan File=p01
Y Axis Title=Elevation
X Axis Title(PF)=Main Channel Distance
X Axis Title(XS)=Station
BEGIN DESCRIPTION:
UNT 03388 IN LACR
END DESCRIPTION:
DSS Export Rating Curves= 0
DSS Export Rating Curve Sorted= 0
DSS Export Volume Flow Curves= 0
DXF OffsetX= 0
DXF OffsetY= 0
DXF ScaleX= 1
DXF ScaleY= 10

--- UNT 03388 IN LACR.p01 (plan) ---

Plan Title=Multiple Run
Short Identifier=Multiple
Geom File=g01
Flow File=f01
Subcritical Flow
K Sum by GR= 0
Std Step Tol= 0.01
Critical Tol= 0.01
Num of Std Step Trials= 20
Max Error Tol= 0.3
Flow Tol Ratio= 0.001
Split Flow NTrial= 30
Split Flow Tol= 0.02
Split Flow Ratio= 0.02
Log Output Level= 0
Friction Slope Method= 1
Unsteady Friction Slope Method= 2
Unsteady Bridges Friction Slope Method= 1
Parabolic Critical Depth
Global Vel Dist=  1 , 1 , 1
Global Log Level= 0
CheckData=True
Encroach Param= -1, 0, 0, 0
BEGIN DESCRIPTION:
Multiple Run
END DESCRIPTION:

--- UNT 03388 IN LACR.f01 (steady flow) ---

Flow Title=Multiple
Program Version=4.10
Number of Profiles= 7
Profile Names=10-year,25-year,50-year,1pct_min,100-year,1pct_plu,500-year
River Rch & RM=UNT 03388 IN LAC,Reach-1         ,9290
     242     309     361     311     421     569     571
Boundary for River Rch & Prof#=UNT 03388 IN LAC,Reach-1         , 1
Up Type= 0
Dn Type= 3
Dn Slope=0.005
Boundary for River Rch & Prof#=UNT 03388 IN LAC,Reach-1         , 2
Up Type= 0
Dn Type= 3
Dn Slope=0.005
Boundary for River Rch & Prof#=UNT 03388 IN LAC,Reach-1         , 3
Up Type= 0
Dn Type= 3
Dn Slope=0.005
Boundary for River Rch & Prof#=UNT 03388 IN LAC,Reach-1         , 4
Up Type= 0
Dn Type= 3
Dn Slope=0.005
Boundary for River Rch & Prof#=UNT 03388 IN LAC,Reach-1         , 5
Up Type= 0
Dn Type= 3
Dn Slope=0.005
Boundary for River Rch & Prof#=UNT 03388 IN LAC,Reach-1         , 6
Up Type= 0
Dn Type= 3
Dn Slope=0.005
Boundary for River Rch & Prof#=UNT 03388 IN LAC,Reach-1         , 7
Up Type= 0
Dn Type= 3
Dn Slope=0.005
DSS Import GetInterval= 0
DSS Import GetPeak= 0
DSS Import FillOption= 0

--- UNT 03388 IN LACR.g01 (geometry) ---

Geom Title=Existing Conditions
Program Version=4.10

River Reach=UNT 03388 IN LAC,Reach-1
Reach XY= 30
      3688061.15     10645121.37      3687670.88     10645044.64
      3687125.31     10645154.02      3686672.18     10644967.82
      3686411.77      10644954.8      3685704.24     10645545.41
        3685197.       10645853.        3684419.       10645344.
        3683787.       10645424.      3683320.75       10645297.
      3683173.25       10645089.      3683123.75       10644868.
        3683023.       10644789.      3683026.25       10644592.
      3682869.25       10644401.      3682729.25       10644324.
      3682664.25       10644189.        3682759.       10643986.
      3682759.25       10643666.      3682687.25       10643276.
      3682557.25       10642947.       3682689.5       10642809.
        3682607.       10642767.       3682616.5       10642642.
       3682484.5       10642533.      3682421.25       10642354.
      3682424.75       10642211.        3682499.       10642100.
      3682450.75       10641995.       3682489.5       10641830.

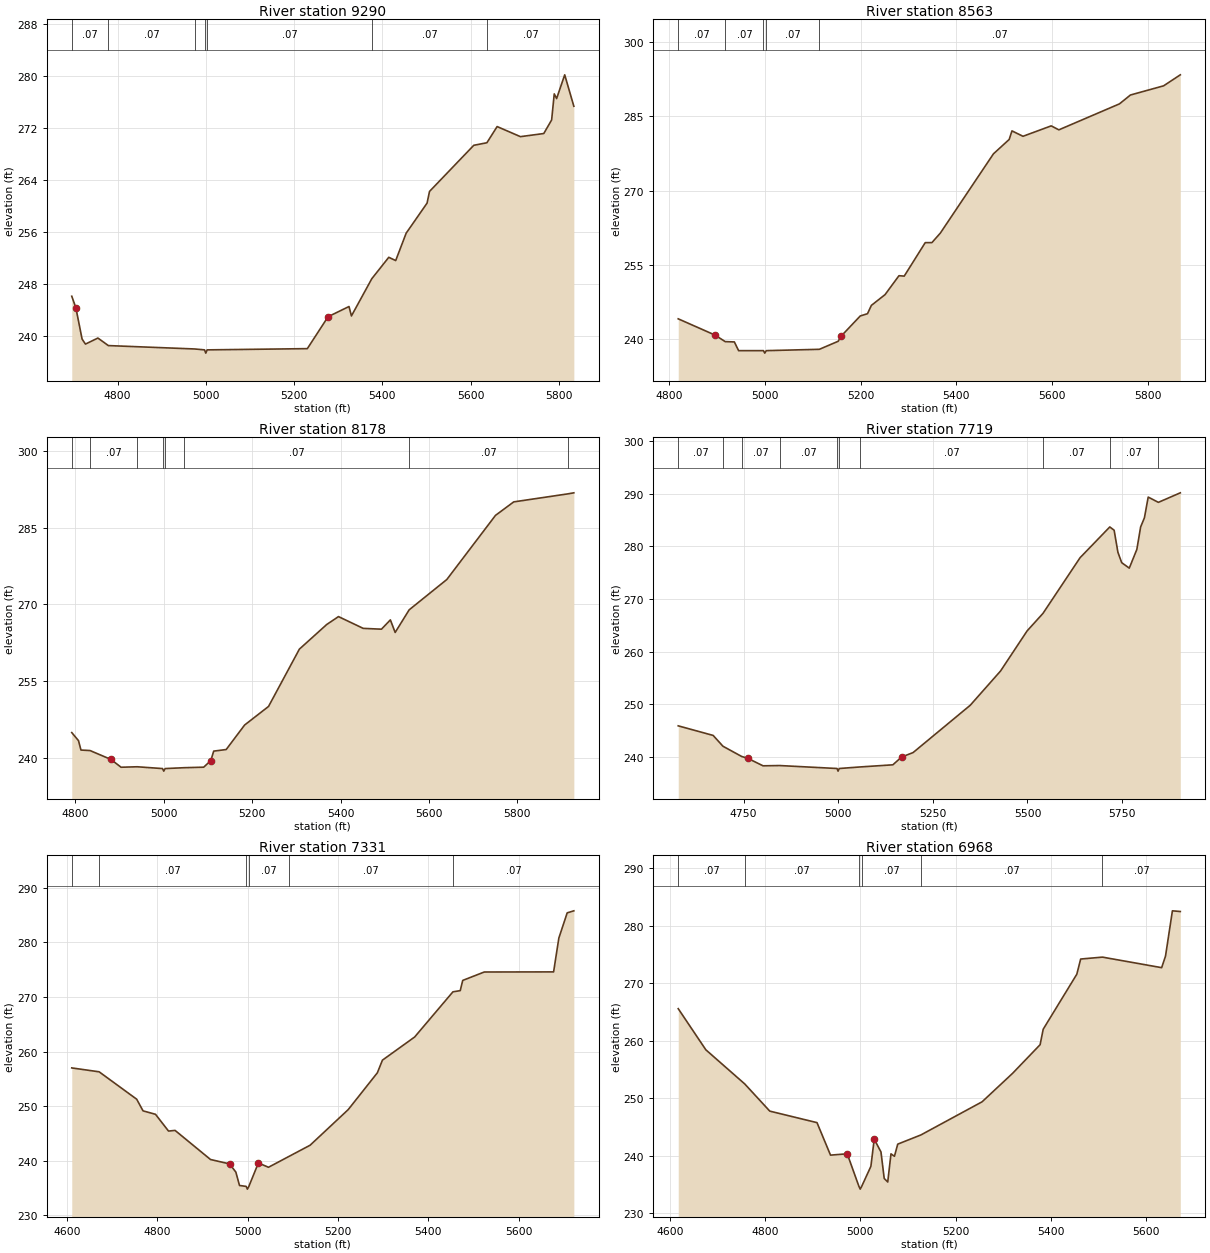
Type RM Length L Ch R = 1 ,9290    ,727,727,727
BEGIN DESCRIPTION:
UNT 03388 IN LACR 12.0
END DESCRIPTION:
XS GIS Cut Line= 3
      3688058.48     10644845.81      3687722.19     10645226.37
      3687477.56     10645806.56
#Sta/Elev= 30
  4696.2   246.1  4705.4  244.34  4719.6  239.51  4727.2  238.74  4755.4  239.67
  4779.1  238.51  4974.5  237.99    4997  237.85  4999.8  237.35    5003  237.85
  5229.9  238.04  5276.9  242.95  5324.3  244.52  5329.8  243.07  5375.9  248.79
  5414.4  252.09  5430.1  251.59  5453.8   255.8  5501.2  260.43  5506.7  262.22
    5607  269.32  5636.7  269.71  5659.9   272.2  5712.7  270.65  5765.6  271.13
  5783.4  273.22  5789.3  277.23  5794.7  276.51    5813  280.16  5833.7  275.33
#Mann= 7 ,-1 , 0
  4696.2     .07       0  4779.1     .07       0  4974.5     .07       0
    4997     .07       0    5003     .07       0  5375.9     .07       0
  5636.7     .07       0
Bank Sta=4705.4,5276.9
XS Rating Curve= 0 ,0
Exp/Cntr=0.3,0.1

Type RM Length L Ch R = 1 ,8563    ,385,385,385
BEGIN DESCRIPTION:
Mapping XS 27113270
END DESCRIPTION:
XS GIS Cut Line= 3
      3687171.65     10644973.94      3687129.56      10645292.5
      3686829.89     10645956.15
#Sta/Elev= 30
  4818.9  244.16  4895.8  240.88  4917.1  239.56  4936.2   239.5  4945.1  237.74
    4997  237.74  4999.8  237.24    5003  237.74  5113.9  238.01  5153.2  239.63
  5159.6  240.68  5199.4  244.74  5214.5  245.19  5222.6  246.87  5251.2  249.04
  5280.3  252.86  5291.3  252.78  5335.2  259.53  5349.2  259.54  5366.8  261.46
  5477.8  277.45  5510.7  280.35  5516.5  282.08  5539.6  280.99  5598.5  283.09
  5614.5  282.29  5741.2  287.53  5764.2  289.32  5833.5  291.17  5868.4  293.39
#Mann= 5 ,-1 , 0
  4818.9     .07       0  4917.1     .07       0    4997     .07       0
    5003     .07       0  5113.9     .07       0
Bank Sta=4895.8,5159.6
XS Rating Curve= 0 ,0
Exp/Cntr=0.3,0.1

Type RM Length L Ch R = 1 ,8178    ,459,459,459
BEGIN DESCRIPTION:
UNT 03388 IN LACR 11.0
END DESCRIPTION:
XS GIS Cut Line= 3
       3686883.6     10644826.45      3686720.57     10645167.51
      3686533.06     10645901.93
#Sta/Elev= 30
  4791.7  244.94  4806.9  243.37  4812.5  241.53  4833.1  241.43  4880.5  239.69
  4903.2  238.17  4939.8  238.26    4997  237.91  4999.8  237.41    5003  237.91
  5046.5  238.08  5090.2  238.18  5106.2  239.47  5112.9  241.32  5141.1  241.63
  5182.8  246.42  5236.9  250.05  5306.7  261.25  5368.6  266.07  5395.2  267.61
  5451.1  265.31  5492.4  265.15  5512.6  266.97  5523.4  264.51  5555.1  268.93
  5640.3  274.86  5750.4  287.39  5791.7  290.03  5913.7  291.59  5927.7   291.8
#Mann= 8 ,-1 , 0
  4791.7     .07       0  4833.1     .07       0  4939.8     .07       0
    4997     .07       0    5003     .07       0  5046.5     .07       0
  5555.1     .07       0  5913.7     .07       0
Bank Sta=4880.5,5106.2
XS Rating Curve= 0 ,0
Exp/Cntr=0.3,0.1

Type RM Length L Ch R = 1 ,7719    ,388,388,388
BEGIN DESCRIPTION:
Mapping XS f9d2dc10
END DESCRIPTION:
XS GIS Cut Line= 3
      3686284.26     10644579.47      3686404.05     10645248.29
      3686404.05     10645895.02
#Sta/Elev= 30
  4577.6  245.89  4669.8  244.07  4695.8  242.01  4745.1  240.07  4761.2  239.72
  4801.6  238.29  4845.4  238.34    4997  237.78  4999.8  237.28    5003  237.78
  5057.1  238.07  5144.5  238.48  5167.6  239.96    5198  240.81    5349  249.81
    5429  256.32    5499  263.93  5541.1  267.28    5639  277.86  5717.5  283.71
    5729  283.09    5739  278.89    5749  276.92    5769  275.88    5789  279.44
    5799  283.71    5809  285.45    5819  289.39  5845.9  288.39  5903.8   290.2
#Mann= 10 ,-1 , 0
  4577.6     .07       0  4695.8     .07       0  4745.1     .07       0
  4845.4     .07       0    4997     .07       0    5003     .07       0
  5057.1     .07       0  5541.1     .07       0  5717.5     .07       0
  5845.9     .07       0
Bank Sta=4761.2,5167.6
XS Rating Curve= 0 ,0
Exp/Cntr=0.3,0.1

Type RM Length L Ch R = 1 ,7331    ,363,363,363
BEGIN DESCRIPTION:
Mapping XS 98e9eb23
END DESCRIPTION:
XS GIS Cut Line= 3
      3685802.16     10644916.63      3686119.01     10645315.95
      3686349.06     10645871.55
#Sta/Elev= 30
  4611.1     257  4671.6  256.29  4754.8  251.27  4768.8  249.14  4796.4  248.51
  4825.2  245.44  4839.7  245.56  4918.2  240.23  4960.3  239.43  4974.2  237.93
  4982.3  235.48    4997  235.31  4999.8  234.81    5003  235.31  5024.1   239.6
  5046.4  238.81  5090.9  240.76  5138.6  242.85  5222.9  249.37  5287.4  256.11
  5298.6  258.42  5369.9  262.66  5454.6  270.93  5470.8  271.15  5476.3  273.02
    5524  274.56  5677.4  274.58    5689  280.77  5707.5  285.39  5722.2  285.76
#Mann= 6 ,-1 , 0
  4611.1     .07       0  4671.6     .07       0    4997     .07       0
    5003     .07       0  5090.9     .07       0  5454.6     .07       0
Bank Sta=4960.3,5024.1
XS Rating Curve= 0 ,0
Exp/Cntr=0.3,0.1

Type RM Length L Ch R = 1 ,6968    ,283,283,283
BEGIN DESCRIPTION:
Mapping XS 00d0a7ea
END DESCRIPTION:
XS GIS Cut Line= 3
      3685524.39     10645193.56      3685927.17     10645627.58
      3686291.75      10645912.3
#Sta/Elev= 30
  4617.5  265.55  4675.5   258.4  4757.3  252.46  4809.8  247.74    4909  245.74
  4937.4  240.09  4972.5  240.32    4997  234.68  4999.8  234.18    5003  234.68
  5022.2  238.14  5029.2  242.86  5043.4  240.64  5050.2  236.03  5057.6  235.42
  5064.4  240.31  5071.7  239.89  5078.6     242  5127.3   243.6  5255.8  249.36
    5320  254.32  5377.7  259.29  5384.2  261.98  5454.8  271.54  5462.9  274.18
  5508.7  274.51    5633  272.68  5641.1  274.68  5655.6  282.56  5672.2  282.44
#Mann= 6 ,-1 , 0
  4617.5     .07       0  4757.3     .07       0    4997     .07       0
    5003     .07       0  5127.3     .07       0  5508.7     .07       0
Bank Sta=4972.5,5029.2
XS Rating Curve= 0 ,0
Exp/Cntr=0.3,0.1

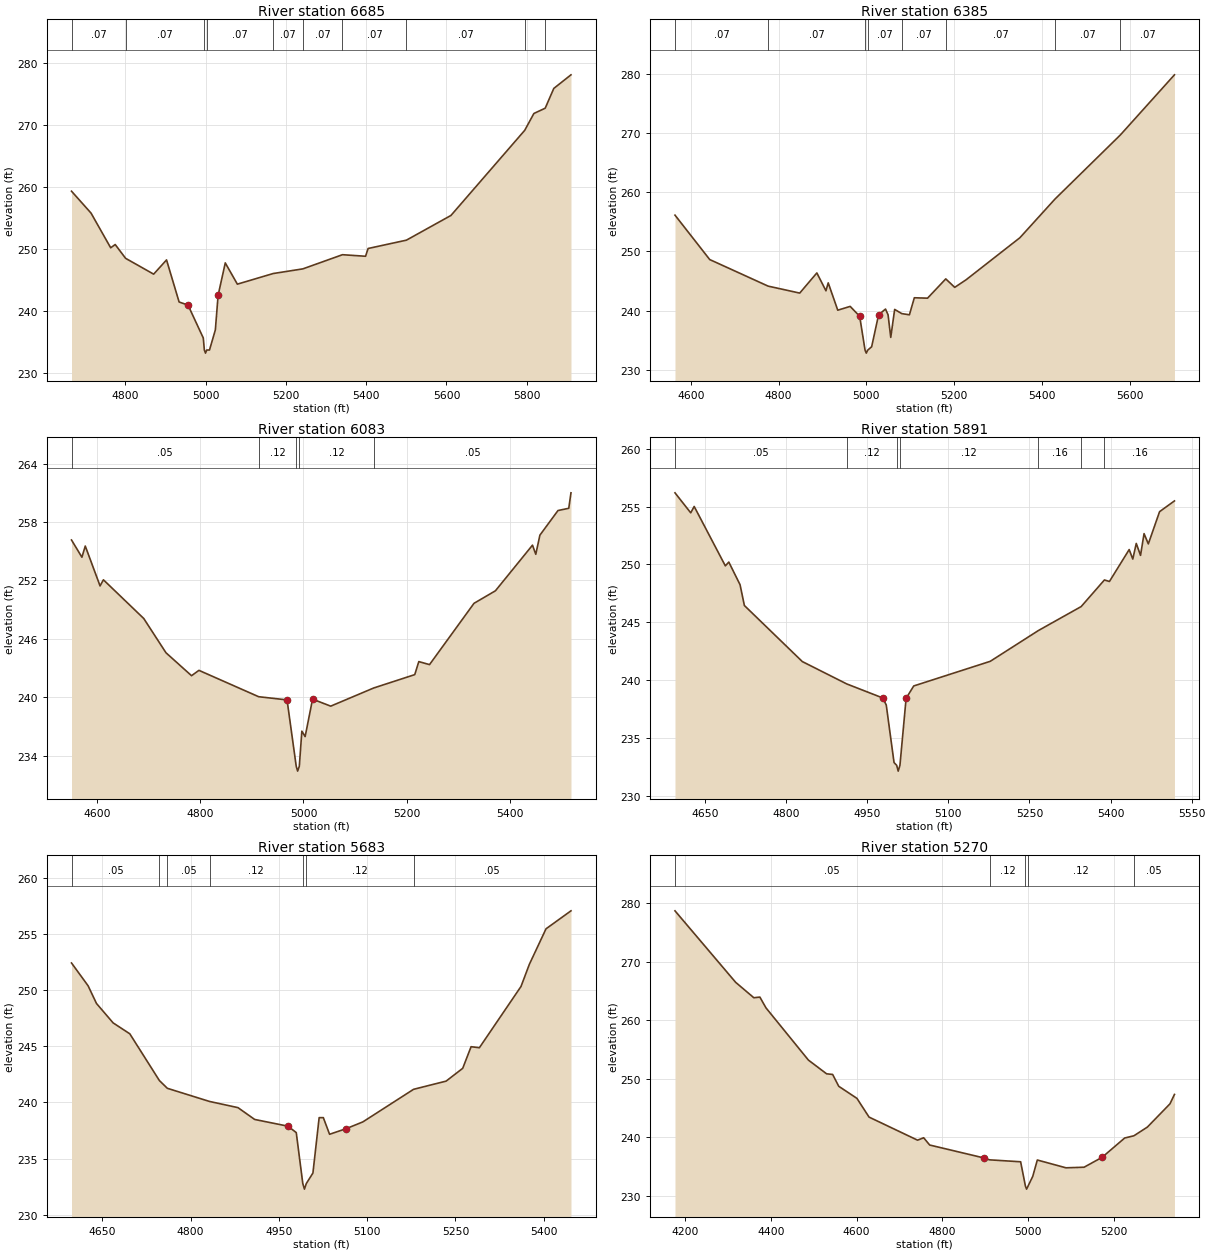
Type RM Length L Ch R = 1 ,6685    ,300,300,300
BEGIN DESCRIPTION:
Mapping XS ca55e514
END DESCRIPTION:
XS GIS Cut Line= 3
      3685437.59     10645328.99       3685611.2      10645784.7
      3686084.27     10646374.96
#Sta/Elev= 30
  4666.1  259.33  4714.7  255.81  4763.7  250.22  4774.9  250.75  4800.8  248.53
  4870.7  245.98  4902.8  248.27  4934.1   241.5  4956.3     241  4994.3  235.71
    4997  233.77  4999.8  233.27    5003  233.77  5009.8  233.77  5024.4  237.01
  5031.2  242.55  5049.1  247.79  5079.2  244.37  5168.4  246.08  5242.4  246.83
    5341  249.11  5398.5  248.86  5404.9  250.11  5500.3  251.45  5611.3  255.43
    5795  269.13  5817.8  271.84    5846  272.69  5867.4  275.87  5910.2  278.06
#Mann= 10 ,-1 , 0
  4666.1     .07       0  4800.8     .07       0    4997     .07       0
    5003     .07       0  5168.4     .07       0  5242.4     .07       0
    5341     .07       0  5500.3     .07       0    5795     .07       0
    5846     .07       0
Bank Sta=4956.3,5031.2
XS Rating Curve= 0 ,0
Exp/Cntr=0.3,0.1

Type RM Length L Ch R = 1 ,6385    ,302,302,302
BEGIN DESCRIPTION:
UNT 03388 IN LACR 10.0
END DESCRIPTION:
XS GIS Cut Line= 4
      3685388.98     10645401.87      3685277.86     10645756.06
      3685343.83     10645870.64       3685187.6     10646485.17
#Sta/Elev= 30
  4564.1  256.14  4643.2  248.63  4776.1  244.14  4848.2  242.96  4887.2  246.37
  4907.9  243.35  4913.1  244.69  4934.8  240.07  4963.1  240.71  4984.7  239.04
    4997  233.31  4999.8  232.81    5003  233.31    5012  233.89  5027.8  239.29
  5043.6  240.26  5049.4  239.28  5055.5  235.47  5064.4   240.2  5080.6  239.49
    5098  239.29  5109.2  242.17  5139.3   242.1  5180.8  245.36  5201.2  243.93
  5226.9   245.2  5349.6  252.32  5429.7  258.87  5578.5   269.7  5701.6  279.86
#Mann= 8 ,-1 , 0
  4564.1     .07       0  4776.1     .07       0    4997     .07       0
    5003     .07       0  5080.6     .07       0  5180.8     .07       0
  5429.7     .07       0  5578.5     .07       0
Bank Sta=4984.7,5027.8
XS Rating Curve= 0 ,0
Exp/Cntr=0.3,0.1

Type RM Length L Ch R = 1 ,6083    ,192,192,192
BEGIN DESCRIPTION:
UNT 03388 IN LACR 9.0
END DESCRIPTION:
XS GIS Cut Line= 2
      3685330.22     10645412.98      3684719.64      10646165.8
#Sta/Elev= 30
  4549.8  256.16    4570  254.39  4576.5  255.54  4605.2  251.44  4611.7  252.07
    4690  248.09  4733.1  244.57  4782.7  242.21  4797.1  242.76    4913  240.05
  4968.1  239.72  4985.9   232.9  4988.6   232.4  4991.9   232.9  4996.8  236.51
  5003.2  235.95  5017.6   239.8  5052.8  239.08  5136.4  240.95  5215.9  242.32
  5223.8  243.66  5244.6  243.35  5330.9  249.65  5372.5  250.94  5444.4  255.63
  5450.8  254.69  5458.8  256.66  5493.9  259.19  5514.8  259.42  5519.1  261.01
#Mann= 5 ,-1 , 0
  4549.8     .05       0    4913     .12       0  4985.9     .07       0
  4991.9     .12       0  5136.4     .05       0
Bank Sta=4968.1,5017.6
XS Rating Curve= 0 ,0
Exp/Cntr=0.3,0.1

Type RM Length L Ch R = 1 ,5891    ,208,208,208
BEGIN DESCRIPTION:
Mapping XS 493e4bdf
END DESCRIPTION:
XS GIS Cut Line= 2
      3685146.16     10645336.63      3684566.36     10646055.31
#Sta/Elev= 30
  4594.8   256.2  4623.9  254.47  4630.3  255.02  4687.9  249.88  4694.3  250.21
  4715.1  248.25  4723.1  246.45  4830.2   241.6  4912.1  239.67  4978.9  238.45
  4985.4  237.84  4999.8  232.86  5004.7  232.62  5007.5  232.12  5010.7  232.62
  5022.1  238.42  5036.2  239.49  5177.6  241.62  5266.5  244.28  5345.8  246.36
  5388.7  248.66    5398  248.53  5434.5  251.29  5441.2  250.47  5447.6  251.82
  5455.5  250.79    5462  252.67  5469.9  251.78  5490.7  254.57  5518.2   255.5
#Mann= 7 ,-1 , 0
  4594.8     .05       0  4912.1     .12       0  5004.7     .07       0
  5010.7     .12       0  5266.5     .16       0  5345.8     .05       0
  5388.7     .16       0
Bank Sta=4978.9,5022.1
XS Rating Curve= 0 ,0
Exp/Cntr=0.3,0.1

Type RM Length L Ch R = 1 ,5683    ,413,413,413
BEGIN DESCRIPTION:
UNT 03388 IN LACR 8.0
END DESCRIPTION:
XS GIS Cut Line= 3
      3684999.58     10645260.22      3684699.61     10645560.19
       3684399.6      10645860.2
#Sta/Elev= 30
  4597.8   252.4    4626  250.37  4640.2   248.8  4668.5  247.07  4696.8   246.1
  4747.1  241.94  4760.6  241.25  4832.3  240.08  4880.6  239.53  4908.9  238.48
  4965.5  237.88  4979.6  237.31  4990.7  232.78  4993.5  232.28  4996.7  232.78
  5007.9  233.71  5018.5  238.64  5025.6  238.64  5036.2  237.16  5064.4  237.66
  5092.7  238.26  5178.9  241.16  5234.2  241.89  5262.4  243.03  5276.6  244.95
  5290.7  244.86  5361.4  250.31  5375.6  252.28  5403.9  255.44  5446.3  257.04
#Mann= 7 ,-1 , 0
  4597.8     .05       0  4747.1     .12       0  4760.6     .05       0
  4832.3     .12       0  4990.7     .07       0  4996.7     .12       0
  5178.9     .05       0
Bank Sta=4965.5,5064.4
XS Rating Curve= 0 ,0
Exp/Cntr=0.3,0.1

Type RM Length L Ch R = 1 ,5270    ,376,376,376
BEGIN DESCRIPTION:
UNT 03388 IN LACR 7.0
END DESCRIPTION:
XS GIS Cut Line= 3
      3684949.64     10644760.16      3684349.61     10645360.19
      3684249.61     10645660.19
#Sta/Elev= 30
  4176.4  278.66  4317.9  266.45  4360.3  263.82  4374.4  263.93  4388.6  262.09
  4487.6  253.17    4530  250.83  4544.1  250.72  4558.3   248.7  4600.7  246.64
    4629  243.44  4742.1   239.5  4756.3  239.91  4770.4  238.67  4897.7  236.45
    4910  236.14  4982.5  235.81  4993.7  231.64  4996.4  231.14  4999.7  231.64
  5010.8  233.33  5021.4  236.11  5088.2  234.78  5130.4  234.88  5172.5  236.57
  5225.2  239.87  5246.6  240.25    5278  241.73  5330.7   245.7  5341.2  247.31
#Mann= 5 ,-1 , 0
  4176.4     .05       0    4910     .12       0  4993.7     .07       0
  4999.7     .12       0  5246.6     .05       0
Bank Sta=4897.7,5172.5
XS Rating Curve= 0 ,0
Exp/Cntr=0.3,0.1

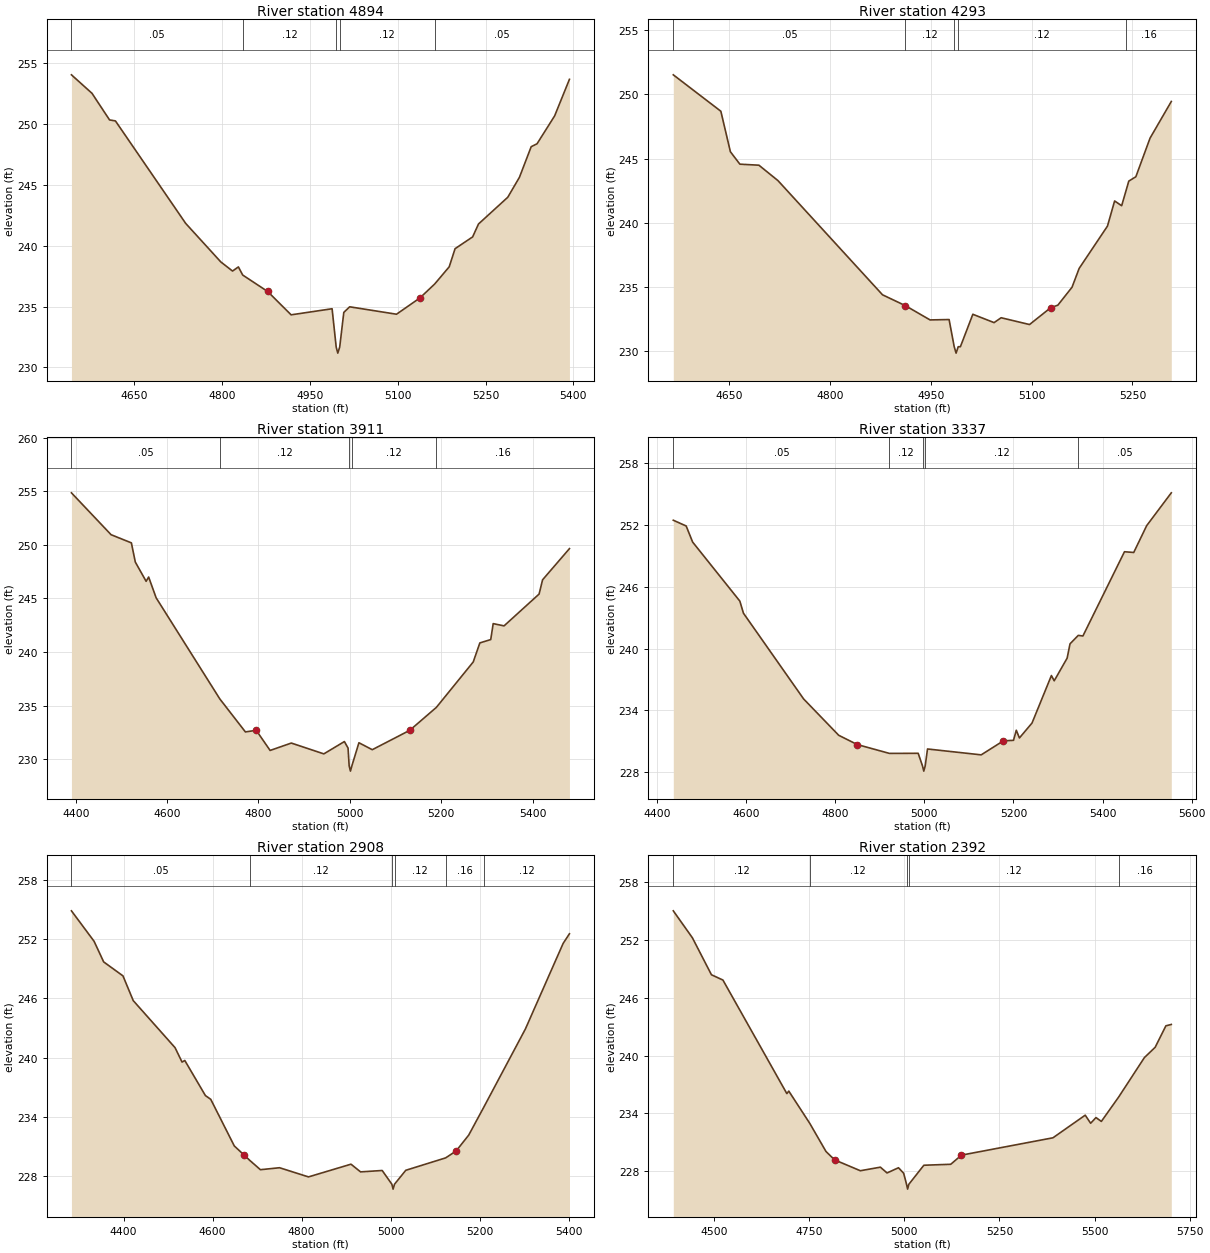
Type RM Length L Ch R = 1 ,4894    ,601,601,601
BEGIN DESCRIPTION:
UNT 03388 IN LACR 6.0
END DESCRIPTION:
XS GIS Cut Line= 2
      3683992.62     10644935.12      3683996.96     10645785.51
#Sta/Elev= 30
  4542.8  254.06  4577.9  252.54  4607.9  250.35  4617.9  250.27  4737.9  241.84
  4797.9  238.67  4817.9  237.92  4827.9  238.26  4835.3  237.59  4877.9  236.24
  4917.9  234.32  4987.9  234.82  4994.9  231.67  4997.6  231.17  5000.9  231.67
  5007.9  234.52  5017.9  234.98  5097.9  234.37  5137.9  235.71    5163  236.85
  5187.9  238.27  5197.9  239.76  5227.9  240.73  5237.9  241.79  5287.9  243.99
  5307.9  245.64  5327.9  248.15  5337.9  248.39  5367.9  250.68  5393.2  253.69
#Mann= 5 ,-1 , 0
  4542.8     .05       0  4835.3     .12       0  4994.9     .07       0
  5000.9     .12       0    5163     .05       0
Bank Sta=4877.9,5137.9
XS Rating Curve= 0 ,0
Exp/Cntr=0.3,0.1

Type RM Length L Ch R = 1 ,4293    ,382,382,382
BEGIN DESCRIPTION:
UNT 03388 IN LACR 5.0
END DESCRIPTION:
XS GIS Cut Line= 3
      3683749.61     10645010.18      3683449.61     10645310.19
      3683349.61     10645610.19
#Sta/Elev= 30
  4567.2  251.53  4637.9  248.69  4652.1  245.53  4666.2  244.56  4694.5  244.48
  4722.8  243.28  4878.3  234.37  4912.4  233.52    4949  232.41  4977.3  232.44
  4984.9  230.32  4987.7  229.82  4990.9  230.32  4994.1  230.32  5012.6  232.85
  5044.2   232.2  5054.7  232.58  5096.9  232.05  5128.5  233.37    5139  233.56
  5160.1  234.96  5170.7  236.43  5212.8  239.73  5223.4  241.69  5233.9  241.32
  5240.1  242.44  5244.5  243.24    5255  243.58  5276.1  246.59  5307.7  249.45
#Mann= 5 ,-1 , 0
  4567.2     .05       0  4912.4     .12       0  4984.9     .07       0
  4990.9     .12       0  5240.1     .16       0
Bank Sta=4912.4,5128.5
XS Rating Curve= 0 ,0
Exp/Cntr=0.3,0.1

Type RM Length L Ch R = 1 ,3911    ,574,574,574
BEGIN DESCRIPTION:
UNT 03388 IN LACR 4.0
END DESCRIPTION:
XS GIS Cut Line= 2
       3683740.6     10644859.89      3682735.43     10645281.74
#Sta/Elev= 30
  4390.7  254.86  4477.5  250.95  4521.9  250.19  4530.5   248.4  4554.2   246.6
  4559.7     247  4576.1  245.06  4715.5  235.62  4771.5  232.54  4795.2  232.69
  4825.6  230.81    4872   231.5  4943.2  230.49  4988.2  231.64  4996.2  231.03
  4998.6  229.38  5001.4  228.88  5004.6  229.38    5020  231.53  5049.2  230.88
  5131.3  232.69  5189.5  234.83  5270.2  239.07  5284.7  240.85  5308.5  241.16
  5313.9  242.65  5337.7  242.44  5414.4  245.41    5422  246.74  5480.8  249.65
#Mann= 5 ,-1 , 0
  4390.7     .05       0  4715.5     .12       0  4998.6     .07       0
  5004.6     .12       0  5189.5     .16       0
Bank Sta=4795.2,5131.3
XS Rating Curve= 0 ,0
Exp/Cntr=0.3,0.1

Type RM Length L Ch R = 1 ,3337    ,429,429,429
BEGIN DESCRIPTION:
UNT 03388 IN LACR 3.0
END DESCRIPTION:
XS GIS Cut Line= 2
      3683475.01     10644255.69       3682589.6     10644937.98
#Sta/Elev= 30
  4436.5  252.46  4465.4   251.9  4479.9  250.34  4585.8  244.61    4594  243.43
    4729  235.11  4807.8  231.58  4849.4  230.68  4921.7  229.82  4986.2  229.83
  4995.9   228.6  4998.7   228.1  5001.9   228.6  5007.1  230.25  5127.6  229.68
  5177.4  231.04  5200.1  231.09  5206.4  232.07  5213.4  231.32  5241.7  232.77
  5285.2  237.38  5291.5  236.87  5320.5  239.07    5327  240.46  5345.5  241.28
  5355.9  241.22  5449.2   249.4    5470  249.33    5499  251.93  5554.3  255.12
#Mann= 5 ,-1 , 0
  4436.5     .05       0  4921.7     .12       0  4995.9     .07       0
  5001.9     .12       0  5345.5     .05       0
Bank Sta=4849.4,5177.4
XS Rating Curve= 0 ,0
Exp/Cntr=0.3,0.1

Type RM Length L Ch R = 1 ,2908    ,516,516,516
BEGIN DESCRIPTION:
UNT 03388 IN LACR 2.0
END DESCRIPTION:
XS GIS Cut Line= 3
      3683349.62     10643960.18      3682749.61     10644310.19
      3682449.61     10644610.19
#Sta/Elev= 30
  4282.8  254.89  4333.7   251.8  4355.2  249.71  4398.6  248.29  4421.7  245.78
  4515.6  241.01  4531.3  239.55  4537.5  239.71  4583.8  236.15  4595.8  235.77
  4648.7  231.04  4670.2  230.14  4683.4  229.58  4707.4  228.63  4750.4  228.83
  4815.4   227.9  4910.9  229.19  4932.4  228.41    4981  228.55  5002.7  227.16
  5005.5  226.66  5008.7  227.16    5034  228.57  5123.6  229.83  5147.1  230.53
  5175.4  232.14    5209  234.95  5302.7   242.9  5387.6  251.59  5401.7  252.56
#Mann= 6 ,-1 , 0
  4282.8     .05       0  4683.4     .12       0  5002.7     .07       0
  5008.7     .12       0  5123.6     .16       0    5209     .12       0
Bank Sta=4670.2,5147.1
XS Rating Curve= 0 ,0
Exp/Cntr=0.3,0.1

Type RM Length L Ch R = 1 ,2392    ,0,0,0
BEGIN DESCRIPTION:
UNT 03388 IN LACR 1.0
END DESCRIPTION:
XS GIS Cut Line= 3
      3683349.61     10643910.19      3682749.61     10643860.19
       3682249.6      10644360.2
#Sta/Elev= 30
  4392.7  255.03  4442.9  252.23    4493  248.39  4523.2  247.84  4691.2  236.05
  4696.3  236.31  4751.3  232.97  4794.1  230.04  4816.7  229.17  4884.4  228.04
  4937.1  228.41  4954.6  227.81  4984.7  228.35  4998.3  227.78  5005.9  226.63
  5008.7  226.13  5011.9  226.63  5051.4  228.61  5122.1  228.71  5150.3  229.66
  5390.8  231.46  5475.6  233.81  5489.8  232.97  5503.9  233.56    5518  233.16
  5563.3  235.68  5631.2  239.79  5659.5  240.86  5687.7  243.09  5701.9  243.23
#Mann= 5 ,-1 , 0
  4392.7     .12       0  4751.3     .12       0  5005.9     .07       0
  5011.9     .12       0  5563.3     .16       0
Bank Sta=4816.7,5150.3
XS Rating Curve= 0 ,0
Exp/Cntr=0.3,0.1

Chan Stop Cuts=-1
Use User Specified Reach Order=0
Composite Channel Slope=5