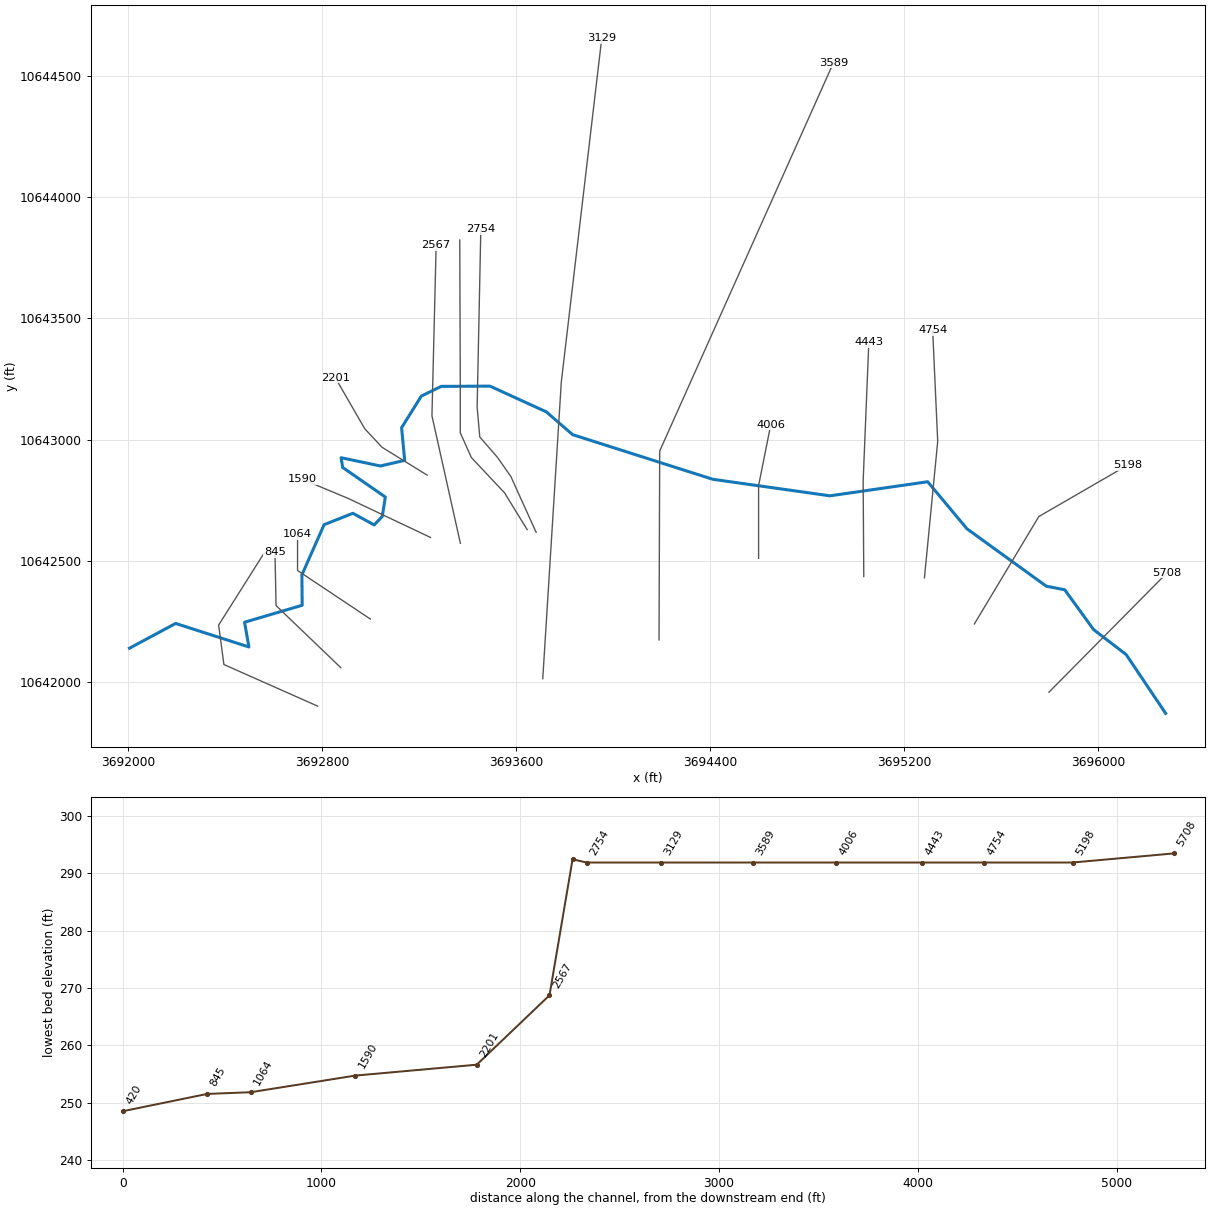
--- UNT 03399 IN LACR.prj (project) ---

Proj Title=UNT 03399 IN LACR Base Level Engineering
Current Plan=p01
Default Exp/Contr=0.3,0.1
English Units
Geom File=g01
Flow File=f01
Plan File=p01
Y Axis Title=Elevation
X Axis Title(PF)=Main Channel Distance
X Axis Title(XS)=Station
BEGIN DESCRIPTION:
UNT 03399 IN LACR
END DESCRIPTION:
DSS Export Rating Curves= 0
DSS Export Rating Curve Sorted= 0
DSS Export Volume Flow Curves= 0
DXF OffsetX= 0
DXF OffsetY= 0
DXF ScaleX= 1
DXF ScaleY= 10

--- UNT 03399 IN LACR.p01 (plan) ---

Plan Title=Multiple Run
Short Identifier=Multiple
Geom File=g01
Flow File=f01
Subcritical Flow
K Sum by GR= 0
Std Step Tol= 0.01
Critical Tol= 0.01
Num of Std Step Trials= 20
Max Error Tol= 0.3
Flow Tol Ratio= 0.001
Split Flow NTrial= 30
Split Flow Tol= 0.02
Split Flow Ratio= 0.02
Log Output Level= 0
Friction Slope Method= 1
Unsteady Friction Slope Method= 2
Unsteady Bridges Friction Slope Method= 1
Parabolic Critical Depth
Global Vel Dist=  1 , 1 , 1
Global Log Level= 0
CheckData=True
Encroach Param= -1, 0, 0, 0
BEGIN DESCRIPTION:
Multiple Run
END DESCRIPTION:

--- UNT 03399 IN LACR.f01 (steady flow) ---

Flow Title=Multiple
Number of Profiles=7
Profile Names=10-year,25-year,50-year,1pct_min,100-year,1pct_plu,500-year
River Rch & RM= UNT 03399 IN LAC,Reach-1,5708
     390     516     618     545     737     997    1051
Boundary for River Rch & Prof#=UNT 03399 IN LAC,Reach-1,1
Up Type=0
Dn Type=3
Dn Slope=0.005
Boundary for River Rch & Prof#=UNT 03399 IN LAC,Reach-1,2
Up Type=0
Dn Type=3
Dn Slope=0.005
Boundary for River Rch & Prof#=UNT 03399 IN LAC,Reach-1,3
Up Type=0
Dn Type=3
Dn Slope=0.005
Boundary for River Rch & Prof#=UNT 03399 IN LAC,Reach-1,4
Up Type=0
Dn Type=3
Dn Slope=0.005
Boundary for River Rch & Prof#=UNT 03399 IN LAC,Reach-1,5
Up Type=0
Dn Type=3
Dn Slope=0.005
Boundary for River Rch & Prof#=UNT 03399 IN LAC,Reach-1,6
Up Type=0
Dn Type=3
Dn Slope=0.005
Boundary for River Rch & Prof#=UNT 03399 IN LAC,Reach-1,7
Up Type=0
Dn Type=3
Dn Slope=0.005

--- UNT 03399 IN LACR.g01 (geometry) ---

Geom Title=Existing Conditions
Program Version=4.10

River Reach=UNT 03399 IN LAC,Reach-1
Reach XY= 30
      3696277.13     10641871.41      3696114.33      10642113.8
      3695980.11     10642216.75      3695861.18     10642380.81
      3695785.23     10642395.57      3695458.26     10642632.11
       3695296.5       10642826.      3694893.75       10642768.
      3694411.25       10642836.      3693833.25       10643020.
      3693724.75       10643114.      3693492.75       10643220.
      3693291.75       10643219.      3693209.75       10643179.
       3693128.5       10643049.        3693141.       10642914.
        3693041.       10642891.      3692879.25       10642925.
       3692885.5       10642885.      3693061.25       10642763.
      3693048.75       10642683.       3693015.5       10642648.
      3692927.75       10642696.        3692809.       10642649.
       3692717.5       10642442.      3692718.75       10642317.
      3692481.25       10642247.      3692499.25       10642145.
      3692197.25       10642242.        3692007.       10642140.

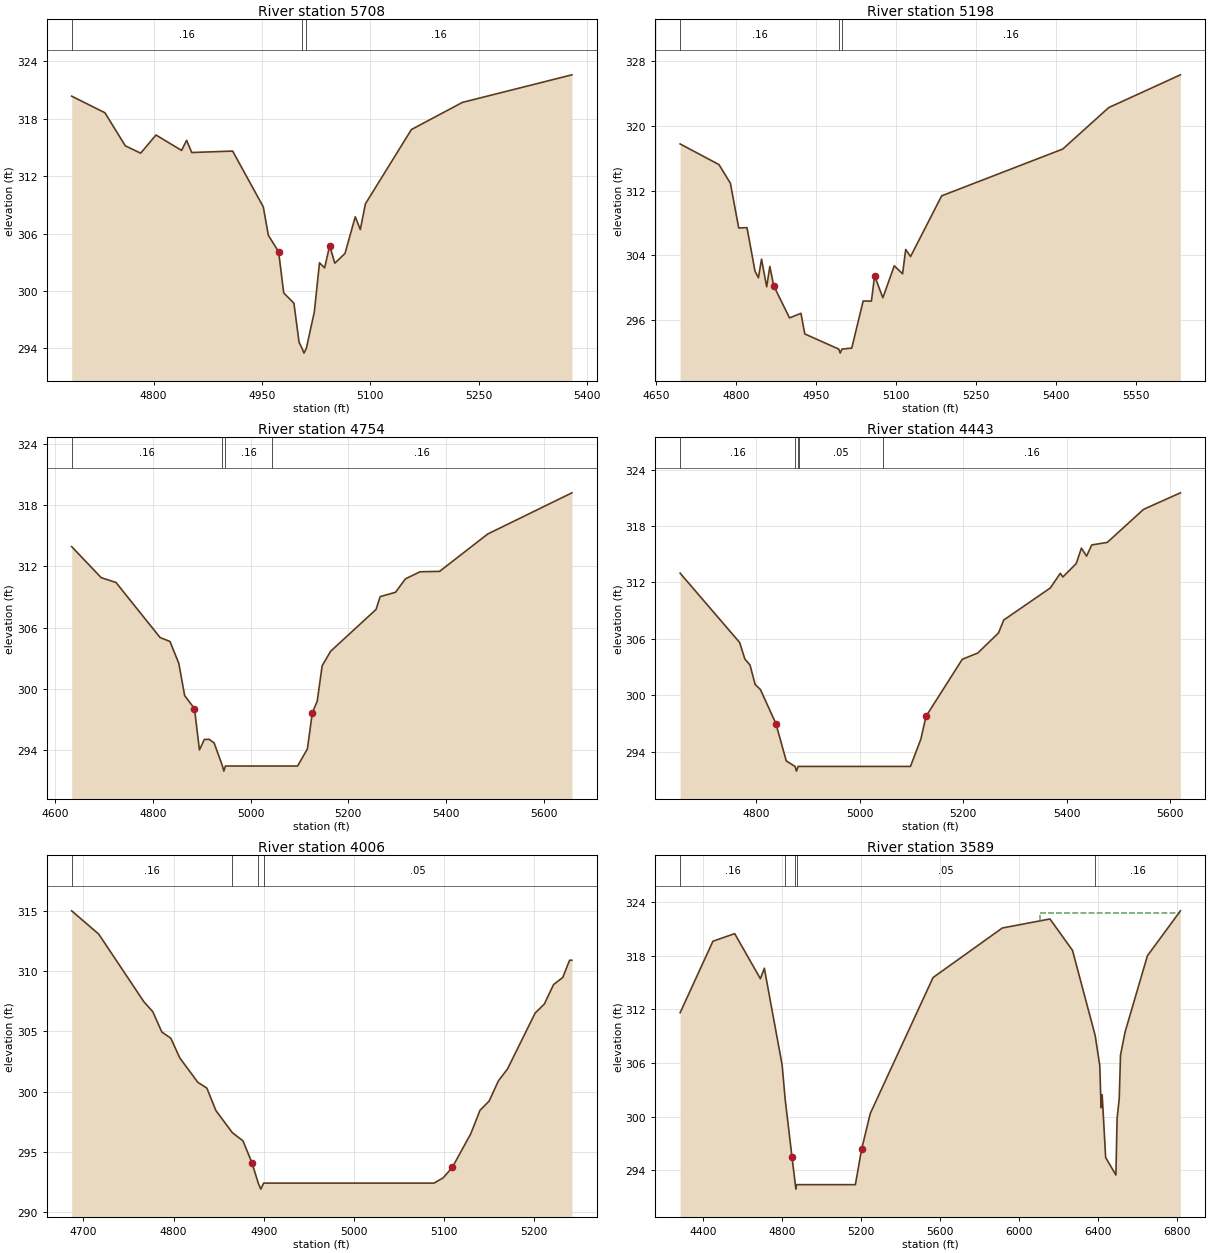
Type RM Length L Ch R = 1 ,5708    ,510,510,510
BEGIN DESCRIPTION:
UNT 03399 IN LACR 9.0
END DESCRIPTION:
XS GIS Cut Line= 2
      3695796.13     10641958.64      3696283.12     10642450.83
#Sta/Elev= 30
  4686.5  320.36  4732.5  318.63  4760.7  315.17    4782   314.4  4803.2   316.3
  4838.6  314.69  4845.6  315.74  4852.7  314.47  4909.3  314.62  4951.7  308.79
  4958.7  305.82  4972.9   304.1    4980  299.79  4994.1  298.72  5001.2  294.65
  5005.3     294    5008   293.5  5011.3     294  5022.4  297.83  5029.5  302.94
  5036.6  302.41  5043.6  304.74  5050.7   302.9  5064.8  303.92    5079  307.75
    5086  306.42  5093.1  309.11  5156.7  316.87  5227.4  319.71  5378.9  322.59
#Mann= 3 ,-1 , 0
  4686.5     .16       0  5005.3     .07       0  5011.3     .16       0
Bank Sta=4972.9,5043.6
XS Rating Curve= 0 ,0
Exp/Cntr=0.3,0.1

Type RM Length L Ch R = 1 ,5198    ,444,444,444
BEGIN DESCRIPTION:
Mapping XS 6cc8d2cf
END DESCRIPTION:
XS GIS Cut Line= 3
      3695488.84      10642239.9      3695754.45     10642682.58
      3696119.07     10642893.54
#Sta/Elev= 30
  4695.8  317.75  4768.6   315.2    4790  312.89  4805.6  307.37  4821.1  307.41
  4836.1  302.04  4842.5  301.22  4848.3  303.52    4858   300.1  4863.9  302.62
  4871.1  300.24  4900.8  296.26  4922.2  296.83  4929.4  294.28    4993  292.41
  4995.8  291.91    4999  292.41  5017.4  292.53  5038.8  298.35  5054.3  298.34
  5060.2  301.46  5075.7  298.75  5097.1   302.7  5112.7  301.71  5118.5  304.72
  5127.6  303.84  5185.9  311.34  5412.8  317.12  5498.9  322.24  5633.3  326.29
#Mann= 3 ,-1 , 0
  4695.8     .16       0    4993     .07       0    4999     .16       0
Bank Sta=4871.1,5060.2
XS Rating Curve= 0 ,0
Exp/Cntr=0.3,0.1

Type RM Length L Ch R = 1 ,4754    ,311,311,311
BEGIN DESCRIPTION:
Mapping XS 49627c10
END DESCRIPTION:
XS GIS Cut Line= 3
      3695283.09     10642429.94      3695337.78     10642992.47
      3695316.95     10643450.81
#Sta/Elev= 30
  4633.7  313.95  4694.2   310.9  4724.4  310.43  4814.8  305.02  4834.9  304.64
    4853  302.49    4865  299.32  4885.1  298.05  4895.2  293.99  4905.2  295.02
  4915.3  295.03  4925.3  294.68  4942.4  292.41  4945.2  291.91  4948.4  292.41
  5043.8  292.41  5096.1  292.41  5116.2  294.09  5126.3  297.64  5136.3  298.77
  5146.4  302.25  5163.8  303.68  5256.7  307.78  5265.2  309.04  5296.7  309.47
  5316.7  310.78  5346.8  311.48  5386.8  311.52  5485.4  315.19  5657.7  319.23
#Mann= 4 ,-1 , 0
  4633.7     .16       0  4942.4    .033       0  4948.4     .16       0
  5043.8     .16       0
Bank Sta=4885.1,5126.3
XS Rating Curve= 0 ,0
Exp/Cntr=0.3,0.1

Type RM Length L Ch R = 1 ,4443    ,437,437,437
BEGIN DESCRIPTION:
Mapping XS 2c3caec4
END DESCRIPTION:
XS GIS Cut Line= 3
      3695033.09     10642435.21      3695030.49     10642828.41
      3695053.93     10643401.32
#Sta/Elev= 30
  4653.3  312.99  4768.3  305.61  4778.3  303.86  4788.3  303.21  4798.3  301.13
  4808.3  300.61  4838.3  296.98  4858.3     293  4875.3  292.41    4878  291.91
  4881.3  292.41  4883.3  292.41  5044.8  292.41  5098.3  292.41  5118.3   295.3
  5128.4  297.75  5198.4  303.82  5228.4  304.49  5268.5  306.63  5278.5     308
  5368.6  311.42  5387.8  312.98  5392.8  312.59  5418.6  314.01  5428.6  315.66
  5438.6  314.81  5448.6     316  5478.6  316.27  5548.7  319.79  5619.9  321.55
#Mann= 5 ,-1 , 0
  4653.3     .16       0  4875.3    .033       0  4881.3     .16       0
  4883.3     .05       0  5044.8     .16       0
Bank Sta=4838.3,5128.4
XS Rating Curve= 0 ,0
Exp/Cntr=0.3,0.1

Type RM Length L Ch R = 1 ,4006    ,417,417,417
BEGIN DESCRIPTION:
UNT 03399 IN LACR 8.0
END DESCRIPTION:
XS GIS Cut Line= 3
      3694599.61     10642510.16      3694599.61     10642810.19
      3694649.61     10643060.21
#Sta/Elev= 30
  4686.9     315  4716.9  313.07  4766.9  307.47  4776.9  306.63  4786.9  304.95
  4796.9  304.43  4806.9  302.79  4826.9  300.77  4836.9  300.29  4846.9  298.43
  4865.2  296.59  4876.9  295.92  4886.9   294.1  4893.9  292.41  4896.7  291.91
  4899.9  292.41  5088.9  292.41  5099.1  292.85  5109.3  293.73  5129.7  296.51
  5139.9  298.45  5150.1  299.22  5160.3  300.89  5170.5  301.89  5201.1  306.52
  5211.3  307.27  5221.5  308.88  5231.7  309.47  5239.3   310.9  5241.9   310.9
#Mann= 4 ,-1 , 0
  4686.9     .16       0  4865.2     .05       0  4893.9    .033       0
  4899.9     .05       0
Bank Sta=4886.9,5109.3
XS Rating Curve= 0 ,0
Exp/Cntr=0.3,0.1

Type RM Length L Ch R = 1 ,3589    ,460,460,460
BEGIN DESCRIPTION:
UNT 03399 IN LACR 7.0
END DESCRIPTION:
XS GIS Cut Line= 3
      3694189.33     10642174.15      3694192.09     10642952.67
      3694908.08     10644552.64
#Sta/Elev= 30
  4285.5  311.64  4451.5  319.63  4561.5  320.48  4691.5  315.44  4711.5  316.61
  4801.5  305.81  4816.9  301.97  4851.5   295.5  4868.5  292.41  4871.3  291.91
  4874.5  292.41  5172.2  292.41  5203.7  296.36  5247.6  300.37  5565.3  315.57
  5915.8  321.11  6156.9  322.12  6270.9  318.61  6385.6  309.09  6408.9  305.74
  6415.5  301.01    6421  302.47  6438.7  295.44  6490.6  293.49  6496.5   299.8
  6507.5  302.06  6513.8  306.89    6537  309.48  6649.9     318  6816.9  323.03
#Mann= 5 ,-1 , 0
  4285.5     .16       0  4816.9     .05       0  4868.5    .033       0
  4874.5     .05       0  6385.6     .16       0
#XS Ineff= 2 , 0
                         6108.52          322.77
Permanent Ineff=
       F       F
Bank Sta=4851.5,5203.7
XS Rating Curve= 0 ,0
Exp/Cntr=0.3,0.1

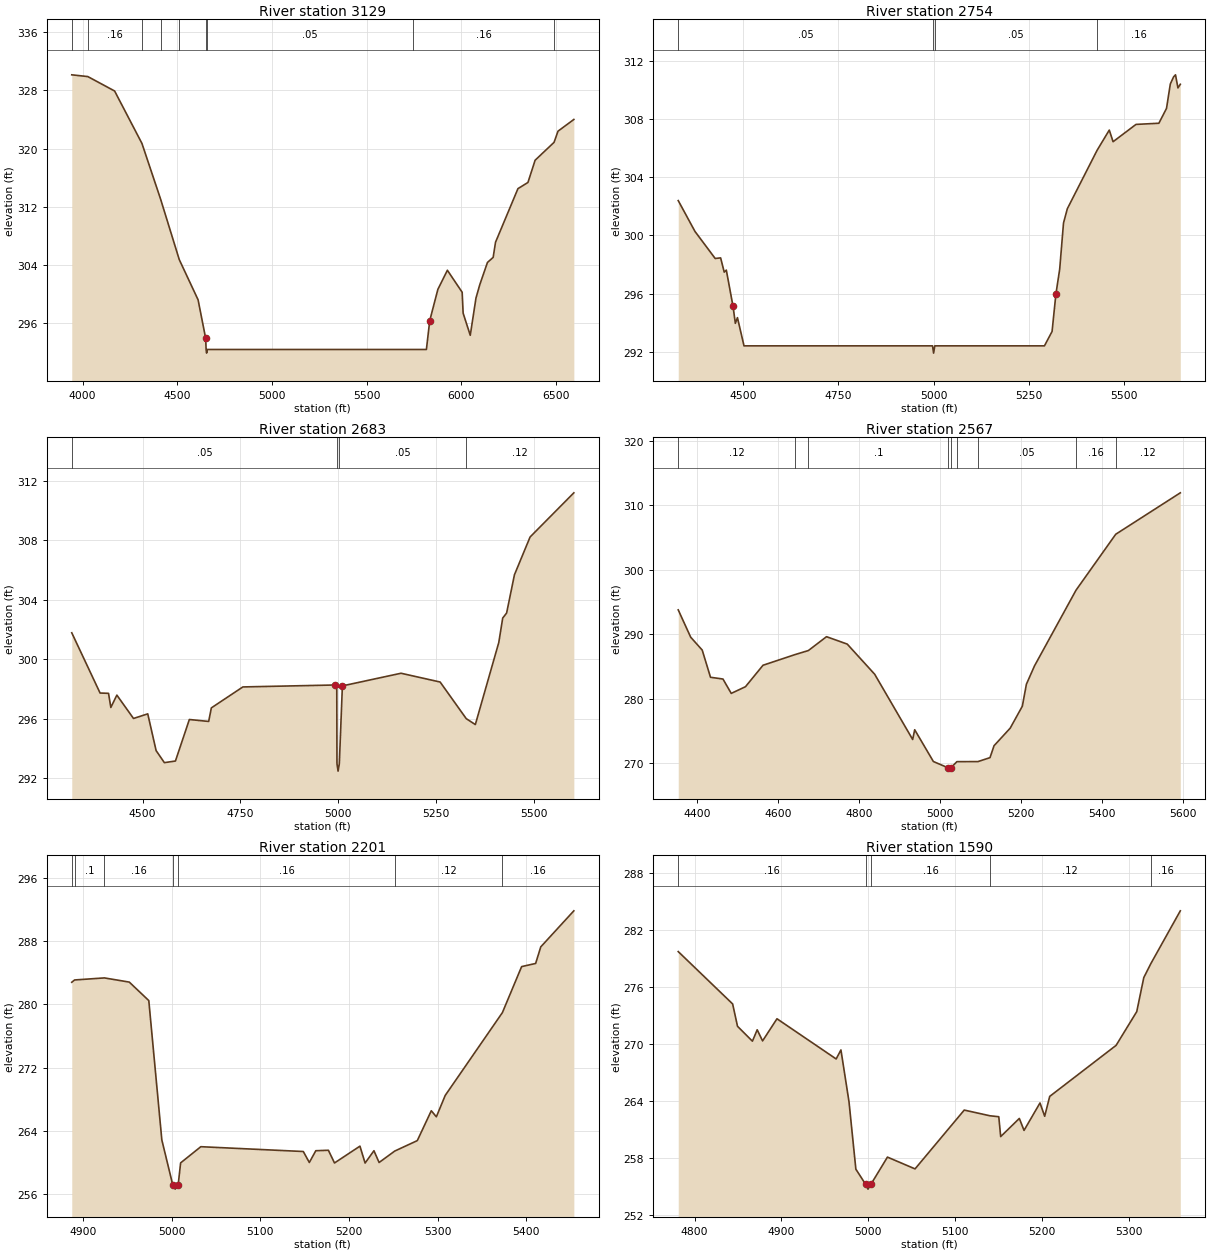
Type RM Length L Ch R = 1 ,3129    ,375,375,375
BEGIN DESCRIPTION:
UNT 03399 IN LACR 6.0
END DESCRIPTION:
XS GIS Cut Line= 3
      3693710.16     10642014.47      3693786.55     10643236.67
      3693953.22     10644653.31
#Sta/Elev= 30
  3942.9  330.13  4027.6  329.89  4169.1  327.91  4313.4  320.71  4411.9  313.06
  4510.4  304.76  4609.9  299.23    4650  293.93  4652.2  292.41  4654.9  291.91
  4658.2  292.41  5743.2  292.41  5815.4  292.41    5833  296.37  5875.9  300.66
  5926.2  303.29  6004.2  300.27  6009.3   297.4    6047  294.36  6077.2  299.48
  6097.4  301.32  6137.7  304.36  6167.9  305.06  6180.4  307.14  6298.8   314.5
  6351.6  315.35  6389.4   318.4  6489.5  320.86  6510.2  322.39  6593.9     324
#Mann= 9 ,-1 , 0
  3942.9     .12       0  4027.6     .16       0  4313.4     .12       0
  4411.9     .16       0  4510.4     .05       0  4652.2    .033       0
  4658.2     .05       0  5743.2     .16       0  6489.5     .05       0
Bank Sta=4650,5833
XS Rating Curve= 0 ,0
Exp/Cntr=0.3,0.1

Type RM Length L Ch R = 1 ,2754    ,71,71,71
BEGIN DESCRIPTION:
Mapping XS 54f3b439
END DESCRIPTION:
XS GIS Cut Line= 6
      3693682.78     10642617.65      3693578.62     10642847.67
       3693522.2     10642927.97      3693450.58     10643010.43
      3693439.73     10643134.13       3693454.9     10643866.41
#Sta/Elev= 30
  4330.1   302.4    4374  300.28    4427  298.42  4441.3  298.46  4450.7  297.48
  4456.2  297.62  4473.8  295.13  4479.9  293.96  4485.4  294.35  4502.6  292.41
    4997  292.41  4999.8  291.91    5003  292.41  5290.5  292.41  5310.5   293.4
  5320.5  295.96  5330.5  297.69  5340.5  300.86  5350.5  301.84  5428.4  305.85
  5460.5  307.25  5470.5  306.45  5530.6  307.64  5590.6  307.72  5610.6  308.74
  5620.6  310.42  5629.2  310.91  5634.2  311.05  5640.6  310.15  5646.8   310.4
#Mann= 4 ,-1 , 0
  4330.1     .05       0    4997    .033       0    5003     .05       0
  5428.4     .16       0
Bank Sta=4473.8,5320.5
XS Rating Curve= 0 ,0
Exp/Cntr=0.3,0.1

Type RM Length L Ch R = 1 ,2683    ,116,116,116
BEGIN DESCRIPTION:
Mapping XS 927eb078
END DESCRIPTION:
XS GIS Cut Line= 6
      3693645.91     10642628.47      3693552.58      10642780.4
      3693415.86      10642925.8      3693370.29      10643027.8
      3693370.29      10643216.6      3693368.12     10643822.09
#Sta/Elev= 30
  4318.8  301.77  4391.2  297.72  4412.8   297.7  4418.7  296.75  4434.1  297.58
  4476.7  296.01  4513.1  296.32  4534.5  293.85  4555.6  293.04  4583.9  293.15
  4619.5  295.94  4668.9  295.81  4675.7  296.72  4756.3  298.13  4990.8  298.26
  4996.5  297.96    4997  292.97  4999.8  292.47    5003  292.97  5010.8   298.2
  5160.8  299.05  5260.8  298.46  5327.5     296  5350.8   295.6  5410.8  301.12
  5420.8  302.76  5430.8   303.1  5450.8  305.67  5490.8  308.21  5602.7  311.18
#Mann= 4 ,-1 , 0
  4318.8     .05       0    4997    .035       0    5003     .05       0
  5327.5     .12       0
Bank Sta=4990.8,5010.8
XS Rating Curve= 0 ,0
Exp/Cntr=0.3,0.1

Type RM Length L Ch R = 1 ,2567    ,366,366,366
BEGIN DESCRIPTION:
UNT 03399 IN LACR 5.0
END DESCRIPTION:
XS GIS Cut Line= 3
      3693370.68     10642572.27      3693253.49     10643097.49
      3693270.85     10643800.64
#Sta/Elev= 30
  4352.7  293.76  4383.5  289.52    4412  287.52  4432.5   283.3  4463.3  283.03
  4483.8   280.8    4519  281.84  4562.4  285.17  4640.9  286.81  4674.5  287.45
  4719.4   289.6  4770.6  288.45  4838.5  283.77  4932.4  273.65  4937.4  275.16
  4983.6  270.23  5020.6  269.24  5023.3  268.74  5026.6  269.24  5041.8  270.21
  5093.8  270.22  5123.6  270.83  5133.6  272.68  5173.6  275.41  5203.6  278.82
  5213.6  282.22  5233.6  285.06  5336.3  296.81  5434.5  305.49  5594.2  311.92
#Mann= 9 ,-1 , 0
  4352.7     .12       0  4640.9     .05       0  4674.5      .1       0
  5020.6     .07       0  5026.6      .1       0  5041.8     .16       0
  5093.8     .05       0  5336.3     .16       0  5434.5     .12       0
Bank Sta=5020.6,5026.6
XS Rating Curve= 0 ,0
Exp/Cntr=0.3,0.1

Type RM Length L Ch R = 1 ,2201    ,611,611,611
BEGIN DESCRIPTION:
UNT 03399 IN LACR 4.0
END DESCRIPTION:
XS GIS Cut Line= 4
      3693233.56     10642853.41      3693047.78     10642968.01
       3692976.6     10643044.39      3692854.76     10643255.46
#Sta/Elev= 30
  4887.3  282.81  4890.5   283.1  4924.1  283.36  4952.2  282.83  4974.2  280.49
  4988.9  262.86  5001.3  257.13    5004  256.63  5007.3  257.13  5010.1  259.95
  5032.9     262  5148.5  261.39  5155.3     260  5162.6  261.49  5176.8  261.55
  5183.7  259.94  5212.4  262.07  5218.2  259.93  5228.2  261.49    5234     260
  5251.7  261.45  5277.1  262.77  5292.9  266.55  5298.6  265.78  5308.6  268.49
  5373.1  278.97  5394.8  284.79  5410.6  285.19  5416.4  287.29  5453.7  291.85
#Mann= 7 ,-1 , 0
  4887.3     .12       0  4890.5      .1       0  4924.1     .16       0
  5001.3     .07       0  5007.3     .16       0  5251.7     .12       0
  5373.1     .16       0
Bank Sta=5001.3,5007.3
XS Rating Curve= 0 ,0
Exp/Cntr=0.3,0.1

Type RM Length L Ch R = 1 ,1590    ,526,526,526
BEGIN DESCRIPTION:
UNT 03399 IN LACR 3.0
END DESCRIPTION:
XS GIS Cut Line= 3
      3693247.45     10642596.47      3692910.62      10642756.2
      3692720.73     10642835.61
#Sta/Elev= 30
  4781.1  279.73  4843.8  274.22  4849.4  271.87  4866.6   270.3  4872.1   271.5
  4878.3  270.33  4894.9  272.66  4963.1  268.43  4968.6  269.38  4977.9  263.92
  4985.8  256.83  4997.1  255.23  4999.8  254.73  5003.1  255.23  5022.2   258.1
    5054  256.86  5110.7  263.05  5140.3  262.45  5150.5  262.35  5152.7  260.26
  5174.2  262.17  5179.6  260.91    5198   263.8  5203.4   262.4  5209.2  264.49
  5285.7  269.86  5309.5  273.41  5317.6  276.99  5325.6  278.44  5359.7  284.02
#Mann= 5 ,-1 , 0
  4781.1     .16       0  4997.1     .07       0  5003.1     .16       0
  5140.3     .12       0  5325.6     .16       0
Bank Sta=4997.1,5003.1
XS Rating Curve= 0 ,0
Exp/Cntr=0.3,0.1

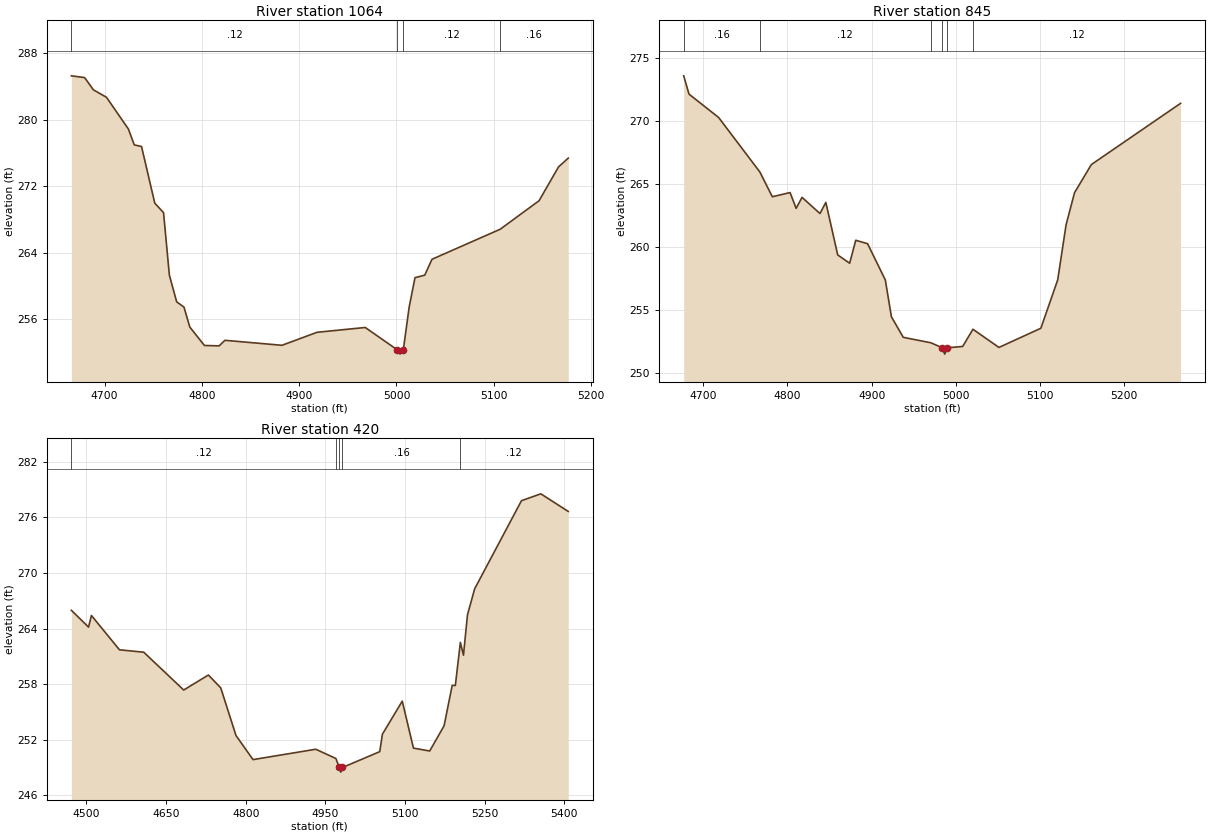
Type RM Length L Ch R = 1 ,1064    ,219,219,219
BEGIN DESCRIPTION:
UNT 03399 IN LACR 2.0
END DESCRIPTION:
XS GIS Cut Line= 3
      3692999.64     10642260.17      3692699.61     10642460.19
      3692699.61      10642610.2
#Sta/Elev= 30
  4665.9  285.25  4679.5  285.04  4688.5  283.57    4702  282.67  4724.5  278.86
  4730.5  276.96    4738  276.76  4751.6  269.96  4760.6  268.82  4766.6  261.32
  4774.1  258.11  4781.6  257.48  4787.6  255.08  4802.6  252.87  4817.7  252.82
  4823.7  253.49  4882.3  252.89  4918.3  254.45  4967.9  255.03    5001  252.33
  5003.7  251.83    5007  252.33    5013  257.46    5019  261.01    5029  261.31
  5036.5  263.22  5106.6  266.83  5146.5  270.25  5166.5  274.31  5176.5  275.37
#Mann= 4 ,-1 , 0
  4665.9     .12       0    5001     .07       0    5007     .12       0
  5106.6     .16       0
Bank Sta=5001,5007
XS Rating Curve= 0 ,0
Exp/Cntr=0.3,0.1

Type RM Length L Ch R = 1 ,845     ,425,425,425
BEGIN DESCRIPTION:
Mapping XS 1cc97f39
END DESCRIPTION:
XS GIS Cut Line= 3
      3692877.91     10642059.67      3692610.96     10642315.77
      3692606.64      10642536.2
#Sta/Elev= 30
  4676.7  273.58    4683  272.13  4718.2  270.28  4767.2  265.96    4782     264
  4803.1  264.33  4810.3  263.08  4817.3  263.95  4838.6  262.67  4845.6  263.55
  4859.7  259.39  4873.9  258.73  4881.1  260.55  4895.2  260.28  4916.3   257.4
  4923.5  254.49  4937.6  252.86  4970.4  252.43  4984.1  252.03  4986.8  251.53
  4990.1  252.03  5008.2  252.14  5020.4   253.5  5051.3  252.06  5101.1  253.58
  5121.1  257.41  5131.1  261.79  5141.1  264.32  5161.1  266.55  5267.1   271.4
#Mann= 6 ,-1 , 0
  4676.7     .16       0  4767.2     .12       0  4970.4     .16       0
  4984.1     .07       0  4990.1     .16       0  5020.4     .12       0
Bank Sta=4984.1,4990.1
XS Rating Curve= 0 ,0
Exp/Cntr=0.3,0.1

Type RM Length L Ch R = 1 ,420     ,0,0,0
BEGIN DESCRIPTION:
UNT 03399 IN LACR 1.0
END DESCRIPTION:
XS GIS Cut Line= 4
      3692782.38     10641901.28      3692396.12     10642072.71
      3692374.42     10642235.47      3692561.05     10642530.62
#Sta/Elev= 30
  4471.6  265.97  4503.9  264.16  4509.4  265.41  4562.2  261.71  4607.9  261.45
  4683.2  257.37  4729.7  258.99    4753   257.6  4781.7  252.46  4813.8  249.86
    4932  250.98  4969.9  249.98  4976.3  249.01  4979.1  248.51  4982.3  249.01
  5052.5  250.72  5057.5   252.6  5094.9  256.17    5116   251.1  5146.6  250.79
  5173.7  253.51    5189  257.87  5194.9  257.86  5204.4  262.51  5210.2  261.13
  5217.8  265.49  5231.3  268.29  5319.5   277.8    5356  278.54  5407.6  276.64
#Mann= 5 ,-1 , 0
  4471.6     .12       0  4969.9     .16       0  4976.3     .07       0
  4982.3     .16       0  5204.4     .12       0
Bank Sta=4976.3,4982.3
XS Rating Curve= 0 ,0
Exp/Cntr=0.3,0.1

Chan Stop Cuts=-1
Use User Specified Reach Order=0
Composite Channel Slope=5