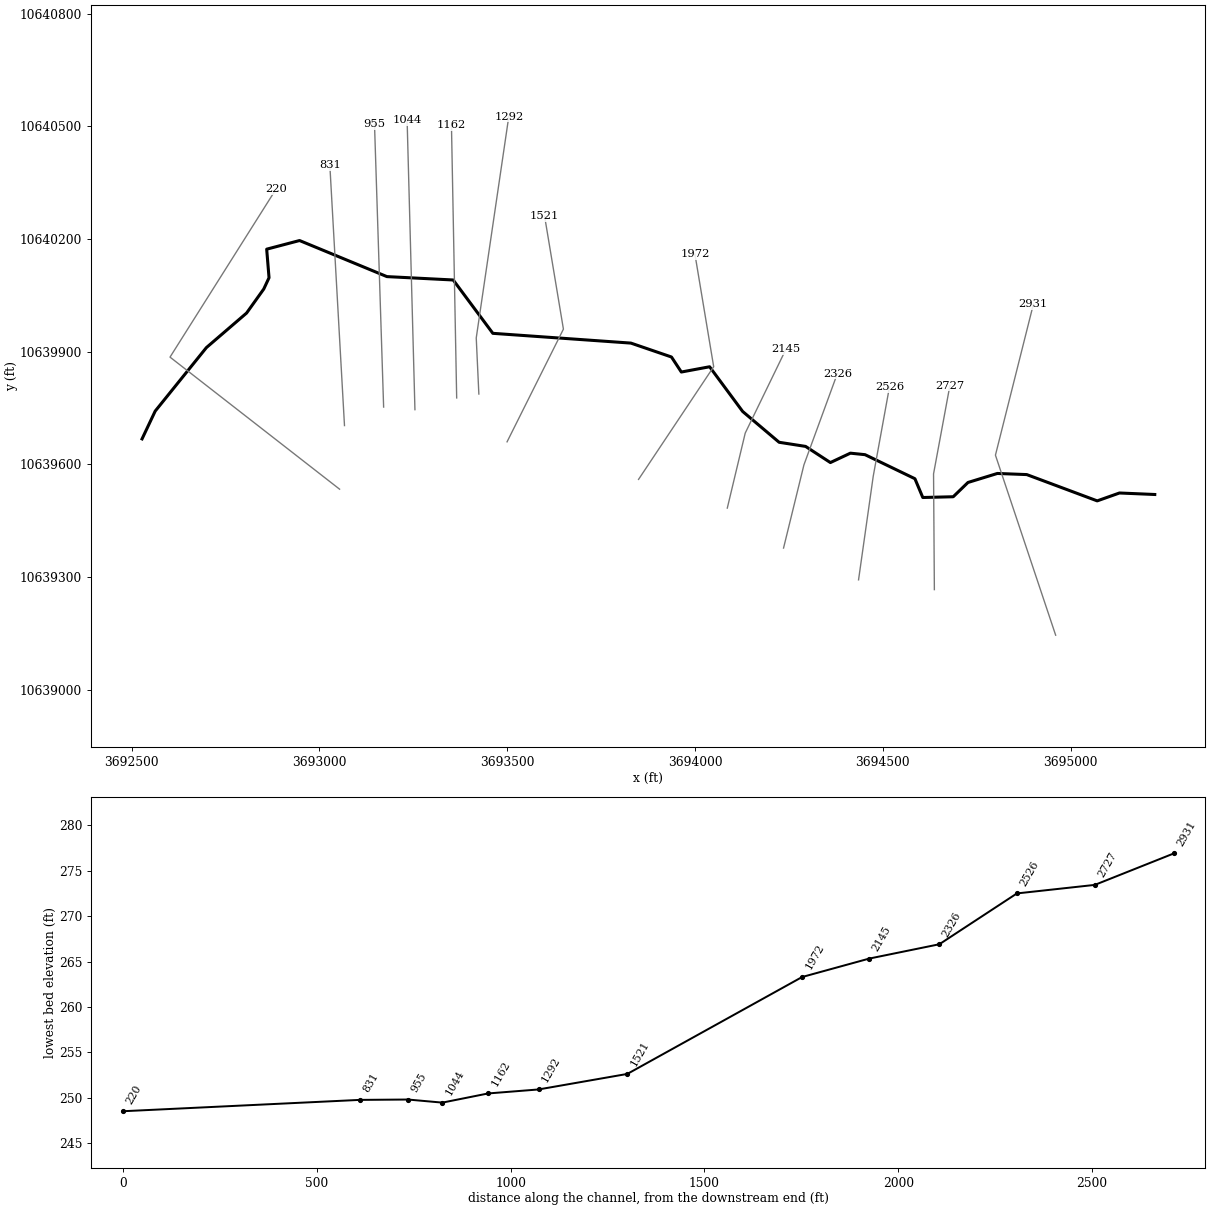
--- UNT 03402 IN LACR.prj (project) ---

Proj Title=UNT 03402 IN LACR Base Level Engineering
Current Plan=p01
Default Exp/Contr=0.3,0.1
English Units
Geom File=g01
Flow File=f01
Plan File=p01
Y Axis Title=Elevation
X Axis Title(PF)=Main Channel Distance
X Axis Title(XS)=Station
BEGIN DESCRIPTION:
UNT 03402 IN LACR
END DESCRIPTION:
DSS Export Rating Curves= 0
DSS Export Rating Curve Sorted= 0
DSS Export Volume Flow Curves= 0
DXF OffsetX= 0
DXF OffsetY= 0
DXF ScaleX= 1
DXF ScaleY= 10

--- UNT 03402 IN LACR.p01 (plan) ---

Plan Title=Multiple Run
Short Identifier=Multiple
Geom File=g01
Flow File=f01
Subcritical Flow
K Sum by GR= 0
Std Step Tol= 0.01
Critical Tol= 0.01
Num of Std Step Trials= 20
Max Error Tol= 0.3
Flow Tol Ratio= 0.001
Split Flow NTrial= 30
Split Flow Tol= 0.02
Split Flow Ratio= 0.02
Log Output Level= 0
Friction Slope Method= 1
Unsteady Friction Slope Method= 2
Unsteady Bridges Friction Slope Method= 1
Parabolic Critical Depth
Global Vel Dist=  1 , 1 , 1
Global Log Level= 0
CheckData=True
Encroach Param= -1, 0, 0, 0
BEGIN DESCRIPTION:
Multiple Run
END DESCRIPTION:

--- UNT 03402 IN LACR.f01 (steady flow) ---

Flow Title=Multiple
Program Version=4.10
Number of Profiles= 7
Profile Names=10-year,25-year,50-year,1pct_min,100-year,1pct_plu,500-year
River Rch & RM=UNT 03402 IN LAC,Reach-1         ,2931
     266     345     407     356     481     650     671
Boundary for River Rch & Prof#=UNT 03402 IN LAC,Reach-1         , 1
Up Type= 0
Dn Type= 3
Dn Slope=0.002
Boundary for River Rch & Prof#=UNT 03402 IN LAC,Reach-1         , 2
Up Type= 0
Dn Type= 3
Dn Slope=0.002
Boundary for River Rch & Prof#=UNT 03402 IN LAC,Reach-1         , 3
Up Type= 0
Dn Type= 3
Dn Slope=0.002
Boundary for River Rch & Prof#=UNT 03402 IN LAC,Reach-1         , 4
Up Type= 0
Dn Type= 3
Dn Slope=0.002
Boundary for River Rch & Prof#=UNT 03402 IN LAC,Reach-1         , 5
Up Type= 0
Dn Type= 3
Dn Slope=0.002
Boundary for River Rch & Prof#=UNT 03402 IN LAC,Reach-1         , 6
Up Type= 0
Dn Type= 3
Dn Slope=0.002
Boundary for River Rch & Prof#=UNT 03402 IN LAC,Reach-1         , 7
Up Type= 0
Dn Type= 3
Dn Slope=0.002
DSS Import GetInterval= 0
DSS Import GetPeak= 0
DSS Import FillOption= 0

--- UNT 03402 IN LACR.g01 (geometry) ---

Geom Title=Existing Conditions
Program Version=4.10

River Reach=UNT 03402 IN LAC,Reach-1
Reach XY= 30
      3695223.75       10639520.      3695129.75       10639524.
       3695070.5       10639503.        3694883.       10639573.
      3694804.75       10639576.       3694726.5       10639552.
      3694687.25       10639514.      3694606.25       10639512.
      3694585.25       10639562.       3694452.5       10639626.
       3694413.5       10639630.      3694360.25       10639605.
      3694294.25       10639648.      3694223.75       10639659.
      3694126.75       10639741.      3694038.75       10639860.
       3693963.5       10639846.      3693937.25       10639886.
      3693829.25       10639923.      3693461.75       10639949.
      3693356.25       10640091.      3693179.75       10640100.
      3692947.25       10640196.      3692859.75       10640173.
        3692866.       10640097.        3692852.       10640067.
      3692806.25       10640003.      3692699.25       10639911.
        3692563.       10639742.        3692528.       10639668.

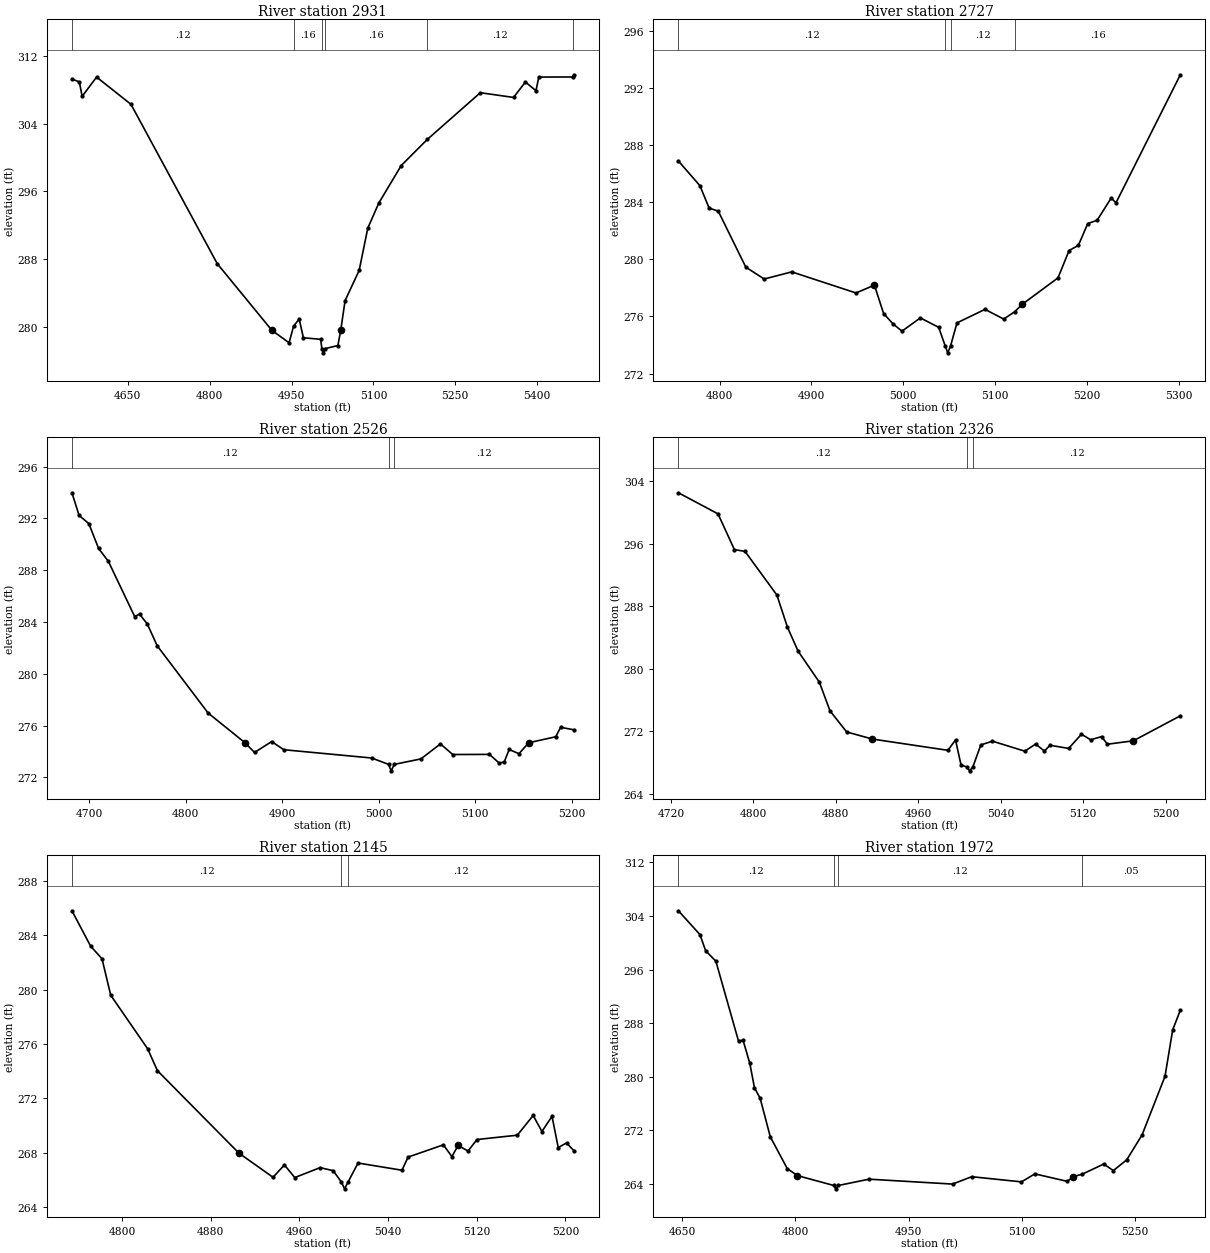
Type RM Length L Ch R = 1 ,2931    ,204,204,204
BEGIN DESCRIPTION:
UNT 03402 IN LACR 6.0
END DESCRIPTION:
XS GIS Cut Line= 3
      3694959.91     10639145.49      3694799.61     10639624.69
      3694900.58     10640026.29
#Sta/Elev= 30
  4547.8  309.29  4561.3  308.96  4566.5  307.25  4592.9  309.53    4656   306.3
  4813.9  287.47  4913.9  279.59  4945.5  278.11  4953.8  280.07    4964  280.92
  4971.8   278.7  5003.4  278.52  5005.6  277.42  5008.4  276.92  5011.6  277.42
  5034.9  277.78  5040.2  279.59  5048.1  283.09  5073.9  286.66  5089.7  291.66
  5109.9  294.63    5151  299.07  5198.8  302.16  5295.9  307.68  5356.7  307.12
  5378.4  308.94  5397.8  307.92    5403  309.53  5465.2  309.54  5467.2   309.8
#Mann= 6 ,-1 , 0
  4547.8     .12       0  4953.8     .16       0  5005.6     .07       0
  5011.6     .16       0  5198.8     .12       0  5465.2     .05       0
Bank Sta=4913.9,5040.2
XS Rating Curve= 0 ,0
Exp/Cntr=0.3,0.1

Type RM Length L Ch R = 1 ,2727    ,201,201,201
BEGIN DESCRIPTION:
Mapping XS 7f84d515
END DESCRIPTION:
XS GIS Cut Line= 3
      3694637.04     10639266.78      3694634.87     10639574.94
      3694678.27     10639809.29
#Sta/Elev= 30
  4755.2  286.91  4778.6  285.18  4788.6  283.61  4798.6  283.39  4828.6  279.46
  4848.6  278.63  4878.6  279.13  4948.6  277.65  4968.6   278.2  4978.6  276.21
  4988.6   275.5  4998.6  274.97  5018.6   275.9  5038.6  275.24  5045.6  273.95
  5048.4  273.45  5051.6  273.95  5058.5  275.55    5089   276.5  5109.4  275.82
  5121.3  276.33  5129.7  276.86  5168.5  278.71  5180.6  280.63  5190.7  280.99
  5200.9  282.52  5211.1  282.75  5226.5  284.32  5231.6  283.97  5301.7  292.96
#Mann= 4 ,-1 , 0
  4755.2     .12       0  5045.6     .07       0  5051.6     .12       0
  5121.3     .16       0
Bank Sta=4968.6,5129.7
XS Rating Curve= 0 ,0
Exp/Cntr=0.3,0.1

Type RM Length L Ch R = 1 ,2526    ,200,200,200
BEGIN DESCRIPTION:
Mapping XS 03b3cf4a
END DESCRIPTION:
XS GIS Cut Line= 3
      3694435.22     10639292.81      3694474.28     10639568.43
      3694517.51     10639806.16
#Sta/Elev= 30
  4682.3  293.98  4689.7  292.23  4699.8   291.6  4709.9  289.68    4720  288.69
  4747.3  284.42  4752.3  284.61  4760.4  283.85  4770.5  282.18  4823.3  276.98
  4861.4  274.69  4871.5  273.93  4889.2  274.77  4901.8  274.14  4992.9   273.5
  5010.3  273.01    5013  272.51  5016.3  273.01  5043.8  273.43  5064.1  274.59
  5076.8  273.77  5114.9  273.78  5125.1   273.1  5130.2  273.21  5135.3  274.16
  5145.4  273.83  5155.6  274.68  5183.5  275.14  5188.6  275.87  5202.3  275.68
#Mann= 3 ,-1 , 0
  4682.3     .12       0  5010.3     .07       0  5016.3     .12       0
Bank Sta=4861.4,5155.6
XS Rating Curve= 0 ,0
Exp/Cntr=0.3,0.1

Type RM Length L Ch R = 1 ,2326    ,181,181,181
BEGIN DESCRIPTION:
UNT 03402 IN LACR 5.0
END DESCRIPTION:
XS GIS Cut Line= 3
      3694235.56     10639377.44      3694289.82     10639598.81
      3694378.81     10639841.91
#Sta/Elev= 30
  4727.3  302.53  4765.7  299.83  4781.6  295.25  4791.9  295.02  4822.8  289.43
  4833.1  285.29  4843.4  282.24    4864  278.27  4874.3   274.6  4890.5  271.89
  4915.5  270.98  4988.6  269.54  4996.1  270.86  5001.4  267.66  5006.9  267.41
  5009.7  266.91  5012.9  267.41  5020.6  270.23  5031.9  270.71  5063.2  269.43
  5073.8  270.34  5082.3  269.44  5087.7  270.19  5105.8  269.78  5118.2   271.6
  5127.1  270.89  5137.7  271.29  5143.4  270.32  5168.6  270.76  5214.1  273.96
#Mann= 3 ,-1 , 0
  4727.3     .12       0  5006.9     .07       0  5012.9     .12       0
Bank Sta=4915.5,5168.6
XS Rating Curve= 0 ,0
Exp/Cntr=0.3,0.1

Type RM Length L Ch R = 1 ,2145    ,173,173,173
BEGIN DESCRIPTION:
Mapping XS c8abaa06
END DESCRIPTION:
XS GIS Cut Line= 3
      3694085.83     10639483.79      3694133.57     10639683.45
      3694241.66     10639906.11
#Sta/Elev= 30
  4754.9   285.8  4771.8  283.19    4782  282.27  4789.9  279.58  4823.2  275.64
    4832  274.03  4905.4  267.97  4936.3  266.18  4946.6  267.09  4955.9  266.16
  4978.8  266.89  4990.5  266.67    4998  265.83  5000.8  265.33    5004  265.83
    5013  267.23  5052.6   266.7  5058.2  267.67    5090  268.57  5097.7   267.7
  5103.3  268.53  5112.2  268.11  5120.3  268.96  5156.7  269.28    5171  270.73
  5178.9  269.55    5188  270.67  5193.6  268.37  5201.1  268.71  5207.7  268.14
#Mann= 3 ,-1 , 0
  4754.9     .12       0    4998     .07       0    5004     .12       0
Bank Sta=4905.4,5103.3
XS Rating Curve= 0 ,0
Exp/Cntr=0.3,0.1

Type RM Length L Ch R = 1 ,1972    ,451,451,451
BEGIN DESCRIPTION:
UNT 03402 IN LACR 4.0
END DESCRIPTION:
XS GIS Cut Line= 3
      3693849.61     10639560.19      3694049.61     10639860.19
      3693999.61      10640160.2
#Sta/Elev= 30
  4645.2  304.76  4673.7  301.21  4681.3  298.79  4694.8  297.24  4724.8  285.33
  4730.8  285.46  4739.8     282  4745.9  278.37  4753.4  276.82  4766.9  271.05
  4789.4  266.31  4802.9  265.27    4851   263.8  4853.8   263.3    4857   263.8
  4897.6  264.74  5008.3  264.01  5033.6  265.11  5099.5  264.34  5117.3  265.53
  5160.4  264.41    5168  265.13  5179.3  265.45  5208.5     267  5221.2  266.02
  5238.9  267.62  5259.2  271.33  5289.6  280.07  5299.8     287  5309.9  289.93
#Mann= 4 ,-1 , 0
  4645.2     .12       0    4851     .07       0    4857     .12       0
  5179.3     .05       0
Bank Sta=4802.9,5168
XS Rating Curve= 0 ,0
Exp/Cntr=0.3,0.1

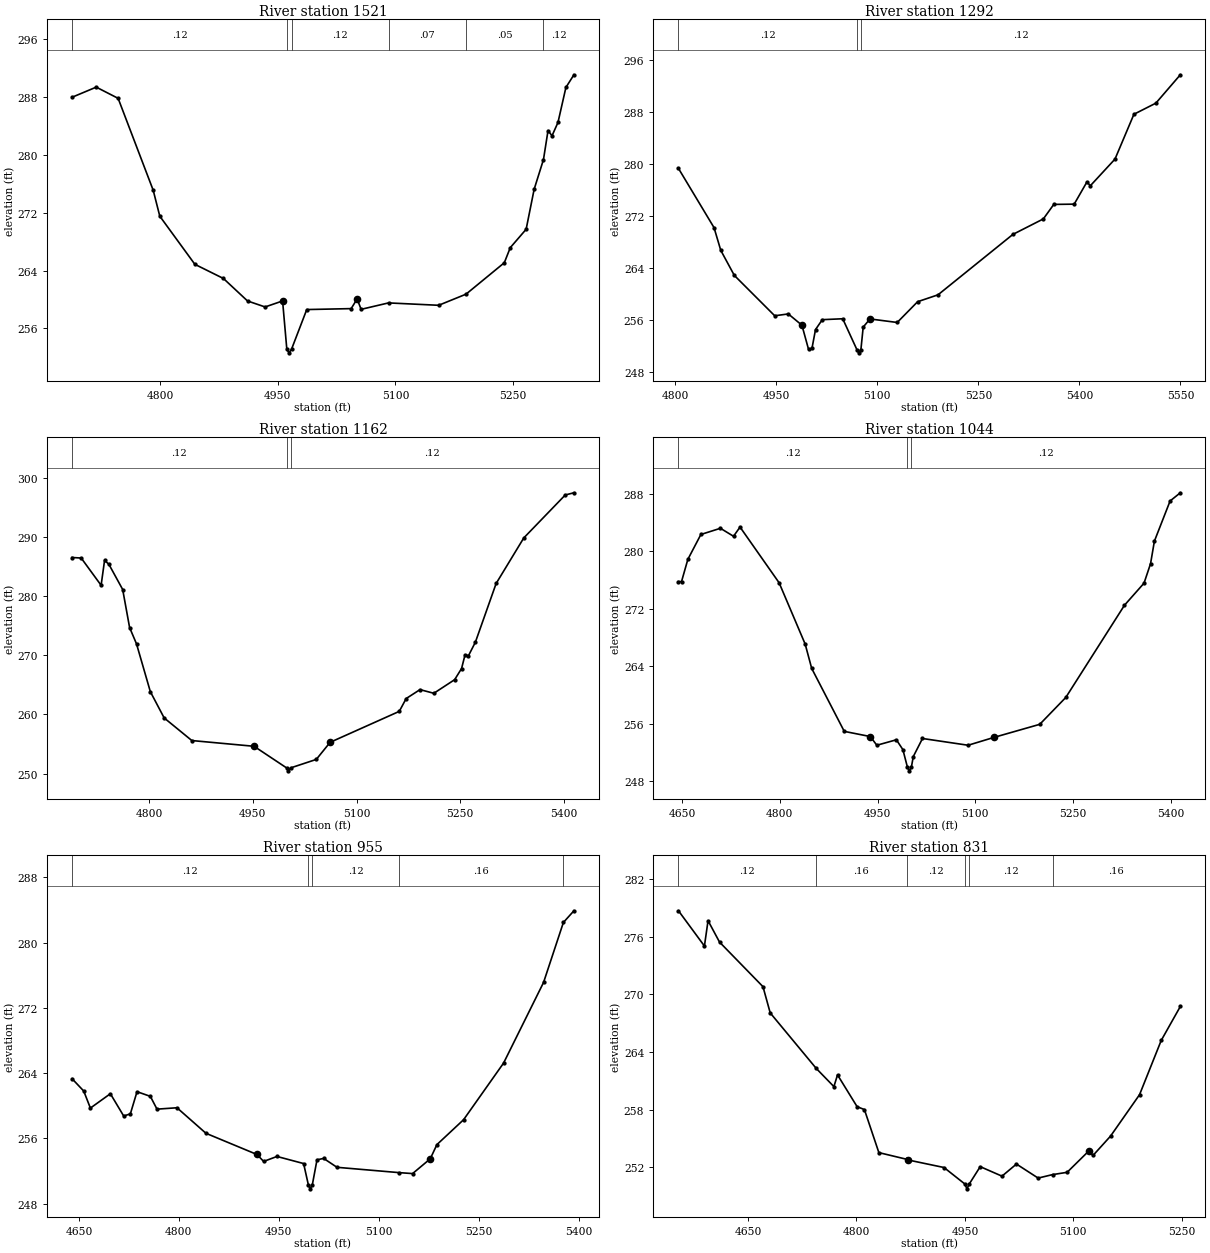
Type RM Length L Ch R = 1 ,1521    ,229,229,229
BEGIN DESCRIPTION:
UNT 03402 IN LACR 3.0
END DESCRIPTION:
XS GIS Cut Line= 3
       3693499.6     10639660.18      3693649.61     10639960.19
       3693599.6     10640260.22
#Sta/Elev= 30
  4687.9  287.99  4718.7  289.39  4746.6  287.84  4791.3  275.12  4799.7  271.53
  4844.4  264.87  4880.8  262.91  4911.5   259.8  4933.9  258.97  4956.2   259.8
  4961.6  253.12  4964.4  252.62  4967.6  253.12    4987  258.61  5043.6  258.74
  5051.2  260.08  5056.3  258.64  5091.2  259.53  5155.1   259.2    5190  260.74
  5238.8  265.09  5246.4  267.18  5266.6  269.72  5276.8  275.25  5288.7  279.37
  5294.5  283.38  5299.6  282.66  5307.2  284.51  5317.3  289.35  5327.5   291.1
#Mann= 6 ,-1 , 0
  4687.9     .12       0  4961.6     .07       0  4967.6     .12       0
  5091.2     .07       0    5190     .05       0  5288.7     .12       0
Bank Sta=4956.2,5051.2
XS Rating Curve= 0 ,0
Exp/Cntr=0.3,0.1

Type RM Length L Ch R = 1 ,1292    ,130,130,130
BEGIN DESCRIPTION:
Mapping XS 76135234
END DESCRIPTION:
XS GIS Cut Line= 3
      3693424.52     10639787.41      3693417.57     10639936.76
      3693504.24     10640526.11
#Sta/Elev= 30
  4804.7  279.26  4857.5  270.16  4867.5  266.67  4887.6  262.82  4947.6  256.61
  4967.8  256.89    4988  255.16  4997.8  251.46  5002.9  251.58  5008.2  254.49
  5018.3  256.01  5048.6  256.15  5069.6  251.41  5072.4  250.91  5075.6  251.41
    5079  254.87  5089.1  256.12  5129.5  255.58  5159.8  258.77  5190.1  259.83
  5301.3  269.12  5346.5   271.5    5362  273.73  5392.3  273.77  5411.2  277.18
  5416.3   276.6  5452.9   280.7    5481  287.59  5513.6   289.3  5549.9  293.66
#Mann= 3 ,-1 , 0
  4804.7     .12       0  5069.6     .07       0  5075.6     .12       0
Bank Sta=4988,5089.1
XS Rating Curve= 0 ,0
Exp/Cntr=0.3,0.1

Type RM Length L Ch R = 1 ,1162    ,118,118,118
BEGIN DESCRIPTION:
Mapping XS 83067971
END DESCRIPTION:
XS GIS Cut Line= 2
      3693365.49     10639777.04       3693351.6      10640502.7
#Sta/Elev= 30
  4688.6  286.53  4701.8  286.44  4730.6  281.83  4735.6  286.04  4741.8  285.39
  4761.8  281.12  4771.8  274.69  4781.8  271.93  4801.8  263.85  4821.8  259.41
  4861.8  255.59  4951.8  254.62  4998.8  250.97  5001.6  250.47  5004.8  250.97
  5041.8   252.4  5061.8  255.29  5161.8  260.52  5171.8  262.69  5191.8   264.2
  5211.8  263.58  5241.9  265.88  5251.9  267.76  5256.9  270.06  5261.9  269.93
  5271.9  272.22  5301.9  282.14  5341.9  289.84  5401.9   297.1  5414.4  297.47
#Mann= 3 ,-1 , 0
  4688.6     .12       0  4998.8     .07       0  5004.8     .12       0
Bank Sta=4951.8,5061.8
XS Rating Curve= 0 ,0
Exp/Cntr=0.3,0.1

Type RM Length L Ch R = 1 ,1044    ,89,89,89
BEGIN DESCRIPTION:
UNT 03402 IN LACR 2.0
END DESCRIPTION:
XS GIS Cut Line= 2
      3693254.38     10639745.77      3693233.56     10640515.89
#Sta/Elev= 30
  4644.4  275.79  4649.1  275.79  4658.8  278.88  4678.8  282.34  4708.8   283.2
  4728.9  282.09  4738.9  283.37  4798.9  275.62  4838.9  267.09  4848.9  263.71
  4898.9  254.95  4938.9  254.23  4948.9  253.02  4978.9  253.78  4988.9  252.41
  4995.9  249.96  4998.7  249.46  5001.9  249.96  5004.9  251.45    5019  253.96
    5089  253.02    5129  254.12    5199  255.93    5239  259.67  5329.1   272.5
  5359.1  275.57  5369.1  278.28    5375  281.41  5399.1     287  5414.8  288.14
#Mann= 3 ,-1 , 0
  4644.4     .12       0  4995.9     .07       0  5001.9     .12       0
Bank Sta=4938.9,5129
XS Rating Curve= 0 ,0
Exp/Cntr=0.3,0.1

Type RM Length L Ch R = 1 ,955     ,124,124,124
BEGIN DESCRIPTION:
Mapping XS b26047d0
END DESCRIPTION:
XS GIS Cut Line= 2
      3693171.04     10639752.72      3693146.75     10640505.73
#Sta/Elev= 30
  4639.7   263.3  4657.2  261.79  4667.2   259.7  4697.2  261.46  4717.2  258.73
  4727.2  258.99  4737.2  261.71  4757.2  261.14  4767.2  259.57  4797.2  259.74
  4840.7  256.61  4917.3  254.01  4927.3  253.16  4947.3  253.77  4987.3   252.9
  4994.4   250.3  4997.1   249.8  5000.4   250.3  5007.4  253.36  5017.4  253.53
  5037.4  252.44  5130.3  251.79  5150.9  251.67  5177.4  253.48  5187.4  255.22
  5227.5  258.28  5287.5  265.22  5347.5   275.1  5377.3  282.46  5393.1  283.89
#Mann= 5 ,-1 , 0
  4639.7     .12       0  4994.4     .07       0  5000.4     .12       0
  5130.3     .16       0  5377.3     .12       0
Bank Sta=4917.3,5177.4
XS Rating Curve= 0 ,0
Exp/Cntr=0.3,0.1

Type RM Length L Ch R = 1 ,831     ,611,611,611
BEGIN DESCRIPTION:
Mapping XS 8c3f5be1
END DESCRIPTION:
XS GIS Cut Line= 2
      3693066.85     10639703.44      3693027.86     10640396.54
#Sta/Elev= 30
  4553.8   278.7  4589.7  275.03  4594.7  277.67  4610.6  275.44  4670.7   270.8
  4680.7  268.07  4744.4  262.29  4768.8   260.4  4773.8  261.62  4800.9  258.31
    4811  258.01    4831  253.53  4869.3  252.84    4871  252.77  4921.1  251.98
    4950  250.26  4952.8  249.76    4956  250.26  4971.2  252.07  5001.3  251.08
  5021.3  252.34  5051.3  250.88  5071.2  251.24  5091.4  251.48  5121.4   253.7
  5127.2  253.23  5151.5  255.25  5191.6  259.56  5221.6  265.21    5248  268.74
#Mann= 6 ,-1 , 0
  4553.8     .12       0  4744.4     .16       0  4869.3     .12       0
    4950     .07       0    4956     .12       0  5071.2     .16       0
Bank Sta=4871,5121.4
XS Rating Curve= 0 ,0
Exp/Cntr=0.3,0.1

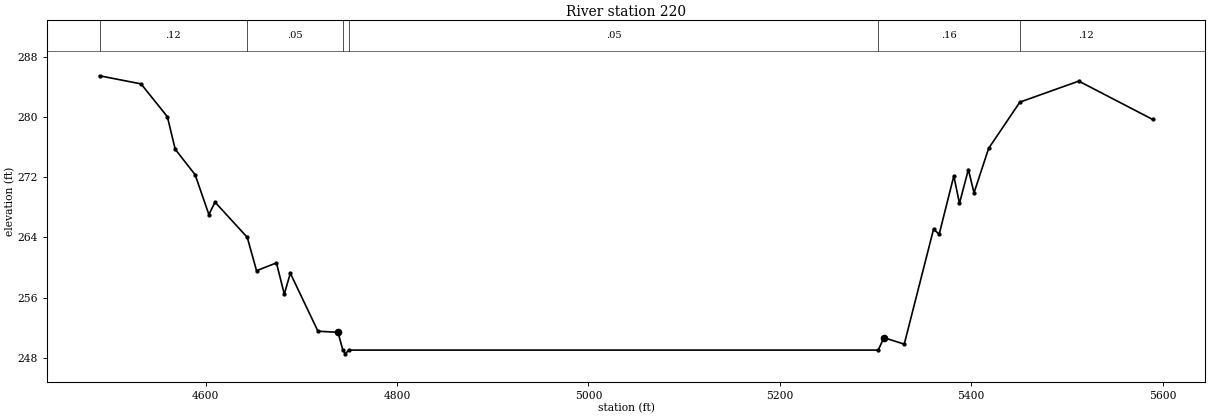
Type RM Length L Ch R = 1 ,220     ,0,0,0
BEGIN DESCRIPTION:
UNT 03402 IN LACR 1.0
END DESCRIPTION:
XS GIS Cut Line= 3
      3693053.81     10639534.14      3692602.44     10639885.68
      3692884.54      10640332.7
#Sta/Elev= 30
  4489.1  285.53  4532.5  284.45    4560  280.08  4568.2  275.75    4589  272.36
  4603.4  267.05  4609.8  268.71  4643.5  264.02  4653.2  259.58    4674  260.62
  4682.2  256.46  4688.5  259.24  4717.4  251.52  4738.3  251.38  4743.4  249.01
  4746.1  248.51  4749.4  249.01  5302.9  249.01  5308.9  250.66  5330.1   249.8
  5360.7   265.1  5366.6  264.44  5381.9  272.19  5387.8  268.54  5397.1  273.05
    5403  269.94  5418.3  275.87  5450.9  282.02  5512.5  284.82  5589.8  279.71
#Mann= 6 ,-1 , 0
  4489.1     .12       0  4643.5     .05       0  4743.4    .033       0
  4749.4     .05       0  5302.9     .16       0  5450.9     .12       0
Bank Sta=4738.3,5308.9
XS Rating Curve= 0 ,0
Exp/Cntr=0.3,0.1

Chan Stop Cuts=-1
Use User Specified Reach Order=0
Composite Channel Slope=5