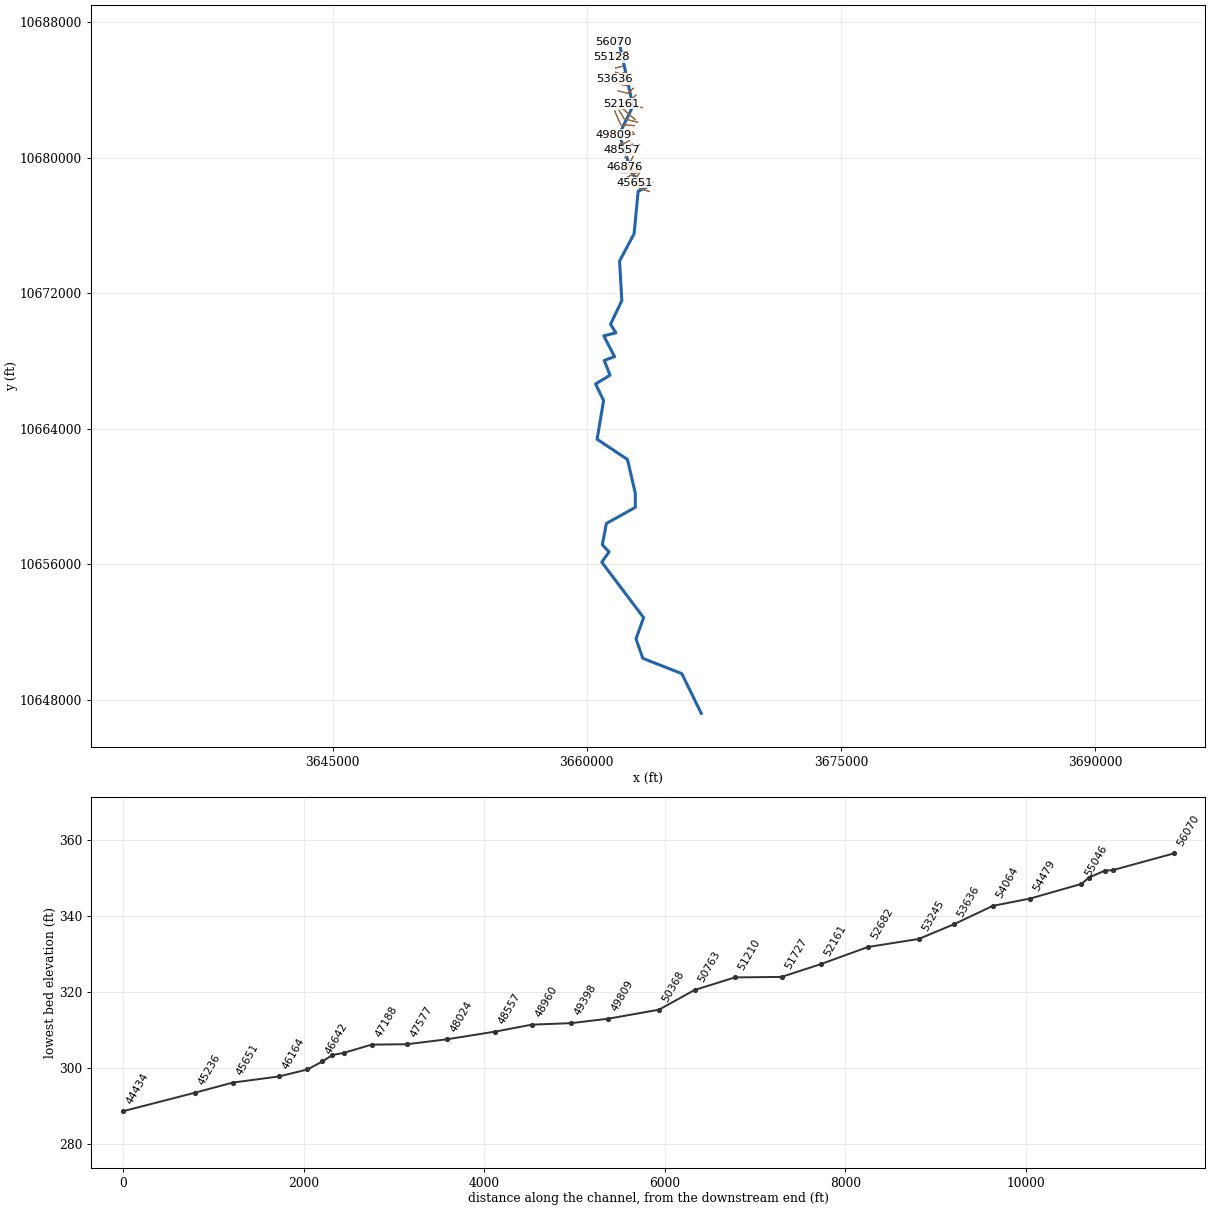
--- UNT 0415 IN LACR.prj (project) ---

Proj Title=UNT 0415 IN LACR Base Level Engineering
Current Plan=p01
Default Exp/Contr=0.3,0.1
English Units
Geom File=g01
Flow File=f01
Plan File=p01
Y Axis Title=Elevation
X Axis Title(PF)=Main Channel Distance
X Axis Title(XS)=Station
BEGIN DESCRIPTION:
UNT 0415 IN LACR
END DESCRIPTION:
DSS Export Rating Curves= 0
DSS Export Rating Curve Sorted= 0
DSS Export Volume Flow Curves= 0
DXF OffsetX= 0
DXF OffsetY= 0
DXF ScaleX= 1
DXF ScaleY= 10

--- UNT 0415 IN LACR.p01 (plan) ---

Plan Title=Multiple Run
Short Identifier=Multiple
Geom File=g01
Flow File=f01
Subcritical Flow
K Sum by GR= 0
Std Step Tol= 0.01
Critical Tol= 0.01
Num of Std Step Trials= 20
Max Error Tol= 0.3
Flow Tol Ratio= 0.001
Split Flow NTrial= 30
Split Flow Tol= 0.02
Split Flow Ratio= 0.02
Log Output Level= 0
Friction Slope Method= 1
Unsteady Friction Slope Method= 2
Unsteady Bridges Friction Slope Method= 1
Parabolic Critical Depth
Global Vel Dist=  1 , 1 , 1
Global Log Level= 0
CheckData=True
Encroach Param= -1, 0, 0, 0
BEGIN DESCRIPTION:
Multiple Run
END DESCRIPTION:

--- UNT 0415 IN LACR.f01 (steady flow) ---

Flow Title=Multiple
Program Version=4.10
Number of Profiles= 7
Profile Names=10-year,25-year,50-year,1pct_min,100-year,1pct_plu,500-year
River Rch & RM=UNT 0415 IN LACR,Reach-1         ,56070
     145     179     205     173     234     317     306
River Rch & RM=UNT 0415 IN LACR,Reach-1         ,51727
     459     610     732     645     872    1179    1244
River Rch & RM=UNT 0415 IN LACR,Reach-1         ,45651
     656     885    1073     954    1290    1745    1874
River Rch & RM=UNT 0415 IN LACR,Reach-1         ,34937
    1003    1381    1697    1527    2065    2793    3075
River Rch & RM=UNT 0415 IN LACR,Reach-1         ,34562
    1797    2526    3145    2862    3871    5235    5897
River Rch & RM=UNT 0415 IN LACR,Reach-1         ,28203
    1797    2526    3145    2862    3871    5235    5897
River Rch & RM=UNT 0415 IN LACR,Reach-1         ,19545
    1797    2526    3145    2862    3871    5235    5897
River Rch & RM=UNT 0415 IN LACR,Reach-1         ,14982
    2067    2918    3643    3323    4494    6078    6877
Boundary for River Rch & Prof#=UNT 0415 IN LACR,Reach-1         , 1
Up Type= 0
Dn Type= 3
Dn Slope=0.005
Boundary for River Rch & Prof#=UNT 0415 IN LACR,Reach-1         , 2
Up Type= 0
Dn Type= 3
Dn Slope=0.005
Boundary for River Rch & Prof#=UNT 0415 IN LACR,Reach-1         , 3
Up Type= 0
Dn Type= 3
Dn Slope=0.005
Boundary for River Rch & Prof#=UNT 0415 IN LACR,Reach-1         , 4
Up Type= 0
Dn Type= 3
Dn Slope=0.005
Boundary for River Rch & Prof#=UNT 0415 IN LACR,Reach-1         , 5
Up Type= 0
Dn Type= 3
Dn Slope=0.005
Boundary for River Rch & Prof#=UNT 0415 IN LACR,Reach-1         , 6
Up Type= 0
Dn Type= 3
Dn Slope=0.005
Boundary for River Rch & Prof#=UNT 0415 IN LACR,Reach-1         , 7
Up Type= 0
Dn Type= 3
Dn Slope=0.005
DSS Import GetInterval= 0
DSS Import GetPeak= 0
DSS Import FillOption= 0

--- UNT 0415 IN LACR.g01 (geometry) ---

Geom Title=Existing Conditions
Program Version=4.10

River Reach=UNT 0415 IN LACR,Reach-1
Reach XY= 30
      3661856.27      10687059.9      3662719.75       10683060.
       3661910.5       10681391.        3662684.       10679032.
      3663570.25       10678295.        3663027.       10678037.
        3662788.       10675525.        3661931.       10673915.
      3662063.75       10671574.      3661397.25       10670180.
      3661717.25       10669676.       3660998.5       10669498.
      3661635.75       10668269.       3661026.5       10668046.
        3661367.       10667172.      3660515.25       10666656.
      3660989.75       10665677.        3660604.       10663397.
        3662396.       10662199.      3662858.25       10660210.
        3662859.       10659371.      3661153.25       10658420.
      3660914.75       10657162.       3661310.5       10656743.
       3660880.5       10656138.      3663349.61     10652860.19
      3662899.61     10651610.19      3663299.61     10650460.19
      3665599.61     10649560.19      3666749.61     10647210.19

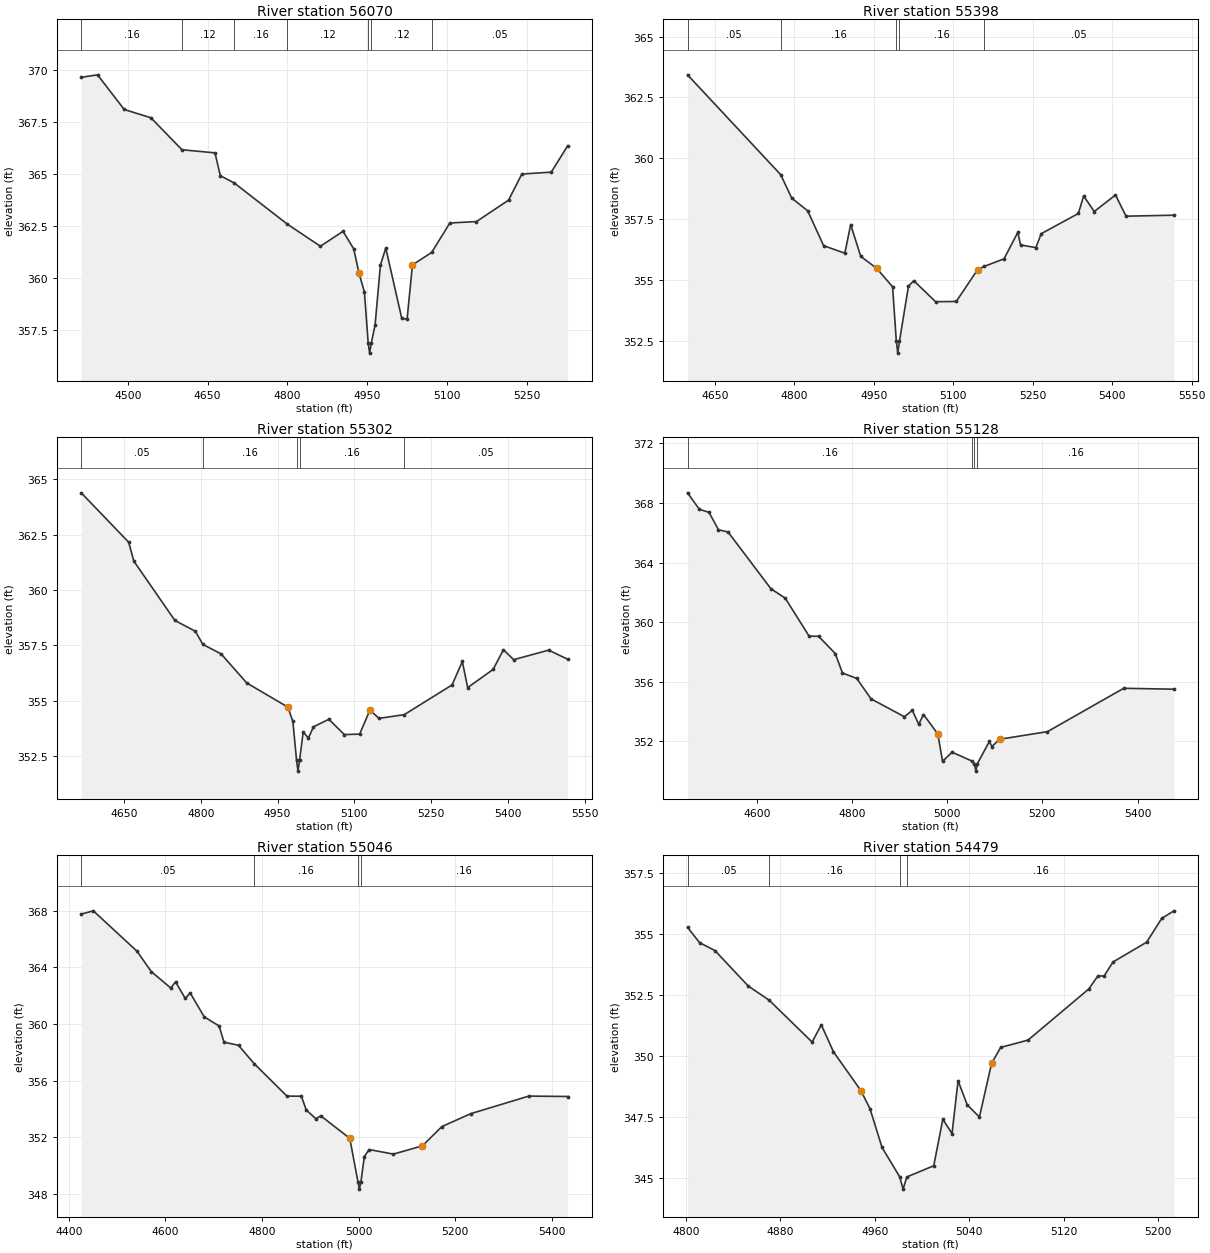
Type RM Length L Ch R = 1 ,56070   ,672,672,672
BEGIN DESCRIPTION:
UNT 0415 IN LACR 70.0
END DESCRIPTION:
XS GIS Cut Line= 2
      3662480.16     10686921.24      3661568.77     10686848.33
#Sta/Elev= 30
  4412.6  369.66  4443.2  369.78  4493.4  368.11  4543.6  367.71  4601.9  366.17
    4664  366.02    4674  364.92  4700.1  364.57  4799.7  362.59  4862.1  361.52
  4904.7  362.24  4924.8  361.39  4934.8  360.21  4944.8  359.32  4951.9  356.87
  4954.6  356.37  4957.9  356.87  4964.9  357.72  4974.9  360.61    4985  361.43
  5015.1  358.04  5025.1  358.01  5035.1  360.62  5071.2  361.22  5105.4  362.64
  5155.5  362.71  5215.7  363.74  5240.8     365    5296  365.09  5326.9  366.36
#Mann= 7 ,-1 , 0
  4412.6     .16       0  4601.9     .12       0  4700.1     .16       0
  4799.7     .12       0  4951.9     .07       0  4957.9     .12       0
  5071.2     .05       0
Bank Sta=4934.8,5035.1
XS Rating Curve= 0 ,0
Exp/Cntr=0.3,0.1

Type RM Length L Ch R = 1 ,55398   ,96,96,96
BEGIN DESCRIPTION:
Mapping XS 38eacdab
END DESCRIPTION:
XS GIS Cut Line= 2
      3662376.02     10686244.16      3661459.41     10686186.87
#Sta/Elev= 30
  4598.2  363.43  4774.2  359.33    4795  358.37  4825.1  357.85  4855.1  356.42
  4895.2  356.11  4906.2  357.28  4925.3  355.98  4955.3  355.49  4985.4  354.73
  4992.4  352.51  4995.1  352.01  4998.4  352.51  5015.4  354.76  5025.4  354.98
  5066.6  354.12  5105.6  354.13  5145.7  355.43  5158.5  355.57  5195.8  355.88
  5221.9  356.97  5226.9  356.45  5255.9  356.34  5265.9  356.91  5336.1  357.74
  5346.1  358.46  5366.1  357.82  5406.2   358.5  5426.2  357.63  5516.6  357.67
#Mann= 5 ,-1 , 0
  4598.2     .05       0  4774.2     .16       0  4992.4     .07       0
  4998.4     .16       0  5158.5     .05       0
Bank Sta=4955.3,5145.7
XS Rating Curve= 0 ,0
Exp/Cntr=0.3,0.1

Type RM Length L Ch R = 1 ,55302   ,174,174,174
BEGIN DESCRIPTION:
UNT 0415 IN LACR 69.0
END DESCRIPTION:
XS GIS Cut Line= 2
      3662402.07     10686150.41       3661454.4     10686093.13
#Sta/Elev= 30
  4566.8  364.39  4659.4  362.16  4669.4  361.31  4749.6  358.63  4789.7  358.14
  4804.1  357.55  4839.8  357.12  4889.8  355.81    4970  354.72  4979.9  354.07
    4987  352.33  4989.8  351.83    4993  352.33    5000   353.6  5010.1  353.32
  5020.1  353.83  5050.1  354.17  5080.2  353.48  5110.2   353.5  5130.3  354.59
  5147.9  354.21  5197.3  354.38  5290.6  355.72  5310.6  356.78    5321   355.6
  5370.7  356.42  5390.8  357.31  5410.8  356.86    5479  357.29  5516.2  356.88
#Mann= 5 ,-1 , 0
  4566.8     .05       0  4804.1     .16       0    4987     .07       0
    4993     .16       0  5197.3     .05       0
Bank Sta=4970,5130.3
XS Rating Curve= 0 ,0
Exp/Cntr=0.3,0.1

Type RM Length L Ch R = 1 ,55128   ,82,82,82
BEGIN DESCRIPTION:
UNT 0415 IN LACR 68.0
END DESCRIPTION:
XS GIS Cut Line= 2
      3662464.61     10685994.16      3661444.22     10685931.69
#Sta/Elev= 30
  4454.3  368.68  4479.3  367.57  4499.4  367.37  4519.4   366.2  4539.5  366.05
  4629.6  362.24  4659.7  361.61  4709.8  359.06  4729.8  359.05  4764.8  357.89
  4779.9  356.59    4810  356.22    4840  354.85  4910.1  353.65  4926.8  354.08
  4940.2  353.14  4950.2   353.8  4980.3   352.5  4990.3  350.66  5010.3  351.27
  5051.8  350.68  5057.4   350.5  5060.2     350  5063.4   350.5  5088.7  351.99
  5093.8  351.65  5110.5  352.14  5210.7  352.65    5371  355.56  5476.6   355.5
#Mann= 4 ,-1 , 0
  4454.3     .16       0  5051.8     .16       0  5057.4     .04       0
  5063.4     .16       0
Bank Sta=4980.3,5110.5
XS Rating Curve= 0 ,0
Exp/Cntr=0.3,0.1

Type RM Length L Ch R = 1 ,55046   ,567,567,567
BEGIN DESCRIPTION:
Mapping XS 79586729
END DESCRIPTION:
XS GIS Cut Line= 2
      3662464.54     10685921.24      3661459.39     10685858.74
#Sta/Elev= 30
  4425.8  367.75  4450.8  367.98    4541  365.14    4571  363.69  4611.1  362.54
  4621.1  362.97  4641.2   361.8  4651.2   362.2  4680.3  360.51  4711.3  359.86
  4721.3  358.72  4751.4   358.5    4784   357.2  4851.6  354.92  4881.6  354.91
  4891.6  353.94  4911.7  353.32  4921.7  353.53  4981.8  351.94  4998.8  348.86
  5001.5  348.36  5004.8  348.86  5011.9  350.66  5021.9  351.15    5072  350.83
  5132.1  351.41  5172.5  352.77  5232.3  353.68  5352.5  354.92  5432.9  354.89
#Mann= 4 ,-1 , 0
  4425.8     .05       0    4784     .16       0  4998.8     .07       0
  5004.8     .16       0
Bank Sta=4981.8,5132.1
XS Rating Curve= 0 ,0
Exp/Cntr=0.3,0.1

Type RM Length L Ch R = 1 ,54479   ,415,415,415
BEGIN DESCRIPTION:
UNT 0415 IN LACR 67.0
END DESCRIPTION:
XS GIS Cut Line= 3
      3662099.59     10685410.18      3661899.61     10685360.19
       3661699.6     10685310.19
#Sta/Elev= 30
  4801.2  355.28  4811.5  354.65  4824.4  354.33  4852.7  352.87  4870.4  352.29
  4906.8  350.57  4914.6  351.28  4924.9  350.17  4948.1  348.58  4955.8  347.84
  4966.1  346.24  4981.1  345.03  4983.9  344.53  4987.1  345.03  5009.9  345.49
  5017.6   347.4  5025.4  346.81  5030.5  348.98  5038.3  347.99  5048.6  347.49
  5058.9  349.69  5066.6  350.35  5089.8  350.65  5141.3  352.75  5149.1  353.29
  5154.2  353.28  5161.9  353.86  5190.3  354.67  5203.2  355.65  5213.5  355.96
#Mann= 4 ,-1 , 0
  4801.2     .05       0  4870.4     .16       0  4981.1     .07       0
  4987.1     .16       0
Bank Sta=4948.1,5058.9
XS Rating Curve= 0 ,0
Exp/Cntr=0.3,0.1

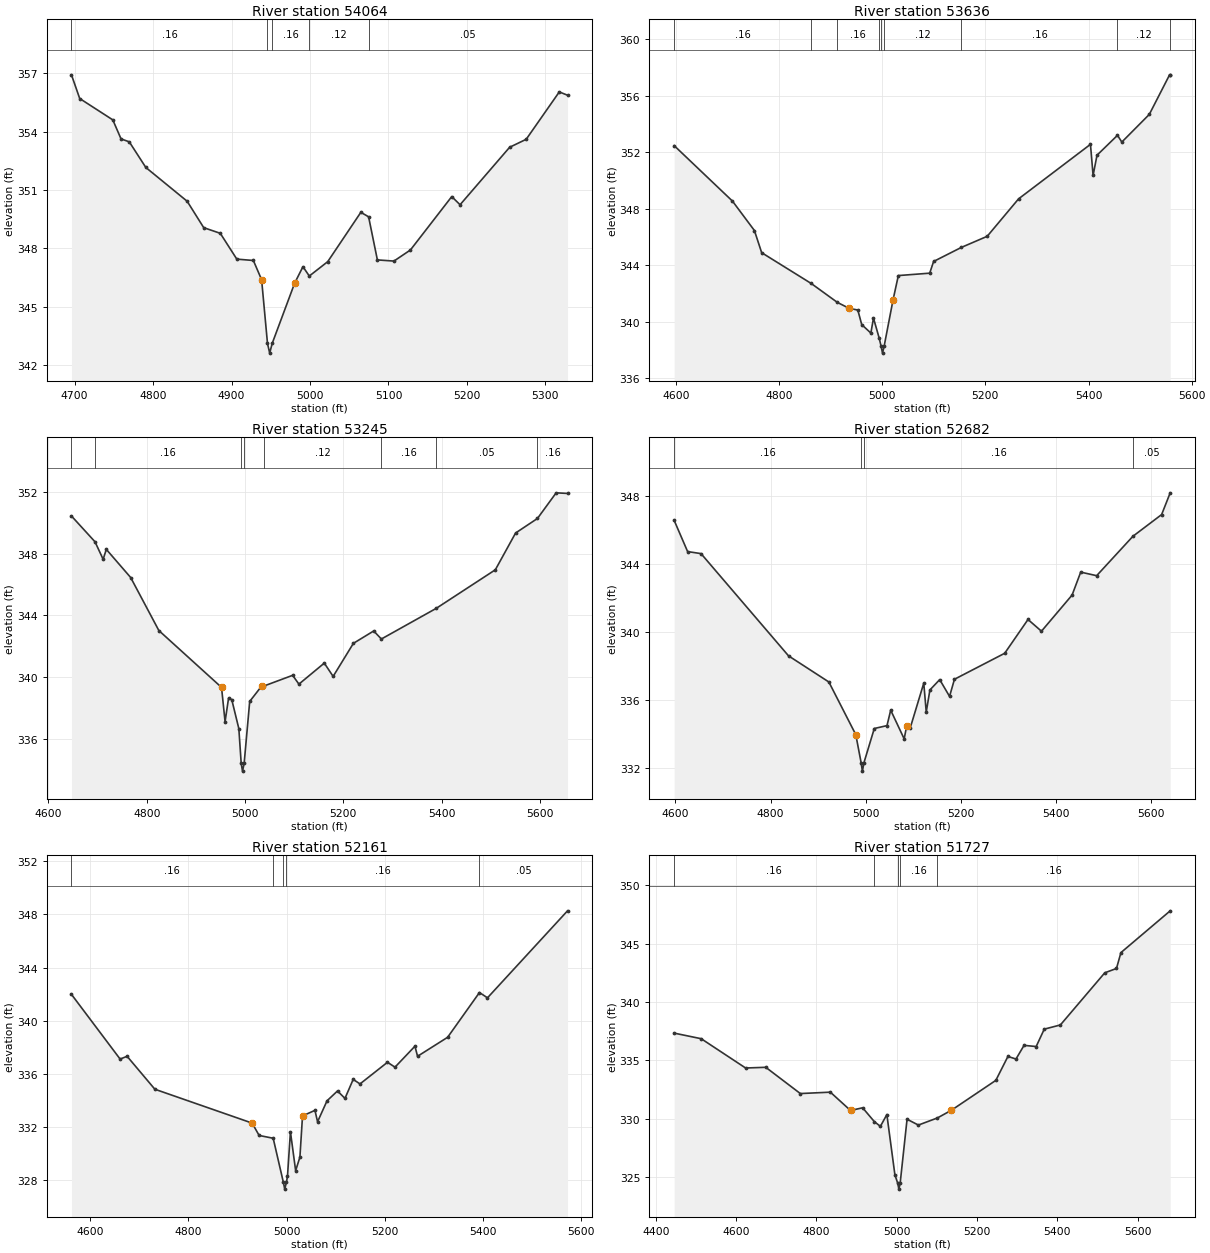
Type RM Length L Ch R = 1 ,54064   ,428,428,428
BEGIN DESCRIPTION:
UNT 0415 IN LACR 66.0
END DESCRIPTION:
XS GIS Cut Line= 3
      3662299.57     10685060.17      3661999.61     10684960.19
      3661699.62     10685060.18
#Sta/Elev= 30
  4695.9  356.93  4706.4  355.71  4748.6  354.61  4759.1  353.63  4769.6  353.48
  4790.7  352.16  4843.4  350.42  4864.5  349.06  4885.6  348.77  4906.7  347.44
  4927.8  347.37  4938.3  346.38  4945.8   343.1  4948.6   342.6  4951.8   343.1
  4980.5  346.21    4991  347.05  4999.1  346.57  5022.6  347.31  5064.8  349.85
  5074.7  349.62  5085.9   347.4    5107  347.34    5128  347.91  5180.7  350.66
  5191.3  350.24  5254.5   353.2  5275.6  353.61  5317.8  356.05  5328.3  355.88
#Mann= 5 ,-1 , 0
  4695.9     .16       0  4945.8     .07       0  4951.8     .16       0
  4999.1     .12       0  5074.7     .05       0
Bank Sta=4938.3,4980.5
XS Rating Curve= 0 ,0
Exp/Cntr=0.3,0.1

Type RM Length L Ch R = 1 ,53636   ,391,391,391
BEGIN DESCRIPTION:
UNT 0415 IN LACR 65.0
END DESCRIPTION:
XS GIS Cut Line= 3
      3662449.61     10684810.19      3662199.61     10684560.19
      3661599.63     10684660.18
#Sta/Elev= 30
  4596.6  352.48  4709.7  348.55  4752.2  346.47  4766.3   344.9  4862.4  342.72
  4913.1  341.38    4936  340.96  4952.7  340.84  4960.3  339.81    4978  339.21
  4983.1  340.27  4994.1  338.86  4997.8  338.29  5000.6  337.79  5003.8  338.29
  5021.1  341.57  5031.3  343.28  5092.1  343.45  5099.7  344.28  5153.3  345.27
  5203.6  346.06  5264.4  348.71  5403.8  352.57  5408.9  350.37  5416.5   351.8
  5456.2  353.21  5464.6  352.73  5517.9  354.69  5557.2  357.49  5558.4  357.49
#Mann= 9 ,-1 , 0
  4596.6     .16       0  4862.4     .12       0  4913.1     .16       0
  4994.1     .12       0  4997.8     .07       0  5003.8     .12       0
  5153.3     .16       0  5456.2     .12       0  5557.2     .08       0
Bank Sta=4936,5021.1
XS Rating Curve= 0 ,0
Exp/Cntr=0.3,0.1

Type RM Length L Ch R = 1 ,53245   ,563,563,563
BEGIN DESCRIPTION:
UNT 0415 IN LACR 64.0
END DESCRIPTION:
XS GIS Cut Line= 3
      3662649.59     10684510.17      3662349.61     10684260.19
      3661749.66     10684410.18
#Sta/Elev= 30
    4647  350.43  4694.9  348.76  4711.4  347.63  4717.9  348.27  4767.4  346.45
  4824.7  343.02  4952.2  339.34  4959.4  337.12  4966.5  338.64    4973  338.55
  4987.4  336.67  4992.2  334.42  4994.9  333.92  4998.2  334.42  5009.5  338.43
  5034.2  339.44  5039.5  339.44  5096.8  340.12  5109.6  339.55  5161.2  340.91
  5179.2  340.05  5220.4  342.19  5261.7  342.99  5277.3  342.47  5388.7  344.45
  5509.1  346.95  5550.3  349.33  5594.7  350.27  5632.8  351.93  5655.9  351.89
#Mann= 8 ,-1 , 0
    4647     .05       0  4694.9     .16       0  4992.2     .07       0
  4998.2     .16       0  5039.5     .12       0  5277.3     .16       0
  5388.7     .05       0  5594.7     .16       0
Bank Sta=4952.2,5034.2
XS Rating Curve= 0 ,0
Exp/Cntr=0.3,0.1

Type RM Length L Ch R = 1 ,52682   ,521,521,521
BEGIN DESCRIPTION:
UNT 0415 IN LACR 63.0
END DESCRIPTION:
XS GIS Cut Line= 3
      3662749.59     10684110.17      3662449.61     10683810.19
      3661849.61     10683960.19
#Sta/Elev= 30
  4597.2  346.58  4625.5  344.74  4653.7  344.62  4837.6   338.6  4922.4  337.06
    4979  333.96  4990.2  332.31  4992.9  331.81  4996.2  332.31  5017.9  334.32
  5044.6  334.49  5052.4   335.4  5080.7  333.71  5085.9  334.45  5093.6  334.37
  5121.9  336.99  5127.1  335.29  5134.8  336.59  5155.4   337.2  5176.1  336.21
  5186.4  337.22    5292  338.75    5341  340.74  5369.3  340.05  5433.7  342.18
  5451.8  343.53  5485.3  343.32  5561.5  345.64  5621.9  346.92  5639.9   348.2
#Mann= 4 ,-1 , 0
  4597.2     .16       0  4990.2     .07       0  4996.2     .16       0
  5561.5     .05       0
Bank Sta=4979,5085.9
XS Rating Curve= 0 ,0
Exp/Cntr=0.3,0.1

Type RM Length L Ch R = 1 ,52161   ,434,434,434
BEGIN DESCRIPTION:
UNT 0415 IN LACR 62.0
END DESCRIPTION:
XS GIS Cut Line= 3
      3662899.64     10683710.22      3662599.61     10683410.19
      3662049.65      10683210.2
#Sta/Elev= 30
  4562.3  341.98  4661.3  337.11  4675.5  337.32    4732  334.84    4930  332.29
  4944.2  331.36  4972.8  331.15  4993.6  327.82  4996.3  327.32  4999.6  327.82
  5001.9  328.28  5007.9  331.64  5018.5  328.71  5027.2  329.73  5032.5  332.83
  5057.8  333.25  5063.1  332.39  5082.4  333.97  5103.7  334.71  5118.9  334.15
  5135.6  335.58  5149.5  335.24  5205.4  336.87  5220.7   336.5  5261.3  338.08
  5266.6  337.32  5327.8  338.75  5392.6  342.12  5408.9  341.72  5571.8  348.27
#Mann= 5 ,-1 , 0
  4562.3     .16       0  4972.8     .16       0  4993.6     .07       0
  4999.6     .16       0  5392.6     .05       0
Bank Sta=4930,5032.5
XS Rating Curve= 0 ,0
Exp/Cntr=0.3,0.1

Type RM Length L Ch R = 1 ,51727   ,517,517,517
BEGIN DESCRIPTION:
UNT 0415 IN LACR 61.0
END DESCRIPTION:
XS GIS Cut Line= 2
      3663266.68     10682973.32      3662037.52     10683098.32
#Sta/Elev= 30
  4445.9  337.33  4513.3  336.85  4623.9  334.34  4674.1   334.4  4760.2  332.15
    4835  332.27  4885.2   330.7  4915.4  330.93  4944.6  329.74  4959.6  329.34
  4975.7  330.35  4995.8  325.17  5002.8  324.46  5005.6  323.96  5008.8  324.46
    5026  329.95  5054.2  329.45  5101.6  330.06  5136.5  330.72  5247.1  333.28
  5277.2  335.33  5297.3  335.11  5317.4  336.28  5347.6  336.18  5367.7  337.67
  5407.9  338.03  5518.5   342.5  5547.6  342.87  5558.7  344.23  5681.4  347.81
#Mann= 5 ,-1 , 0
  4445.9     .16       0  4944.6     .16       0  5002.8     .07       0
  5008.8     .16       0  5101.6     .16       0
Bank Sta=4885.2,5136.5
XS Rating Curve= 0 ,0
Exp/Cntr=0.3,0.1

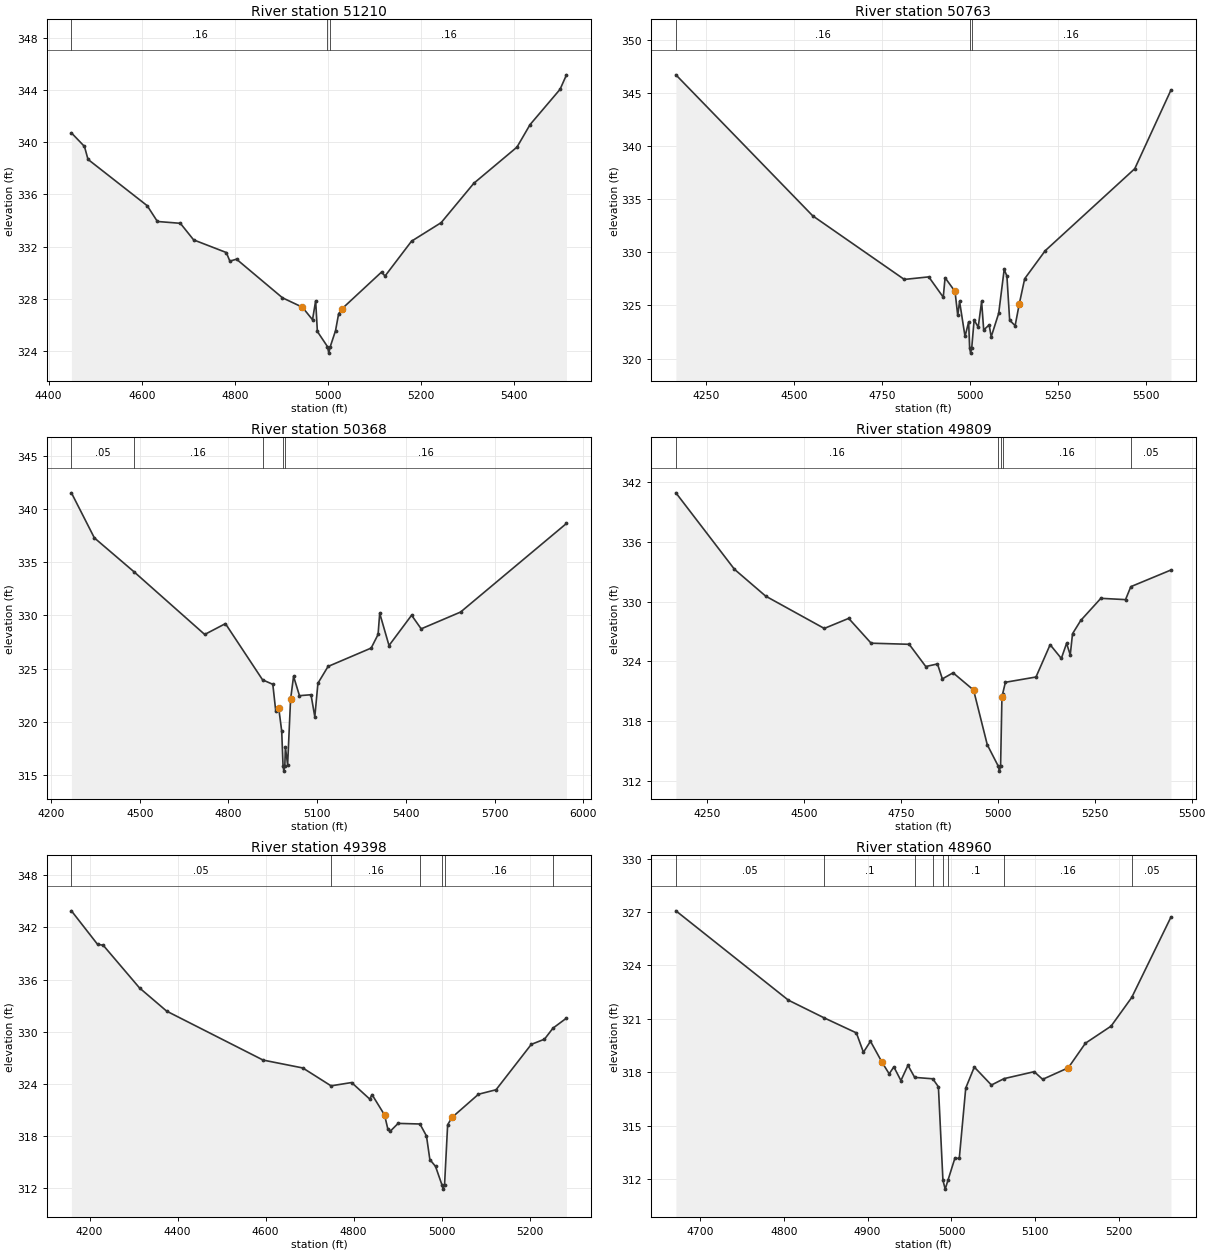
Type RM Length L Ch R = 1 ,51210   ,447,447,447
BEGIN DESCRIPTION:
UNT 0415 IN LACR 60.0
END DESCRIPTION:
XS GIS Cut Line= 3
      3662849.58     10682260.21      3662449.61     10682610.19
      3662049.59      10682960.2
#Sta/Elev= 30
    4449  340.71    4477  339.67  4484.6  338.68  4611.7  335.13  4633.6  333.92
  4682.9  333.78  4711.4  332.51  4781.6  331.54  4789.2  330.88  4803.5  331.03
  4902.2  328.07  4944.9  327.35  4966.7  326.39  4973.4  327.84  4977.1  325.49
  4998.8  324.33  5001.6  323.83  5004.8  324.33  5016.1  325.55  5022.7  326.84
  5030.3  327.24  5114.8  330.04  5122.4  329.74  5179.3  332.41  5242.9  333.83
  5313.1  336.85  5405.7  339.62  5433.7  341.34  5498.2  344.05    5512  345.16
#Mann= 3 ,-1 , 0
    4449     .16       0  4998.8     .03       0  5004.8     .16       0
Bank Sta=4944.9,5030.3
XS Rating Curve= 0 ,0
Exp/Cntr=0.3,0.1

Type RM Length L Ch R = 1 ,50763   ,395,395,395
BEGIN DESCRIPTION:
UNT 0415 IN LACR 59.0
END DESCRIPTION:
XS GIS Cut Line= 3
      3662999.62     10682110.19      3662199.61     10682310.19
      3661899.62     10682810.17
#Sta/Elev= 30
    4163  346.69  4552.1  333.43  4812.4  327.45    4882  327.69  4923.2  325.78
  4928.4  327.61  4956.7  326.32  4964.4  324.06  4969.6  325.39  4985.1  322.09
  4995.4  323.45  4998.2  321.02    5001  320.52  5004.2  321.02    5011  323.64
  5022.6  322.96  5032.3  325.38  5038.2   322.7  5053.7  323.17  5059.5  322.05
  5080.9  324.27  5096.5   328.4  5104.2  327.76    5112  323.62  5127.6   323.1
  5139.2  325.12  5154.8  327.52  5213.1  330.15  5467.7  337.86  5570.7  345.26
#Mann= 3 ,-1 , 0
    4163     .16       0  4998.2     .03       0  5004.2     .16       0
Bank Sta=4956.7,5139.2
XS Rating Curve= 0 ,0
Exp/Cntr=0.3,0.1

Type RM Length L Ch R = 1 ,50368   ,559,559,559
BEGIN DESCRIPTION:
UNT 0415 IN LACR 58.0
END DESCRIPTION:
XS GIS Cut Line= 3
       3662799.6     10681910.19      3661999.61     10681960.19
       3661649.6     10682760.22
#Sta/Elev= 30
  4268.7  341.54  4346.3   337.3  4479.6  334.13  4719.6  328.21  4789.7  329.23
  4915.4  323.94    4950  323.52    4960  320.99  4970.1  321.26  4980.1  319.12
  4984.6  315.85  4987.3  315.35  4990.6  315.85  4992.6   317.6  5000.1  315.94
  5010.1  322.11  5020.2  324.27  5040.2  322.45  5079.2  322.54  5092.1  320.46
  5102.6  323.62  5136.9   325.2  5282.7  326.93  5306.1  328.21  5311.6  330.21
  5343.1  327.17  5419.5  330.02  5451.9  328.74  5585.2  330.32  5943.5  338.66
#Mann= 5 ,-1 , 0
  4268.7     .05       0  4479.6     .16       0  4915.4     .05       0
  4984.6     .03       0  4990.6     .16       0
Bank Sta=4970.1,5010.1
XS Rating Curve= 0 ,0
Exp/Cntr=0.3,0.1

Type RM Length L Ch R = 1 ,49809   ,411,411,411
BEGIN DESCRIPTION:
UNT 0415 IN LACR 57.0
END DESCRIPTION:
XS GIS Cut Line= 3
      3662749.62     10681510.19      3661949.61     10681610.19
      3661549.64     10681360.21
#Sta/Elev= 30
  4168.7  340.91  4319.9  333.24  4400.5  330.55  4551.7  327.31  4614.7  328.32
  4672.6  325.83  4770.9  325.72  4813.7  323.49  4843.9  323.75  4856.5  322.25
  4884.2  322.86  4937.1  321.13  4972.4  315.65  5000.8   313.5  5003.6     313
  5006.8   313.5  5010.3  320.45  5012.2  320.76  5019.2  321.91  5098.2  322.44
  5134.7  325.68  5163.6   324.3  5177.2  325.82  5186.6  324.65  5192.5  326.78
  5213.7  328.11  5265.6  330.33  5329.3   330.2    5343   331.5  5446.6  333.17
#Mann= 5 ,-1 , 0
  4168.7     .16       0  5000.8     .03       0  5006.8     .05       0
  5012.2     .16       0    5343     .05       0
Bank Sta=4937.1,5010.3
XS Rating Curve= 0 ,0
Exp/Cntr=0.3,0.1

Type RM Length L Ch R = 1 ,49398   ,438,438,438
BEGIN DESCRIPTION:
UNT 0415 IN LACR 56.0
END DESCRIPTION:
XS GIS Cut Line= 3
      3662799.64      10681410.2      3661999.61     10681210.19
      3661699.57     10681210.19
#Sta/Elev= 30
  4158.9  343.92  4218.2  340.06  4231.1  339.95  4313.6  335.03  4375.4  332.35
  4594.4  326.71  4684.6   325.8  4748.7  323.74  4795.4  324.12  4836.7  322.21
  4841.8  322.73  4870.2  320.39  4877.9  318.73  4883.1   318.5  4901.1  319.41
  4950.7  319.34  4965.5  317.96  4973.2  315.24  4986.1  314.45  5000.6  312.33
  5003.3  311.83  5006.6  312.33  5013.6  319.25  5023.6   320.1  5083.6  322.77
  5123.6  323.29  5203.6  328.52  5233.6  329.12  5252.9  330.39  5283.6  331.55
#Mann= 6 ,-1 , 0
  4158.9     .05       0  4748.7     .16       0  4950.7     .16       0
  5000.6     .07       0  5006.6     .16       0  5252.9     .05       0
Bank Sta=4870.2,5023.6
XS Rating Curve= 0 ,0
Exp/Cntr=0.3,0.1

Type RM Length L Ch R = 1 ,48960   ,403,403,403
BEGIN DESCRIPTION:
UNT 0415 IN LACR 55.0
END DESCRIPTION:
XS GIS Cut Line= 3
      3662499.57     10681010.17      3662199.61     10680860.19
      3661949.63     10680810.19
#Sta/Elev= 30
  4671.4  327.07  4805.5  322.05  4848.4  321.05  4886.6  320.21    4895  319.12
  4903.4  319.74  4917.3  318.55  4925.7  317.91  4931.3   318.3  4939.7  317.53
  4948.1  318.39  4956.1  317.71  4977.7  317.63  4984.4  317.18  4989.8  311.93
  4992.5  311.43  4995.8  311.93    5004  313.16  5009.3  313.16    5017  317.11
  5027.2  318.29  5047.6  317.28  5062.7  317.64  5098.6  318.03  5108.7   317.6
  5139.3  318.25  5159.7  319.63  5190.3  320.59  5214.9   322.2  5261.7  326.72
#Mann= 8 ,-1 , 0
  4671.4     .05       0  4848.4      .1       0  4956.1     .05       0
  4977.7      .1       0  4989.8     .07       0  4995.8      .1       0
  5062.7     .16       0  5214.9     .05       0
Bank Sta=4917.3,5139.3
XS Rating Curve= 0 ,0
Exp/Cntr=0.3,0.1

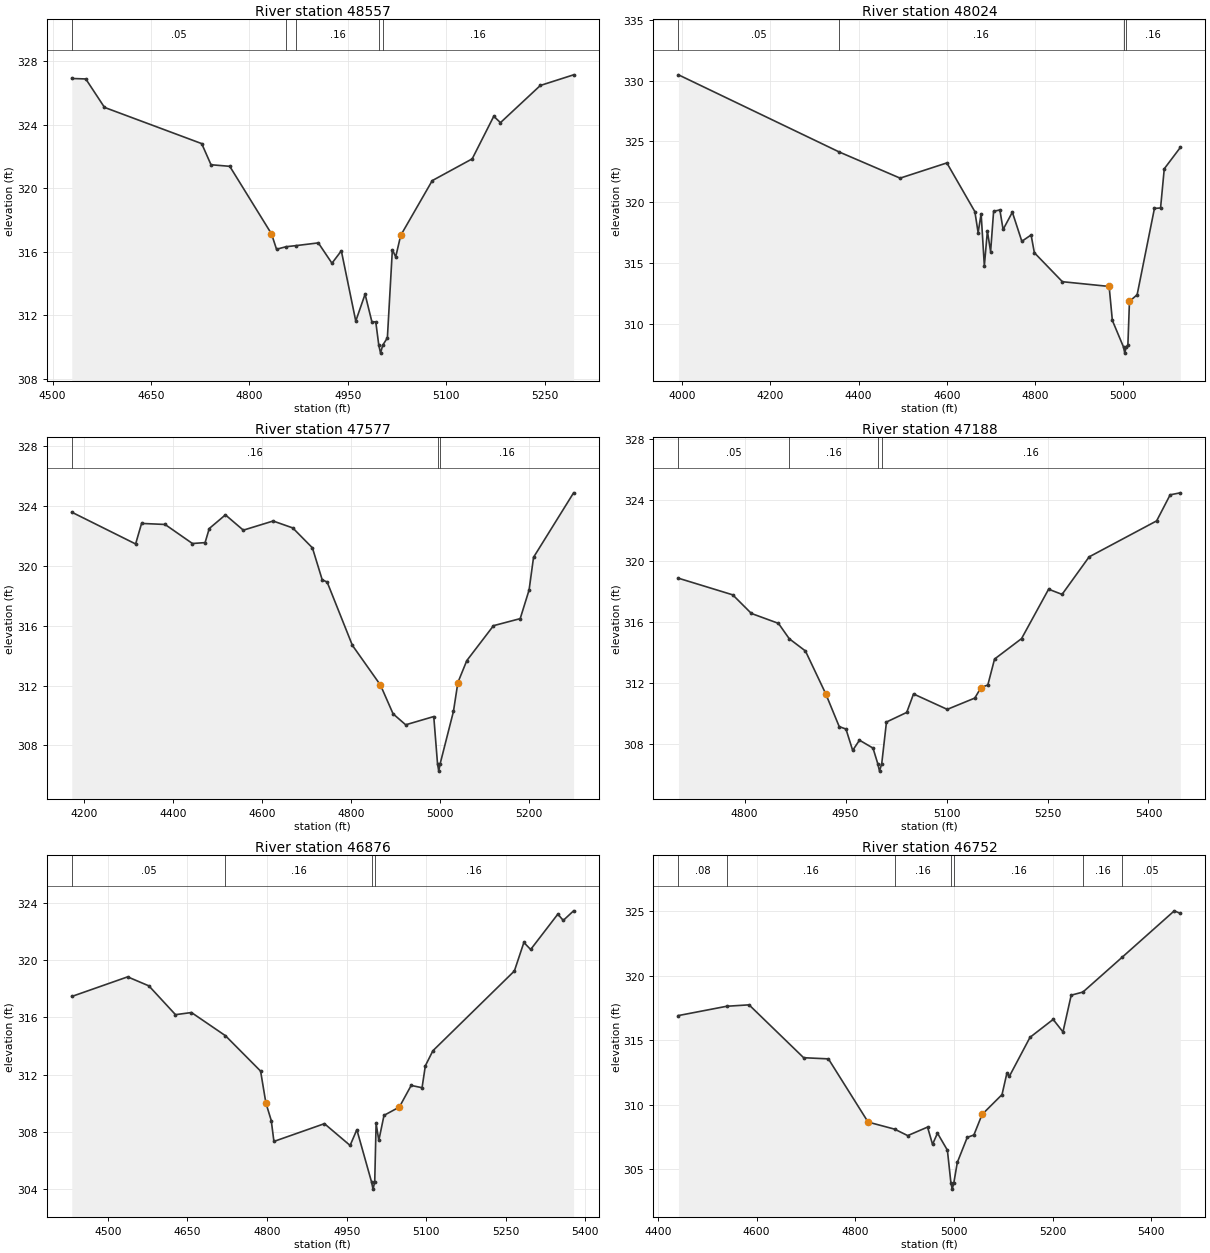
Type RM Length L Ch R = 1 ,48557   ,533,533,533
BEGIN DESCRIPTION:
UNT 0415 IN LACR 54.0
END DESCRIPTION:
XS GIS Cut Line= 3
      3662699.58     10680810.16      3662349.61     10680510.19
      3662049.59     10680460.18
#Sta/Elev= 30
  4529.2   326.9  4550.6  326.87  4579.1  325.08  4727.3   322.8  4741.5  321.47
  4770.1  321.37  4833.7  317.12  4841.4  316.15  4856.1  316.31  4871.6  316.38
  4905.1  316.55  4925.9  315.27  4940.2  316.05  4962.2  311.63  4976.4  313.32
  4986.8  311.58  4992.7  311.58  4997.3  310.11    5000  309.61  5003.3  310.11
  5010.4  310.57    5018  316.12  5023.1  315.67  5030.7  317.02  5078.8  320.47
  5139.7  321.84  5172.6  324.52  5182.8  324.12  5243.6  326.46  5294.3  327.13
#Mann= 5 ,-1 , 0
  4529.2     .05       0  4856.1      .1       0  4871.6     .16       0
  4997.3     .07       0  5003.3     .16       0
Bank Sta=4833.7,5030.7
XS Rating Curve= 0 ,0
Exp/Cntr=0.3,0.1

Type RM Length L Ch R = 1 ,48024   ,447,447,447
BEGIN DESCRIPTION:
UNT 0415 IN LACR 53.0
END DESCRIPTION:
XS GIS Cut Line= 3
      3663099.57     10680760.16      3662349.61     10680060.19
      3662249.58     10680010.17
#Sta/Elev= 30
  3991.9  330.47  4356.3  324.13  4494.3  321.98  4600.3  323.23  4663.8  319.23
  4671.2   317.5    4678  319.05  4685.3  314.77  4692.2  317.63  4699.5  315.94
  4706.3  319.25  4720.5  319.37  4727.8  317.76  4748.8  319.18  4770.3  316.79
  4791.3  317.31  4798.7  315.85  4862.2  313.47  4968.2  313.08  4975.5  310.29
  5000.8   308.1  5003.6   307.6  5006.8   308.1  5010.7  308.26  5014.3  311.85
  5031.7   312.4  5070.9  319.49  5084.8  319.53  5093.2  322.75  5129.6   324.5
#Mann= 4 ,-1 , 0
  3991.9     .05       0  4356.3     .16       0  5000.8     .07       0
  5006.8     .16       0
Bank Sta=4968.2,5014.3
XS Rating Curve= 0 ,0
Exp/Cntr=0.3,0.1

Type RM Length L Ch R = 1 ,47577   ,389,389,389
BEGIN DESCRIPTION:
UNT 0415 IN LACR 52.0
END DESCRIPTION:
XS GIS Cut Line= 3
      3662899.62     10680460.22      3662549.61     10679710.19
      3662249.59     10679710.19
#Sta/Elev= 30
  4171.9  323.56  4315.4  321.44  4328.8  322.81  4381.6  322.74  4443.1  321.47
  4471.5  321.53  4480.9  322.47  4517.2  323.38  4557.4  322.36  4624.4  322.97
  4668.5  322.51  4712.7  321.18  4734.7  319.05  4745.8   318.9  4802.5  314.68
  4865.6  312.03    4894  310.11  4922.3  309.38  4985.4  309.93  4993.8  306.79
  4996.6  306.29  4999.8  306.79  5029.6  310.27  5039.6   312.2  5059.6  313.66
  5119.6  315.99  5179.6  316.46  5199.6  318.37  5209.6  320.55  5299.6  324.85
#Mann= 3 ,-1 , 0
  4171.9     .16       0  4993.8     .03       0  4999.8     .16       0
Bank Sta=4865.6,5039.6
XS Rating Curve= 0 ,0
Exp/Cntr=0.3,0.1

Type RM Length L Ch R = 1 ,47188   ,312,312,312
BEGIN DESCRIPTION:
UNT 0415 IN LACR 51.0
END DESCRIPTION:
XS GIS Cut Line= 2
      3662997.54     10679641.72      3662254.57     10679579.23
#Sta/Elev= 30
  4701.7  318.84  4782.3  317.75    4810  316.53  4850.2  315.88  4866.3  314.87
  4890.3  314.07  4920.4  311.27  4940.5  309.11  4950.5  308.95  4960.5  307.55
  4970.6  308.22  4990.7   307.7  4997.7  306.69  5000.4  306.19  5003.7  306.69
  5010.7  309.41  5040.8  310.04  5050.9  311.25    5101  310.24  5141.9  310.98
  5151.2  311.67  5161.3  311.84  5171.3  313.54  5211.4  314.88  5251.6  318.12
  5271.6  317.78  5311.8  320.24  5412.1   322.6  5432.2  324.31  5447.3  324.44
#Mann= 4 ,-1 , 0
  4701.7     .05       0  4866.3     .16       0  4997.7     .07       0
  5003.7     .16       0
Bank Sta=4920.4,5151.2
XS Rating Curve= 0 ,0
Exp/Cntr=0.3,0.1

Type RM Length L Ch R = 1 ,46876   ,124,124,124
BEGIN DESCRIPTION:
Mapping XS 2d54f868
END DESCRIPTION:
XS GIS Cut Line= 3
      3663174.63     10679402.14      3662685.06     10679367.42
      3662240.57     10679464.65
#Sta/Elev= 30
  4431.9  317.46  4537.2  318.83  4577.3   318.2  4627.4  316.19  4657.5  316.34
  4721.6  314.72  4787.8  312.25  4797.8  310.02  4807.9   308.8  4812.9  307.34
  4908.1  308.58  4956.5  307.06  4969.2  308.16  4996.9  304.51  4999.7  304.01
  5002.9  304.51  5005.5   308.6  5010.6  307.41  5020.4  309.16  5049.3  309.74
  5071.6  311.25  5092.1  311.09  5098.3  312.62  5112.5  313.67  5266.1  319.24
    5284  321.23  5296.8  320.74    5348  323.21  5358.2  322.77  5377.7  323.44
#Mann= 4 ,-1 , 0
  4431.9     .05       0  4721.6     .16       0  4996.9     .07       0
  5002.9     .16       0
Bank Sta=4797.8,5049.3
XS Rating Curve= 0 ,0
Exp/Cntr=0.3,0.1

Type RM Length L Ch R = 1 ,46752   ,110,110,110
BEGIN DESCRIPTION:
Mapping XS 76b7c17f
END DESCRIPTION:
XS GIS Cut Line= 3
      3663191.99      10679332.7      3662546.17      10679270.2
       3662188.5     10679357.01
#Sta/Elev= 30
  4441.8  316.92  4539.6  317.64  4584.8  317.75  4695.4  313.65  4745.6  313.56
    4826  308.66  4879.8  308.11  4906.3  307.61  4946.5  308.27  4956.6  306.93
  4966.6   307.8  4986.7  306.48  4993.8  303.96  4996.5  303.46  4999.8  303.96
  5006.8  305.53  5026.9  307.47  5040.4  307.66    5057  309.25  5097.4  310.79
  5107.2  312.44  5112.3  312.21  5154.1  315.23    5201  316.62  5220.9  315.65
  5237.6   318.5  5261.3  318.74  5341.1  321.45  5446.5  325.04  5458.7  324.84
#Mann= 7 ,-1 , 0
  4441.8     .08       0  4539.6     .16       0  4879.8     .16       0
  4993.8     .07       0  4999.8     .16       0  5261.3     .16       0
  5341.1     .05       0
Bank Sta=4826,5057
XS Rating Curve= 0 ,0
Exp/Cntr=0.3,0.1

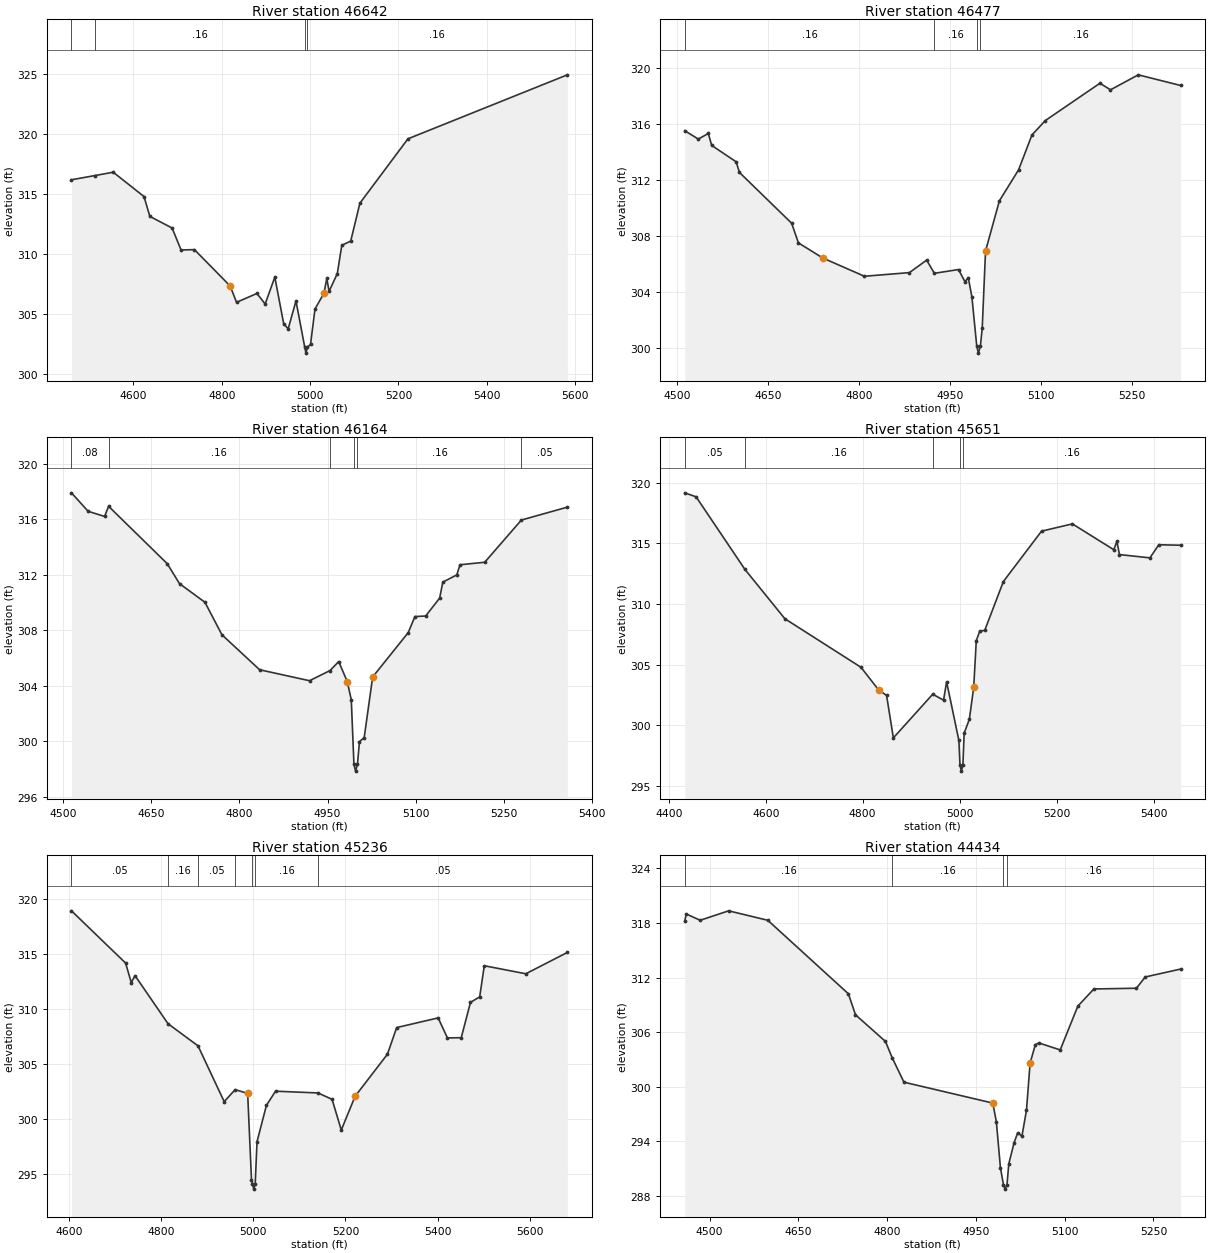
Type RM Length L Ch R = 1 ,46642   ,165,165,165
BEGIN DESCRIPTION:
UNT 0415 IN LACR 50.0
END DESCRIPTION:
XS GIS Cut Line= 3
      3663185.08     10679249.37      3662428.12     10679138.25
      3662070.51     10679134.78
#Sta/Elev= 30
  4459.8  316.21    4513  316.56  4554.3  316.84  4624.1  314.81  4637.2  313.16
  4687.7  312.19  4707.9  310.36  4738.2  310.39  4819.1  307.36  4833.5     306
  4879.7  306.74  4898.3  305.86  4920.2   308.1  4940.4   304.2  4950.5   303.8
  4968.1  306.12  4987.9  302.27  4990.7  301.77  4993.9  302.27    5001  302.49
  5011.1  305.44  5031.3  306.75  5037.9  307.99    5043  306.91  5061.7   308.4
  5071.8  310.75    5092   311.1  5112.8  314.26  5221.6  319.62  5582.5  324.95
#Mann= 4 ,-1 , 0
  4459.8     .08       0    4513     .16       0  4987.9     .04       0
  4993.9     .16       0
Bank Sta=4819.1,5031.3
XS Rating Curve= 0 ,0
Exp/Cntr=0.3,0.1

Type RM Length L Ch R = 1 ,46477   ,313,313,313
BEGIN DESCRIPTION:
Mapping XS c04c450f
END DESCRIPTION:
XS GIS Cut Line= 2
      3663139.96     10679221.61      3662396.83     10678877.82
#Sta/Elev= 30
  4512.2  315.53  4534.6  314.93  4551.2  315.33  4556.7  314.48  4597.1  313.31
  4602.6  312.55  4688.8  308.93  4699.9  307.53  4740.2  306.45  4808.9  305.15
  4883.2  305.41  4911.7   306.3  4924.4  305.36  4964.3  305.63  4974.9  304.76
  4980.4  305.05  4986.4  303.67  4994.4  300.17  4997.1  299.67  5000.4  300.17
  5003.4  301.43  5008.9  306.95  5031.8  310.53  5063.5  312.74  5085.5  315.22
  5107.6  316.25  5197.8  318.91  5215.2  318.44  5261.1  319.51    5331  318.75
#Mann= 4 ,-1 , 0
  4512.2     .16       0  4924.4     .16       0  4994.4     .07       0
  5000.4     .16       0
Bank Sta=4740.2,5008.9
XS Rating Curve= 0 ,0
Exp/Cntr=0.3,0.1

Type RM Length L Ch R = 1 ,46164   ,513,513,513
BEGIN DESCRIPTION:
UNT 0415 IN LACR 49.0
END DESCRIPTION:
XS GIS Cut Line= 3
      3663254.51      10679294.5      3662921.17     10678870.89
      3662639.88     10678752.82
#Sta/Elev= 30
    4514  317.89  4542.4  316.56  4570.4  316.19  4577.2  316.92    4677  312.79
  4697.9  311.35  4741.2  310.01  4770.1  307.67  4834.3  305.15  4919.2  304.36
    4954  305.09  4968.9  305.74  4983.4   304.3  4990.3  302.99  4994.8  298.35
  4997.6  297.85  5000.8  298.35  5004.2  299.97  5012.3  300.27  5026.7  304.63
  5087.3  307.83  5098.6  308.98  5116.9  309.02  5140.7  310.31  5146.1  311.46
  5169.9  311.98  5175.3  312.71  5217.4  312.89  5279.8  315.93  5358.1  316.86
#Mann= 6 ,-1 , 0
    4514     .08       0  4577.2     .16       0    4954     .16       0
  4994.8     .07       0  5000.8     .16       0  5279.8     .05       0
Bank Sta=4983.4,5026.7
XS Rating Curve= 0 ,0
Exp/Cntr=0.3,0.1

Type RM Length L Ch R = 1 ,45651   ,415,415,415
BEGIN DESCRIPTION:
UNT 0415 IN LACR 48.0
END DESCRIPTION:
XS GIS Cut Line= 3
      3663792.69     10678801.45      3663306.59     10678711.17
      3662810.11     10678530.63
#Sta/Elev= 30
    4433  319.17  4456.5  318.84  4557.3  312.85  4639.6  308.79  4796.5  304.79
  4832.8  302.93  4849.3  302.47  4863.3  298.97  4944.5  302.57  4966.8  302.08
  4973.1  303.59  4998.4  298.76  5000.7  296.73  5003.5  296.23  5006.7  296.73
  5009.3  299.36    5020   300.5    5029  303.14  5034.3  306.98  5041.2  307.74
  5051.9  307.85  5090.2  311.86  5168.9  316.01  5232.5  316.61  5317.9  314.48
  5324.3  315.17  5329.6  314.08  5392.4  313.81  5410.7  314.89  5455.7  314.85
#Mann= 5 ,-1 , 0
    4433     .05       0  4557.3     .16       0  4944.5     .05       0
  5000.7     .03       0  5006.7     .16       0
Bank Sta=4832.8,5029
XS Rating Curve= 0 ,0
Exp/Cntr=0.3,0.1

Type RM Length L Ch R = 1 ,45236   ,802,802,802
BEGIN DESCRIPTION:
Mapping XS 0de13c95
END DESCRIPTION:
XS GIS Cut Line= 3
      3663895.05     10678578.88      3663348.22     10678474.72
      3662829.55     10678455.19
#Sta/Elev= 30
  4605.7  318.89  4723.2  314.14  4735.4  312.37  4743.6     313  4815.2  308.63
  4880.2  306.62    4937  301.55  4960.7  302.64  4987.9   302.3  4996.2  294.45
  4998.3   294.1  5001.1   293.6  5004.3   294.1  5008.2  297.91  5028.6  301.21
  5048.4   302.5  5140.5  302.34    5171  301.76    5191  298.97    5221  302.04
  5291.1  305.86  5311.1  308.28  5401.1  309.16  5421.2  307.34  5451.2  307.36
  5471.2  310.57  5491.2  311.07  5501.2   313.9  5591.3  313.17  5681.4  315.11
#Mann= 7 ,-1 , 0
  4605.7     .05       0  4815.2     .16       0  4880.2     .05       0
  4960.7     .16       0  4998.3     .07       0  5004.3     .16       0
  5140.5     .05       0
Bank Sta=4987.9,5221
XS Rating Curve= 0 ,0
Exp/Cntr=0.3,0.1

Type RM Length L Ch R = 1 ,44434   ,239,239,239
BEGIN DESCRIPTION:
UNT 0415 IN LACR 47.0
END DESCRIPTION:
XS GIS Cut Line= 3
      3663674.67     10678023.66      3663209.37     10678162.56
      3662917.67      10678360.5
#Sta/Elev= 30
  4457.9  318.22  4460.6  318.99  4484.1   318.3  4532.1  319.34  4598.3   318.3
  4734.5  310.21  4746.5   307.9  4797.1  304.97  4808.6  303.16  4828.4  300.48
  4978.6  298.18  4984.6  296.12  4991.5  291.04  4996.6  289.21  4999.3  288.71
  5002.6  289.21  5005.6  291.49  5014.5   293.8  5020.6  294.91  5027.8  294.54
  5035.5  297.39  5041.6  302.58  5050.5  304.61  5056.5   304.8  5092.5  304.03
  5122.3  308.85  5149.4  310.74  5221.3  310.82  5236.2  312.06    5296  312.93
#Mann= 4 ,-1 , 0
  4457.9     .16       0  4808.6     .16       0  4996.6     .03       0
  5002.6     .16       0
Bank Sta=4978.6,5041.6
XS Rating Curve= 0 ,0
Exp/Cntr=0.3,0.1