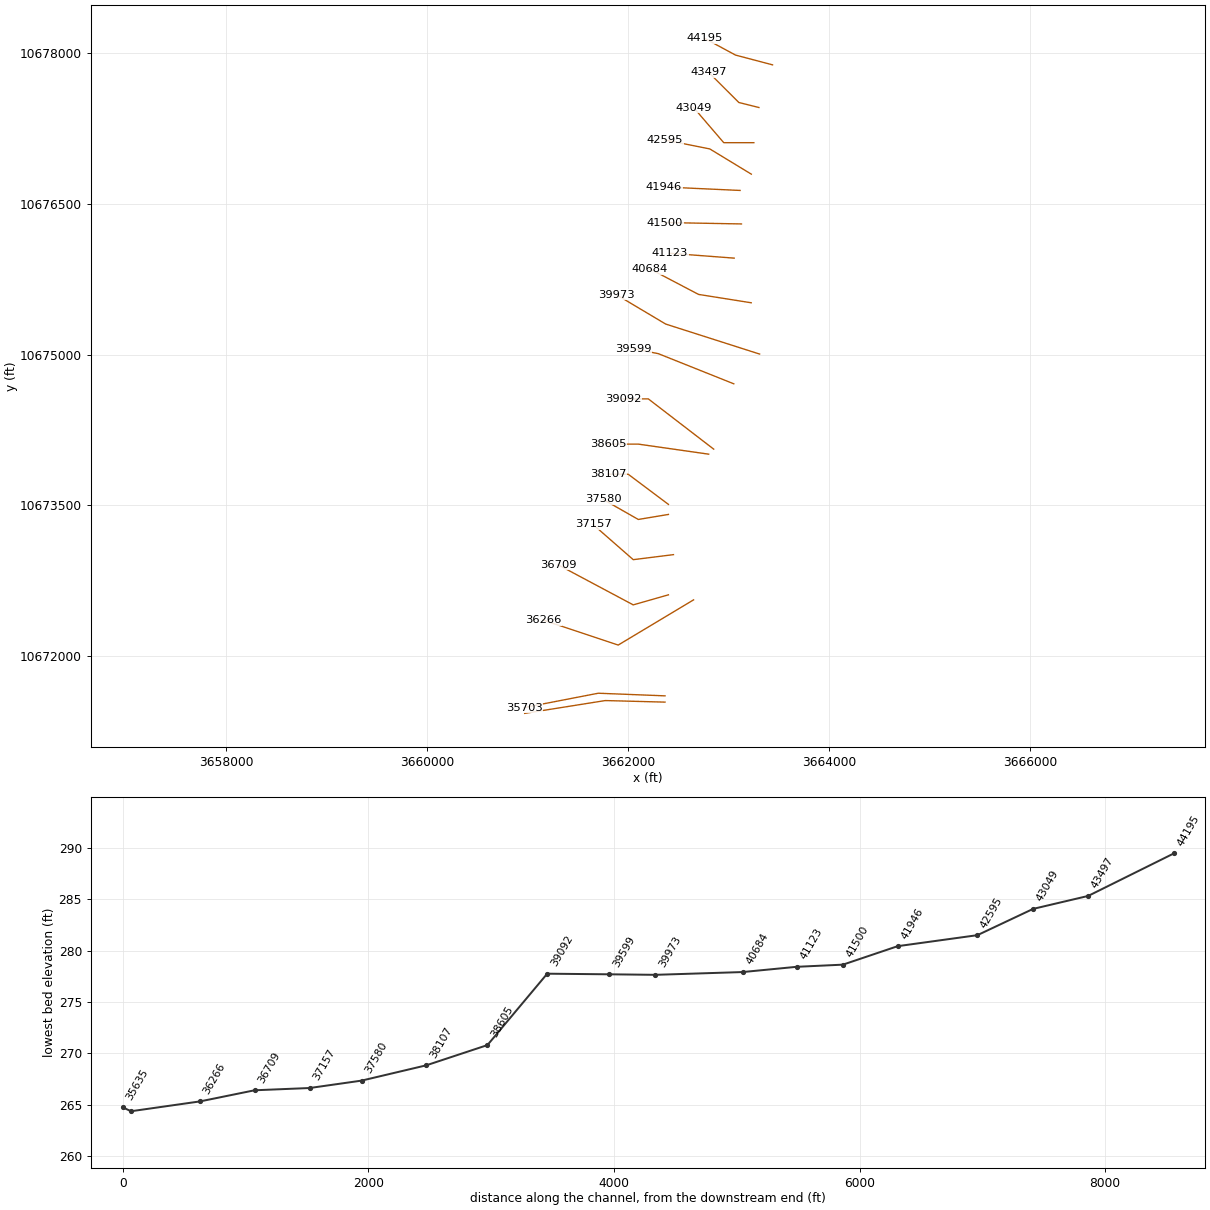
HEC-RAS study UNT 0415 IN LACR.prj: UNT 0415 IN LACR Base Level Engineering

--- UNT 0415 IN LACR.g01 (geometry) --- (continued)

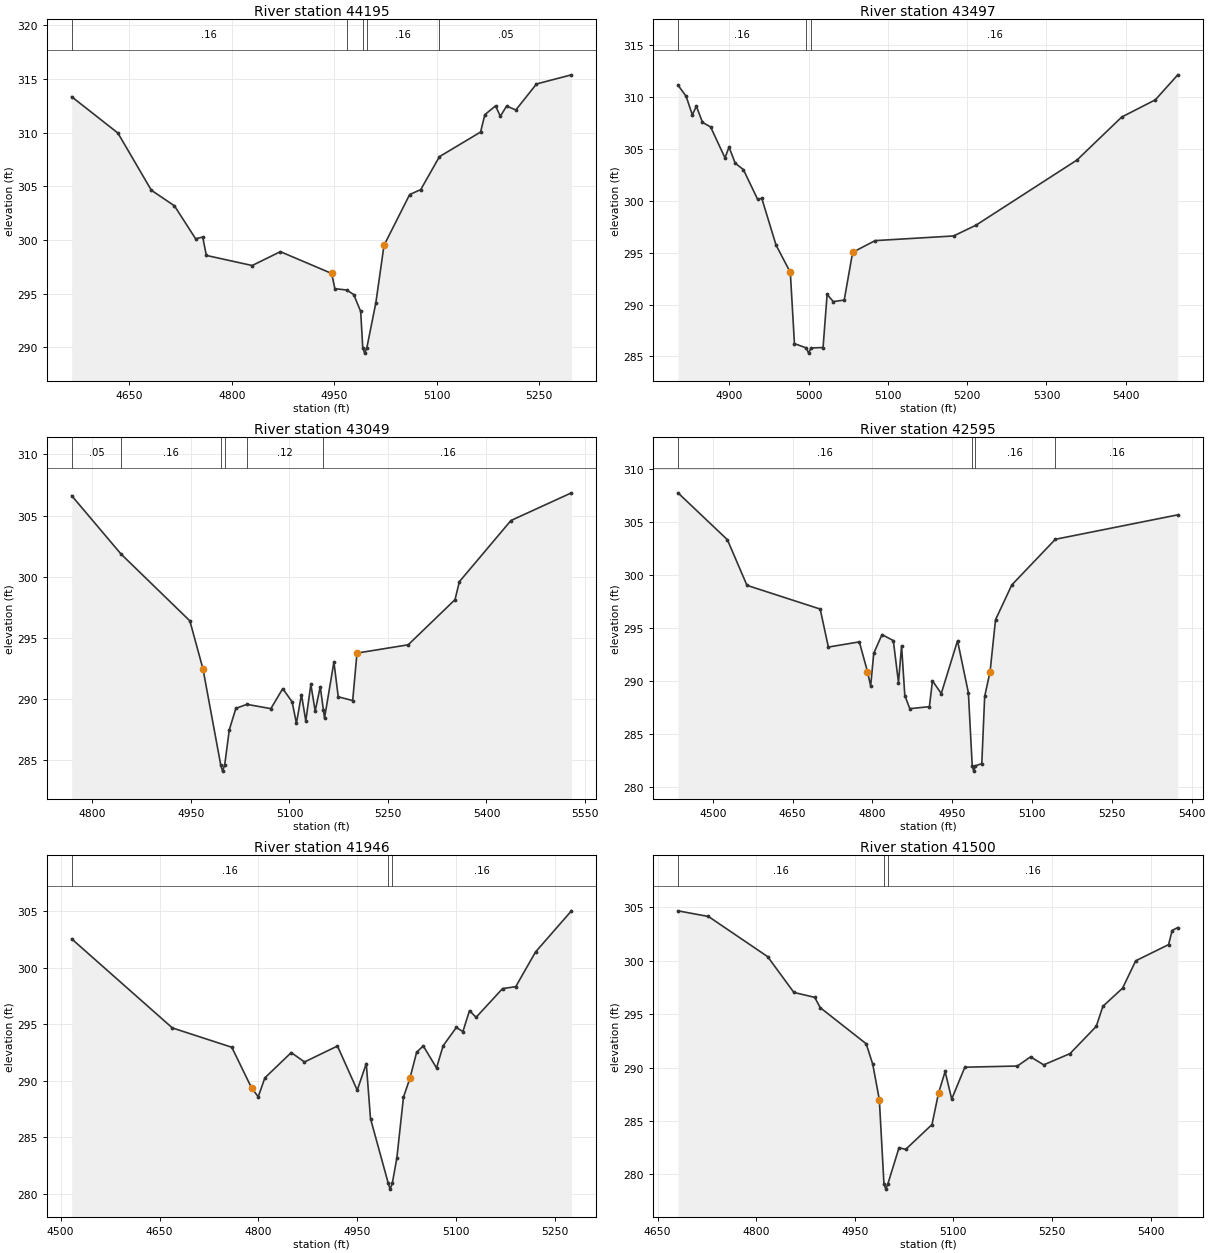
Type RM Length L Ch R = 1 ,44195   ,698,698,698
BEGIN DESCRIPTION:
UNT 0415 IN LACR 46.0
END DESCRIPTION:
XS GIS Cut Line= 3
       3663435.1     10677884.77      3663067.01       10677982.
        3662758.     10678148.66
#Sta/Elev= 30
  4565.4  313.34  4633.1  309.96  4682.1  304.63  4715.9  303.18  4746.9  300.11
  4757.3  300.27  4762.6  298.56  4829.7  297.62    4871  298.91  4946.1  296.88
  4950.8  295.46  4968.2  295.34  4978.4  294.91  4988.6  293.34  4991.6  289.96
  4994.4  289.46  4997.6  289.96  5010.8  294.15  5022.7  299.49  5060.3  304.23
  5076.5  304.69  5103.9  307.76  5164.1  310.05  5170.4  311.67    5186  312.49
  5193.1  311.52  5202.2  312.47  5215.8  312.11    5246  314.53  5297.2  315.38
#Mann= 5 ,-1 , 0
  4565.4     .16       0  4968.2     .16       0  4991.6     .07       0
  4997.6     .16       0  5103.9     .05       0
Bank Sta=4946.1,5022.7
XS Rating Curve= 0 ,0
Exp/Cntr=0.3,0.1

Type RM Length L Ch R = 1 ,43497   ,448,448,448
BEGIN DESCRIPTION:
UNT 0415 IN LACR 45.0
END DESCRIPTION:
XS GIS Cut Line= 3
      3663299.62     10677460.19      3663099.61     10677510.19
      3662799.63     10677810.17
#Sta/Elev= 30
  4835.2  311.17  4845.5  310.09  4853.3   308.3  4858.4  309.14  4866.1  307.58
  4876.4  307.13  4894.5  304.15  4899.6  305.19  4907.4  303.64  4917.7  303.02
  4935.7  300.15  4940.9  300.25  4958.9  295.74  4976.9  293.11  4982.1  286.24
  4997.1  285.82  4999.9  285.32  5003.1  285.82  5018.2  285.86  5023.3  290.98
  5031.1  290.29  5044.9  290.44  5055.5  295.04  5083.8  296.17  5182.8  296.62
  5211.1  297.66  5338.4  303.94  5394.9  308.09  5437.3  309.75  5465.6  312.16
#Mann= 3 ,-1 , 0
  4835.2     .16       0  4997.1     .07       0  5003.1     .16       0
Bank Sta=4976.9,5055.5
XS Rating Curve= 0 ,0
Exp/Cntr=0.3,0.1

Type RM Length L Ch R = 1 ,43049   ,454,454,454
BEGIN DESCRIPTION:
UNT 0415 IN LACR 44.0
END DESCRIPTION:
XS GIS Cut Line= 3
       3663249.6     10677110.19      3662949.61     10677110.19
      3662649.59     10677460.22
#Sta/Elev= 30
  4768.4  306.63  4843.5  301.85  4948.4  296.37  4968.4  292.42  4995.4  284.56
  4998.1  284.06  5001.4  284.56  5008.4  287.44  5018.4   289.2  5035.2  289.53
  5071.7  289.18  5089.8  290.82  5104.1  289.73  5110.6  287.98  5118.3  290.33
  5124.9  288.17  5132.6  291.16  5139.2  288.98  5146.9  290.98  5151.7  289.07
  5153.4   288.4  5167.7     293  5174.3  290.15  5196.3  289.84  5202.8  293.73
  5280.8  294.41  5352.1  298.11  5358.7  299.58  5437.2  304.59  5529.4  306.86
#Mann= 6 ,-1 , 0
  4768.4     .05       0  4843.5     .16       0  4995.4     .07       0
  5001.4     .16       0  5035.2     .12       0  5151.7     .16       0
Bank Sta=4968.4,5202.8
XS Rating Curve= 0 ,0
Exp/Cntr=0.3,0.1

Type RM Length L Ch R = 1 ,42595   ,649,649,649
BEGIN DESCRIPTION:
UNT 0415 IN LACR 43.0
END DESCRIPTION:
XS GIS Cut Line= 3
      3663223.92     10676796.87      3662810.99     10677048.08
      3662363.66     10677137.39
#Sta/Elev= 30
  4434.5  307.79  4527.4  303.36  4564.2  299.05  4701.8  296.81  4717.2  293.22
  4775.4  293.71  4790.7   290.9  4796.7  289.54  4802.5  292.63    4818   294.4
  4839.3  293.83    4849  289.87  4854.8  293.34  4860.9  288.64  4870.3   287.4
  4907.1  287.59  4912.9  290.03  4929.4  288.83    4960  293.82  4980.4   288.9
  4987.6     282  4990.4   281.5  4993.6     282  5005.6  282.21    5011  288.55
  5021.2  290.91  5031.4   295.8    5062  299.09  5143.8   303.4    5374  305.71
#Mann= 4 ,-1 , 0
  4434.5     .16       0  4987.6     .07       0  4993.6     .16       0
  5143.8     .16       0
Bank Sta=4790.7,5021.2
XS Rating Curve= 0 ,0
Exp/Cntr=0.3,0.1

Type RM Length L Ch R = 1 ,41946   ,446,446,446
BEGIN DESCRIPTION:
UNT 0415 IN LACR 42.0
END DESCRIPTION:
XS GIS Cut Line= 2
      3663112.19     10676634.78      3662355.19      10676669.5
#Sta/Elev= 30
  4516.8  302.57  4669.5  294.69  4759.6  292.98  4789.7  289.37  4799.7   288.6
  4809.7  290.27  4849.7  292.51  4869.8  291.68  4919.8  293.09  4949.8  289.18
  4963.5  291.54  4969.9  286.67  4996.9  280.93  4999.6  280.43  5002.9  280.93
  5009.9   283.2  5019.9  288.57  5029.9  290.28  5039.9  292.55  5049.9   293.1
    5070  291.15    5080  293.11    5100  294.73    5110  294.37    5120  296.22
    5130  295.63  5170.1  298.17  5190.1  298.34  5220.1  301.41  5274.6  305.05
#Mann= 3 ,-1 , 0
  4516.8     .16       0  4996.9     .07       0  5002.9     .16       0
Bank Sta=4789.7,5029.9
XS Rating Curve= 0 ,0
Exp/Cntr=0.3,0.1

Type RM Length L Ch R = 1 ,41500   ,377,377,377
BEGIN DESCRIPTION:
UNT 0415 IN LACR 41.0
END DESCRIPTION:
XS GIS Cut Line= 2
        3663126.     10676301.45      3662365.63     10676315.34
#Sta/Elev= 30
  4680.9  304.65  4727.3  304.12  4817.3  300.37  4857.3  297.02    4889  296.56
  4897.3   295.6  4967.3  292.22  4977.3   290.3  4987.3  286.99  4994.3  279.13
  4997.1  278.63  5000.3  279.13  5017.3  282.51  5027.3  282.34  5067.4  284.67
  5077.4  287.62  5087.4  289.63  5097.4  287.05  5117.4  290.03  5197.4  290.14
  5217.4     291  5237.4  290.25  5277.4   291.3  5317.4  293.85  5327.4  295.72
  5357.4  297.42  5377.4  299.98  5427.4  301.49  5432.8  302.81  5441.4  303.09
#Mann= 3 ,-1 , 0
  4680.9     .16       0  4994.3     .07       0  5000.3     .16       0
Bank Sta=4987.3,5077.4
XS Rating Curve= 0 ,0
Exp/Cntr=0.3,0.1

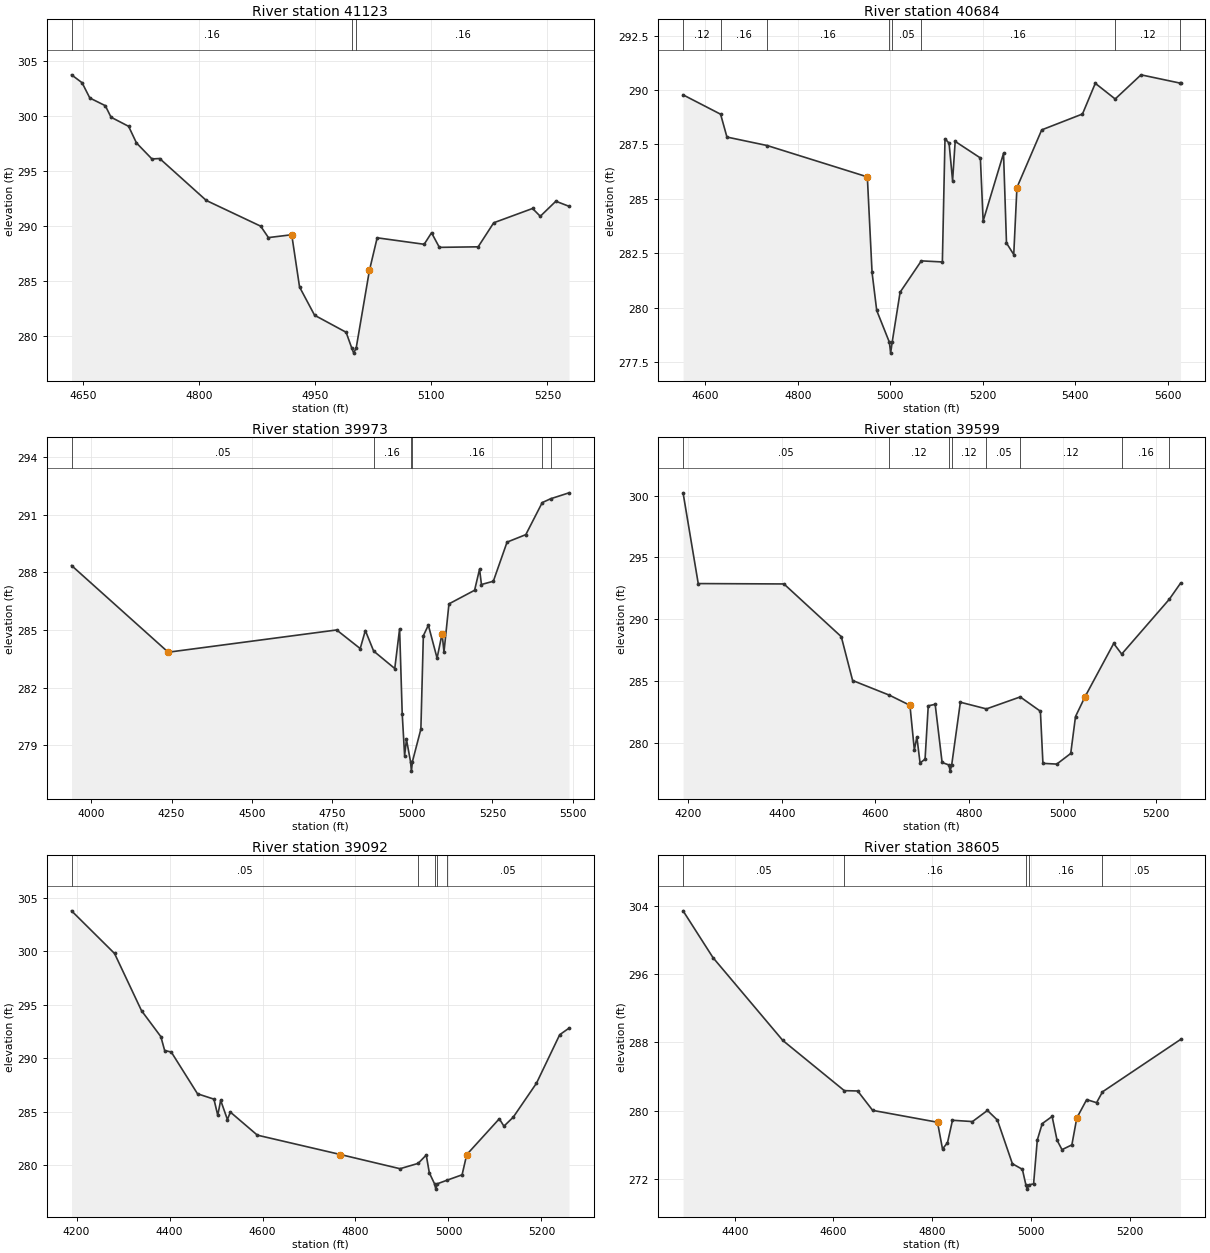
Type RM Length L Ch R = 1 ,41123   ,439,439,439
BEGIN DESCRIPTION:
UNT 0415 IN LACR 40.0
END DESCRIPTION:
XS GIS Cut Line= 2
      3663053.13     10675961.17      3662412.66     10676009.64
#Sta/Elev= 30
  4635.5  303.76  4649.1  303.04  4659.1  301.65  4679.1  300.95  4686.5   299.9
  4709.2  299.07  4719.3  297.56  4739.3   296.1  4749.3  296.14  4809.5  292.32
  4879.7  289.98  4889.7  288.94  4919.8   289.2  4929.9  284.44  4949.3  281.87
    4990  280.32  4997.1  278.92  4999.8  278.42  5003.1  278.92  5020.1  285.95
  5030.1  288.92  5090.8  288.33  5100.3  289.38  5110.4  288.05  5160.5   288.1
  5180.6  290.29  5230.7  291.59  5240.7  290.88  5260.8  292.25  5277.8  291.79
#Mann= 3 ,-1 , 0
  4635.5     .16       0  4997.1     .07       0  5003.1     .16       0
Bank Sta=4919.8,5020.1
XS Rating Curve= 0 ,0
Exp/Cntr=0.3,0.1

Type RM Length L Ch R = 1 ,40684   ,711,711,711
BEGIN DESCRIPTION:
UNT 0415 IN LACR 39.0
END DESCRIPTION:
XS GIS Cut Line= 3
       3663223.3     10675516.72      3662698.95     10675600.06
      3662216.29     10675853.54
#Sta/Elev= 30
  4551.7  289.78  4632.9  288.89  4646.6  287.84  4733.7  287.45  4950.3  286.01
  4960.5  281.62  4970.6  279.87    4998  278.41  5000.7  277.91    5004  278.41
  5021.2  280.71  5067.1  282.15  5112.6   282.1  5118.3  287.76  5127.1  287.56
  5134.7  285.83  5140.3  287.64  5194.8  286.88  5200.8  283.98  5244.9  287.09
  5251.3  282.97    5267  282.44  5273.9  285.52  5327.5  288.17  5415.7   288.9
  5443.4  290.31  5486.4  289.59  5542.3   290.7  5626.7  290.32  5627.8  290.32
#Mann= 8 ,-1 , 0
  4551.7     .12       0  4632.9     .16       0  4733.7     .16       0
    4998     .03       0    5004     .05       0  5067.1     .16       0
  5486.4     .12       0  5626.7     .16       0
Bank Sta=4950.3,5273.9
XS Rating Curve= 0 ,0
Exp/Cntr=0.3,0.1

Type RM Length L Ch R = 1 ,39973   ,374,374,374
BEGIN DESCRIPTION:
UNT 0415 IN LACR 38.0
END DESCRIPTION:
XS GIS Cut Line= 3
      3663306.63      10675006.3      3662372.56     10675304.92
      3661882.99     10675596.58
#Sta/Elev= 30
  3938.3  288.36  4239.6  283.84  4764.6     285    4838  284.03    4854  284.97
  4879.9   283.9  4945.7  282.99  4960.8  285.06  4968.9  280.64  4976.4  278.45
  4982.2  279.29  4994.8  278.14  4997.6  277.64  5000.8  278.14  5027.1  279.83
  5034.8   284.7  5050.4  285.25  5077.6  283.53  5093.2  284.81  5099.1  283.85
  5114.6  286.36  5194.5  287.07    5210  288.17  5215.9  287.37  5252.9  287.54
  5295.7  289.58  5354.1  289.97  5405.3  291.64  5431.4  291.84  5488.8  292.15
#Mann= 6 ,-1 , 0
  3938.3     .05       0  4879.9     .16       0  4994.8     .07       0
  5000.8     .16       0  5405.3     .05       0  5431.4     .12       0
Bank Sta=4239.6,5093.2
XS Rating Curve= 0 ,0
Exp/Cntr=0.3,0.1

Type RM Length L Ch R = 1 ,39599   ,507,507,507
BEGIN DESCRIPTION:
UNT 0415 IN LACR 37.0
END DESCRIPTION:
XS GIS Cut Line= 3
      3663049.66     10674710.17      3662299.61     10675010.19
      3662049.58     10675060.19
#Sta/Elev= 30
  4189.3  300.23  4221.7  292.88  4404.8  292.85  4527.3  288.58  4551.5  285.03
  4630.2  283.84    4674  283.02  4683.4  279.41  4688.8  280.46  4695.6  278.35
  4706.3  278.66  4713.1  282.98  4727.9   283.1  4742.7  278.39  4757.2  278.19
  4759.9  277.69  4763.2  278.19  4781.7  283.27  4837.4  282.73  4909.6   283.7
  4952.7  282.54  4958.1  278.32  4987.7  278.26  5017.5  279.12  5027.7  282.11
  5048.1  283.72  5109.3  288.03  5126.4  287.17  5228.1  291.61  5252.1  292.91
#Mann= 8 ,-1 , 0
  4189.3     .05       0  4630.2     .12       0  4757.2     .07       0
  4763.2     .12       0  4837.4     .05       0  4909.6     .12       0
  5126.4     .16       0  5228.1     .12       0
Bank Sta=4674,5048.1
XS Rating Curve= 0 ,0
Exp/Cntr=0.3,0.1

Type RM Length L Ch R = 1 ,39092   ,487,487,487
BEGIN DESCRIPTION:
UNT 0415 IN LACR 36.0
END DESCRIPTION:
XS GIS Cut Line= 3
      3662849.64     10674060.16      3662199.61     10674560.19
      3661949.61     10674560.19
#Sta/Elev= 30
  4189.2  303.79  4281.7   299.8  4339.7  294.45  4381.3  292.02  4389.5  290.72
  4403.7  290.58  4460.2  286.67  4495.5  286.17  4503.7  284.66    4510  286.06
  4524.5  284.26  4530.8  284.96  4588.9   282.8  4767.4  280.99  4895.8  279.66
  4934.8  280.16  4952.2  280.94  4958.8  279.28    4970  278.25  4972.8  277.75
    4976  278.25  4997.3  278.59  5029.3  279.09  5039.3  280.98  5109.3  284.33
  5119.3  283.64  5139.3  284.48  5189.3  287.66  5239.3   292.2  5259.3  292.81
#Mann= 5 ,-1 , 0
  4189.2     .05       0  4934.8     .16       0    4970     .03       0
    4976     .16       0  4997.3     .05       0
Bank Sta=4767.4,5039.3
XS Rating Curve= 0 ,0
Exp/Cntr=0.3,0.1

Type RM Length L Ch R = 1 ,38605   ,498,498,498
BEGIN DESCRIPTION:
UNT 0415 IN LACR 35.0
END DESCRIPTION:
XS GIS Cut Line= 3
      3662799.57     10674010.19      3662099.61     10674110.19
      3661799.58     10674110.19
#Sta/Elev= 30
  4295.5  303.38  4356.1   297.9  4497.5   288.2  4621.9  282.33    4649  282.29
  4679.3  280.02  4810.6  278.63  4820.7   275.5  4830.8  276.23  4840.9  278.86
  4881.4  278.71  4911.7  280.01  4931.9  278.88  4962.2  273.77  4982.4  273.12
  4989.5   271.3  4992.2   270.8  4995.5   271.3  5005.1  271.41  5012.6  276.55
  5022.6  278.47  5042.6  279.31  5052.6  276.53  5062.6  275.42  5082.6  275.98
  5092.6  279.13  5112.6  281.28  5132.6  280.92  5144.6  282.19  5302.6  288.32
#Mann= 5 ,-1 , 0
  4295.5     .05       0  4621.9     .16       0  4989.5     .07       0
  4995.5     .16       0  5144.6     .05       0
Bank Sta=4810.6,5092.6
XS Rating Curve= 0 ,0
Exp/Cntr=0.3,0.1

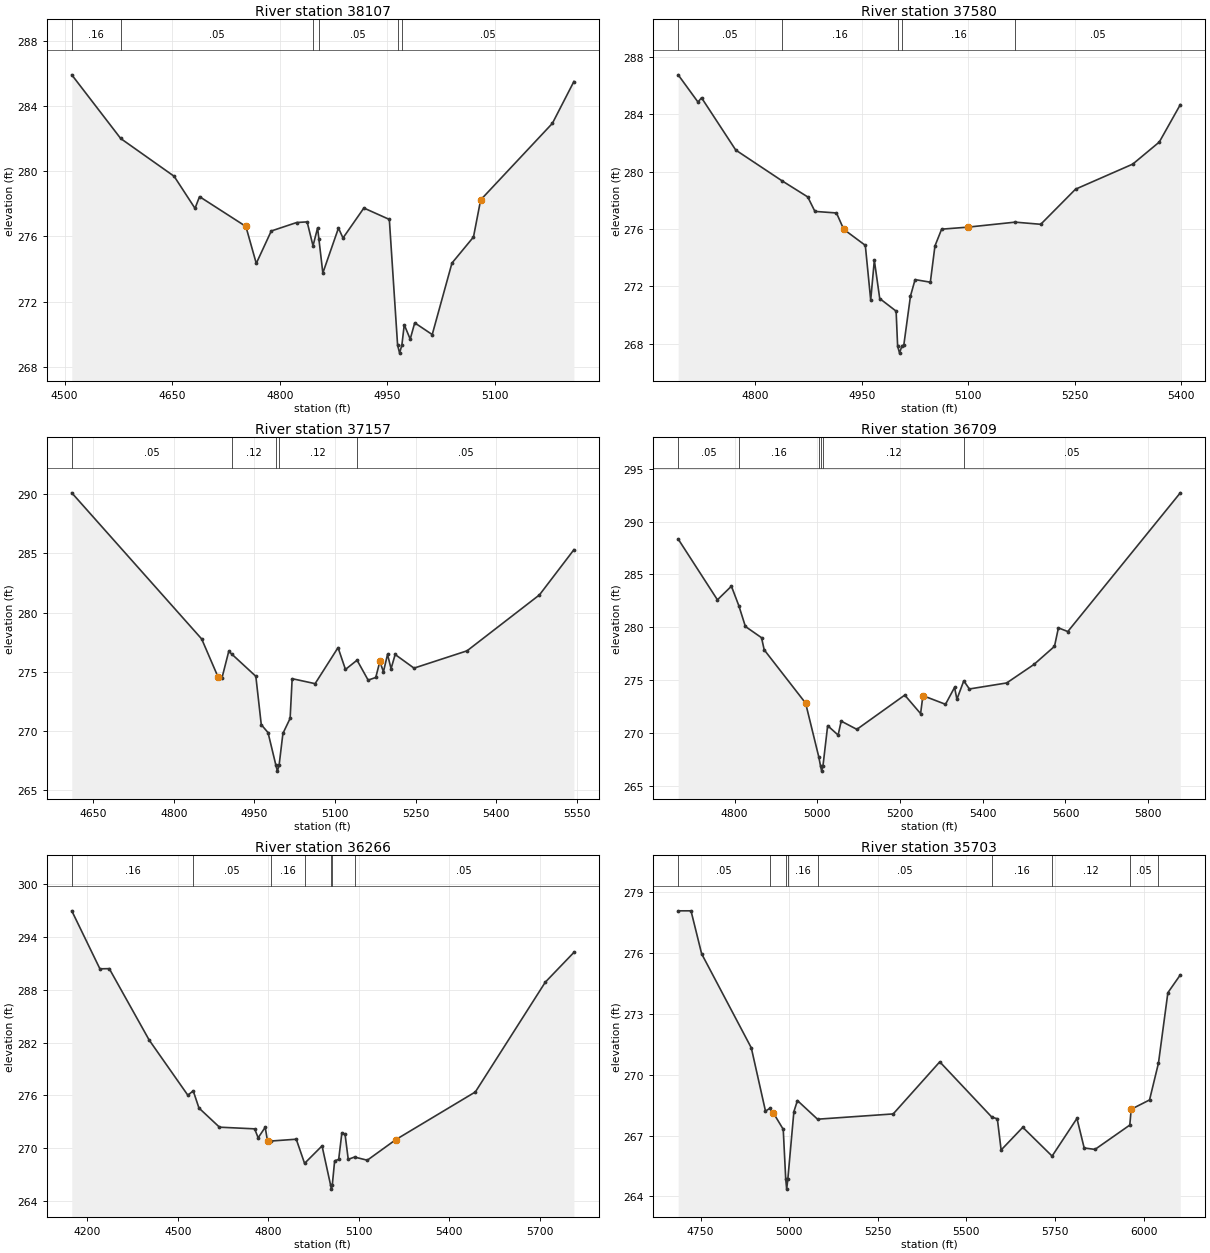
Type RM Length L Ch R = 1 ,38107   ,527,527,527
BEGIN DESCRIPTION:
UNT 0415 IN LACR 34.0
END DESCRIPTION:
XS GIS Cut Line= 3
      3662399.57     10673510.22      3661999.61     10673810.19
      3661799.56     10673810.19
#Sta/Elev= 30
  4509.9  285.92  4578.1  282.01  4652.6  279.69  4681.7  277.72    4688  278.44
  4752.6  276.61  4767.1  274.34    4788  276.33  4823.4  276.85    4838  276.89
  4846.2  275.42  4852.6  276.52  4854.4  275.84  4859.9  273.75  4881.7  276.51
    4888   275.9  4917.1  277.74  4952.6  277.04  4964.1  269.33  4966.9  268.83
  4970.1  269.33  4973.4  270.57  4981.7  269.69    4988  270.69  5012.4  269.97
  5039.9  274.36  5069.9  275.96  5079.9  278.24  5179.9  282.94  5209.9  285.51
#Mann= 6 ,-1 , 0
  4509.9     .16       0  4578.1     .05       0  4846.2     .16       0
  4854.4     .05       0  4964.1     .03       0  4970.1     .05       0
Bank Sta=4752.6,5079.9
XS Rating Curve= 0 ,0
Exp/Cntr=0.3,0.1

Type RM Length L Ch R = 1 ,37580   ,423,423,423
BEGIN DESCRIPTION:
UNT 0415 IN LACR 33.0
END DESCRIPTION:
XS GIS Cut Line= 3
      3662399.61     10673410.19      3662099.61     10673360.19
      3661749.57     10673560.21
#Sta/Elev= 30
  4691.5  286.76  4719.4  284.86  4724.4  285.16  4772.6  281.51  4837.6  279.37
    4874  278.24  4884.1  277.23  4914.5  277.12  4924.7  275.98  4955.1  274.86
  4962.7  271.04  4967.8  273.82  4975.4  271.15  4998.5  270.27  5000.6  267.84
  5003.3  267.34  5006.6  267.84  5009.3  267.89  5018.7  271.32  5025.2  272.47
  5046.7  272.29  5053.2  274.82  5062.6  275.99  5099.3  276.13  5166.2  276.48
  5202.2  276.33  5251.2  278.78  5331.8  280.53  5369.2  282.07  5398.8  284.68
#Mann= 5 ,-1 , 0
  4691.5     .05       0  4837.6     .16       0  5000.6     .07       0
  5006.6     .16       0  5166.2     .05       0
Bank Sta=4924.7,5099.3
XS Rating Curve= 0 ,0
Exp/Cntr=0.3,0.1

Type RM Length L Ch R = 1 ,37157   ,448,448,448
BEGIN DESCRIPTION:
UNT 0415 IN LACR 32.0
END DESCRIPTION:
XS GIS Cut Line= 3
      3662449.57     10673010.18      3662049.61     10672960.19
       3661649.6      10673310.2
#Sta/Elev= 30
  4609.9   290.1  4851.7  277.77    4882  274.58  4889.5  274.49  4902.1  276.73
  4907.8  276.49  4952.5  274.62  4962.6  270.54  4975.2  269.87  4989.8  267.12
  4992.6  266.62  4995.8  267.12  5002.9   269.8  5016.3  271.07  5020.1  274.42
  5062.8     274  5105.5  277.04  5119.3   275.2  5140.9  275.98  5161.5   274.3
  5175.7  274.52  5183.3  275.88    5190     275  5197.6  276.47  5204.2  275.26
  5211.8  276.46  5246.9  275.31  5345.6  276.77  5480.4  281.49  5544.5   285.3
#Mann= 5 ,-1 , 0
  4609.9     .05       0  4907.8     .12       0  4989.8     .07       0
  4995.8     .12       0  5140.9     .05       0
Bank Sta=4882,5183.3
XS Rating Curve= 0 ,0
Exp/Cntr=0.3,0.1

Type RM Length L Ch R = 1 ,36709   ,443,443,443
BEGIN DESCRIPTION:
UNT 0415 IN LACR 31.0
END DESCRIPTION:
XS GIS Cut Line= 3
      3662399.61     10672610.19      3662049.61     10672510.19
      3661299.61     10672910.19
#Sta/Elev= 30
  4663.6  288.35  4758.5   282.6  4792.3  283.89  4810.3  282.04  4826.1  280.08
  4865.1  279.02  4871.6  277.87  4971.7  272.83  5003.5  267.75  5007.7   266.9
  5010.5   266.4  5013.7   266.9    5025   270.7  5050.3  269.81  5057.7  271.13
  5095.6  270.35  5211.4  273.59  5249.7  271.84  5255.3  273.54  5309.9  272.72
  5331.8  274.32  5337.5   273.2  5354.1  274.94  5367.6  274.17  5457.9  274.74
  5523.8  276.49  5573.4   278.2  5582.9  279.95  5605.6   279.6  5877.6  292.72
#Mann= 6 ,-1 , 0
  4663.6     .05       0  4810.3     .16       0  5003.5     .12       0
  5007.7     .07       0  5013.7     .12       0  5354.1     .05       0
Bank Sta=4971.7,5255.3
XS Rating Curve= 0 ,0
Exp/Cntr=0.3,0.1

Type RM Length L Ch R = 1 ,36266   ,563,563,563
BEGIN DESCRIPTION:
UNT 0415 IN LACR 30.0
END DESCRIPTION:
XS GIS Cut Line= 3
      3662649.65     10672560.21      3661899.61     10672110.19
      3661149.57      10672360.2
#Sta/Elev= 30
  4148.1  296.99  4241.4  290.39  4272.5  290.41  4404.7  282.29    4533  276.01
  4550.9   276.5  4569.9  274.55  4637.9  272.37  4754.6  272.18  4766.2  271.16
  4789.6  272.36  4797.3  270.79  4807.4  270.79  4892.6     271  4920.2  268.25
  4978.1  270.24  5006.2  265.82  5008.9  265.32  5012.2  265.82  5019.9  268.54
  5033.3   268.7  5043.9  271.73  5054.4  271.57    5065  268.71  5085.8  268.97
  5128.2  268.61  5223.1  270.96  5486.6  276.38  5718.5  288.87  5813.4  292.26
#Mann= 7 ,-1 , 0
  4148.1     .16       0  4550.9     .05       0  4807.4     .16       0
  4920.2     .12       0  5006.2     .07       0  5012.2     .12       0
  5085.8     .05       0
Bank Sta=4797.3,5223.1
XS Rating Curve= 0 ,0
Exp/Cntr=0.3,0.1

Type RM Length L Ch R = 1 ,35703   ,68,68,68
BEGIN DESCRIPTION:
Mapping XS 64f2c818
END DESCRIPTION:
XS GIS Cut Line= 3
      3662365.74     10671604.83      3661701.64     10671630.88
      3660963.36      10671487.9
#Sta/Elev= 30
    4687  278.09  4723.2  278.09  4753.2  275.97  4893.3  271.33  4933.3  268.21
  4945.1  268.34  4954.8  268.14  4983.4  267.31  4990.4  264.86  4993.1  264.36
  4996.4  264.86  5013.4  268.18  5023.4  268.73  5080.2  267.81  5293.6  268.07
    5425  270.64    5572  267.91  5587.4  267.83  5598.1  266.29  5659.2  267.41
  5741.9  265.99    5812  267.85  5832.4  266.39    5863  266.32  5961.1  267.52
    5965   268.3  6016.8  268.76    6042  270.58  6068.5  274.05  6103.6  274.93
#Mann= 9 ,-1 , 0
    4687     .05       0  4945.1     .16       0  4990.4     .07       0
  4996.4     .16       0  5080.2     .05       0    5572     .16       0
  5741.9     .12       0  5961.1     .05       0    6042     .08       0
Bank Sta=4954.8,5965
XS Rating Curve= 0 ,0
Exp/Cntr=0.3,0.1

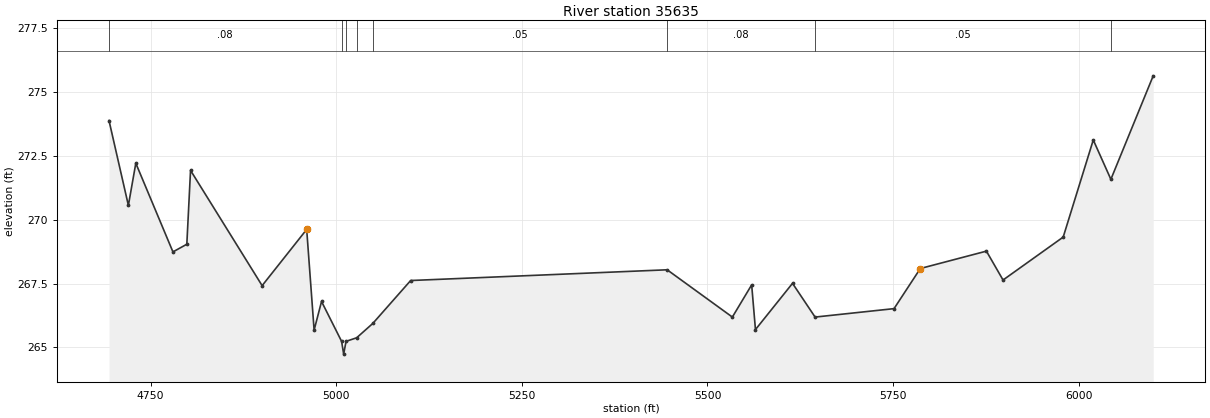
Type RM Length L Ch R = 1 ,35635   ,100,100,100
BEGIN DESCRIPTION:
UNT 0415 IN LACR 29.0
END DESCRIPTION:
XS GIS Cut Line= 3
      3662365.71     10671542.33      3661771.96     10671557.96
       3660969.9     10671430.36
#Sta/Elev= 30
  4694.1  273.88  4720.2  270.56  4730.2  272.21  4780.2  268.74  4798.9  269.04
  4803.9  271.93  4900.3  267.42  4960.3  269.62  4970.3  265.68  4980.3   266.8
  5007.3  265.24  5010.1  264.74  5013.3  265.24  5027.6  265.38  5049.3  265.94
  5100.3  267.62  5445.7  268.04  5533.5  266.19  5559.5  267.45  5564.6   265.7
  5614.5  267.51  5644.9  266.19  5751.2  266.52  5786.6  268.09  5875.6  268.77
    5898  267.64    5979  269.32  6019.5  273.12  6043.2  271.58  6100.2  275.63
#Mann= 8 ,-1 , 0
  4694.1     .08       0  5007.3     .07       0  5013.3     .08       0
  5027.6     .16       0  5049.3     .05       0  5445.7     .08       0
  5644.9     .05       0  6043.2     .08       0
Bank Sta=4960.3,5786.6
XS Rating Curve= 0 ,0
Exp/Cntr=0.3,0.1