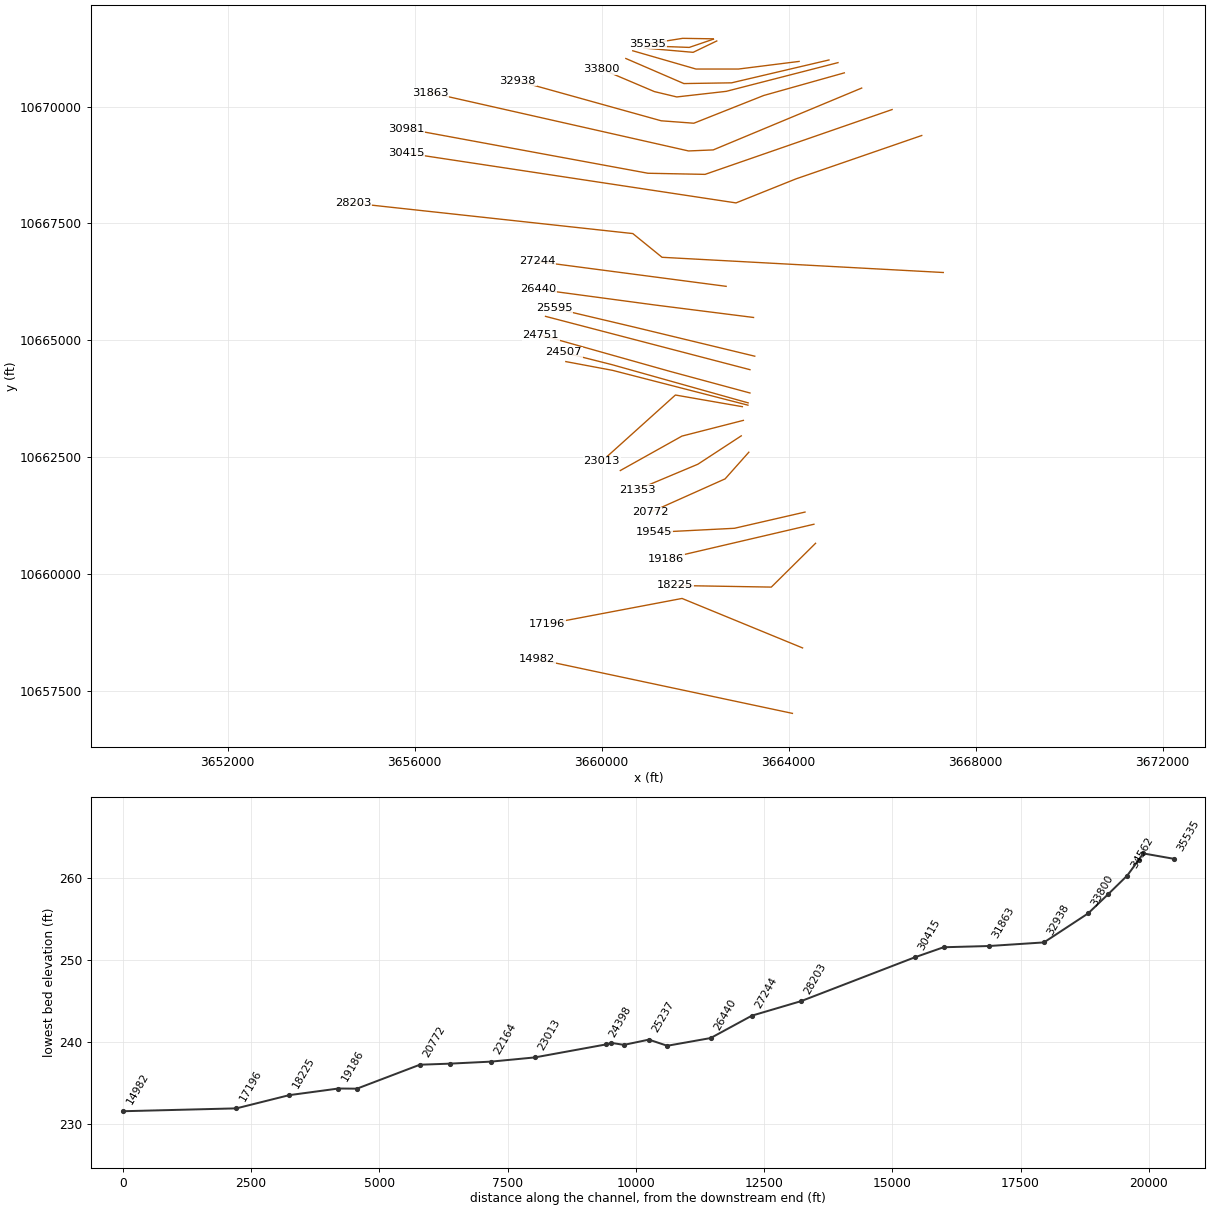
HEC-RAS study UNT 0415 IN LACR.prj: UNT 0415 IN LACR Base Level Engineering

--- UNT 0415 IN LACR.g01 (geometry) --- (continued)

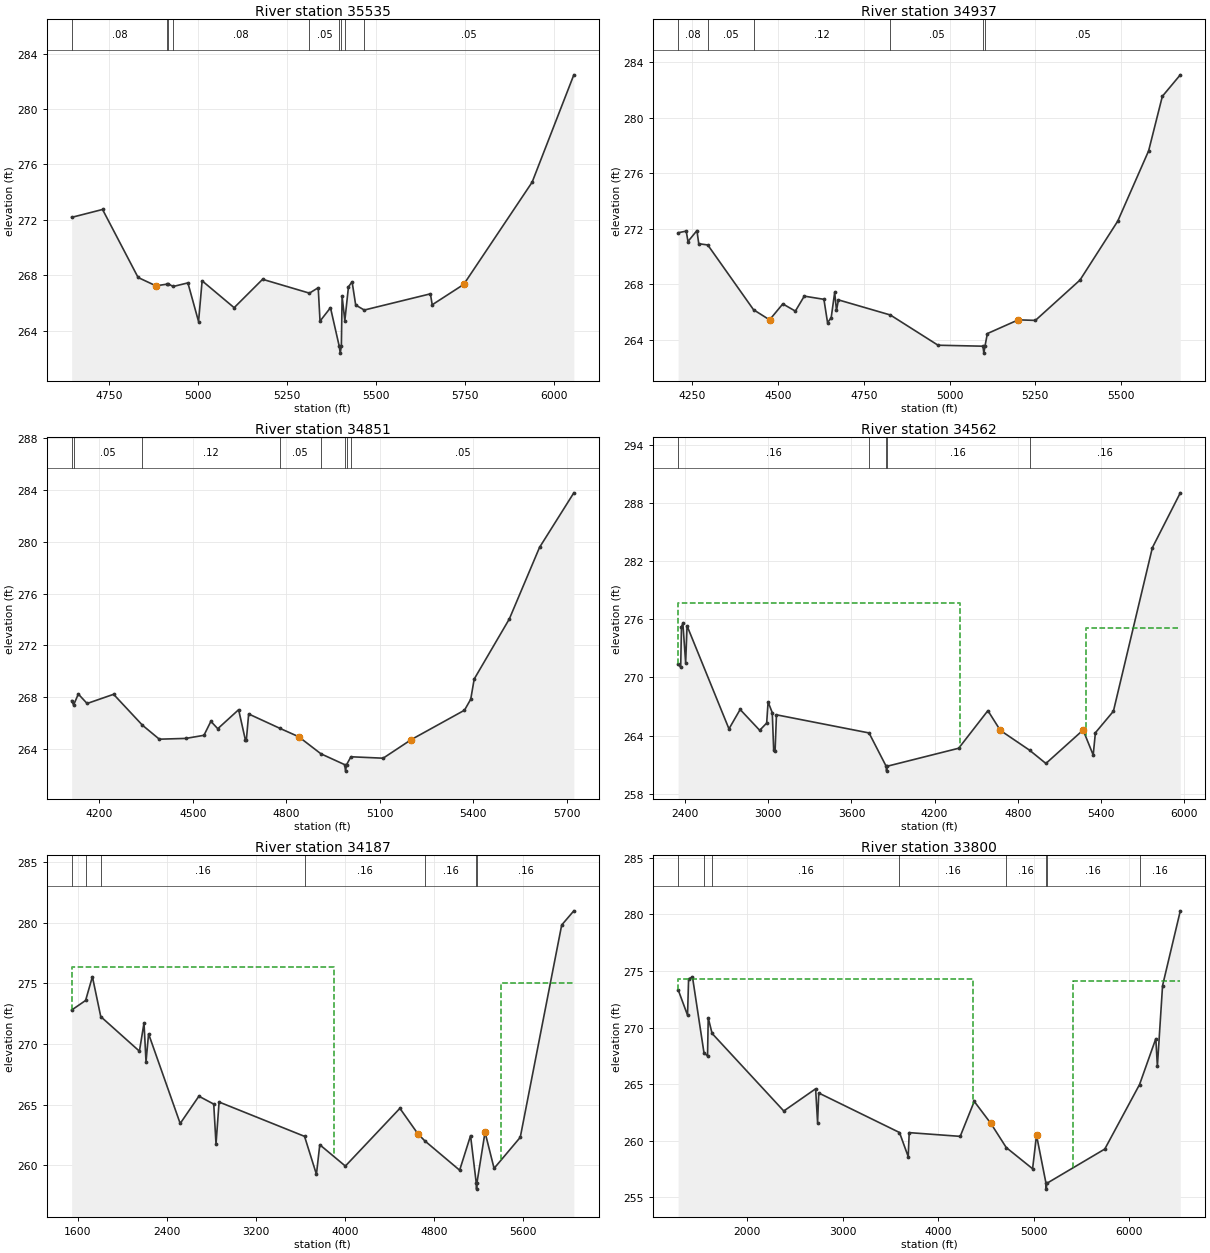
Type RM Length L Ch R = 1 ,35535   ,598,598,598
BEGIN DESCRIPTION:
Mapping XS d5a1a99b
END DESCRIPTION:
XS GIS Cut Line= 3
      3662386.51     10671451.19      3661732.89      10671461.6
      3660983.79     10671341.96
#Sta/Elev= 30
  4643.9  272.18  4730.8  272.75  4830.8  267.84  4880.8  267.24  4912.7  267.36
  4915.8  267.38  4929.3  267.19  4970.8  267.45  5000.8  264.66  5010.8   267.6
  5100.9  265.66  5180.9  267.71  5312.6  266.71  5337.3   267.1  5342.4  264.69
  5371.8  265.66  5396.4  262.88  5399.2  262.38  5402.4  262.88  5404.5  266.47
  5412.2  264.73  5422.4  267.17  5432.6  267.53  5442.7  265.85  5466.8  265.49
  5652.8  266.66  5657.9  265.87  5746.5  267.34  5938.9  274.72  6056.2  282.47
#Mann= 9 ,-1 , 0
  4643.9     .08       0  4912.7     .05       0  4915.8     .12       0
  4929.3     .08       0  5312.6     .05       0  5396.4     .07       0
  5402.4     .05       0  5412.2     .08       0  5466.8     .05       0
Bank Sta=4880.8,5746.5
XS Rating Curve= 0 ,0
Exp/Cntr=0.3,0.1

Type RM Length L Ch R = 1 ,34937   ,86,86,86
BEGIN DESCRIPTION:
Mapping XS 04354628
END DESCRIPTION:
XS GIS Cut Line= 3
      3662392.08     10671444.45      3661873.88     10671267.38
      3660957.23     10671301.23
#Sta/Elev= 30
  4208.2  271.72  4231.8  271.84    4237  271.09  4263.1  271.88  4268.4  270.93
  4294.7  270.84  4428.2  266.17    4475  265.44  4513.6  266.59  4550.2  266.07
  4576.2  267.15  4633.5  266.92  4644.1  265.24  4654.7  265.59  4664.9  267.42
  4670.2  266.12  4675.8  266.88  4827.3  265.79  4966.4  263.61  5097.3  263.54
  5100.1  263.04  5103.3  263.54  5110.3  264.45  5200.4  265.44  5250.4   265.4
  5380.5  268.31  5490.6  272.56  5580.7  277.63  5620.7  281.56  5673.1  283.11
#Mann= 6 ,-1 , 0
  4208.2     .08       0  4294.7     .05       0  4428.2     .12       0
  4827.3     .05       0  5097.3     .03       0  5103.3     .05       0
Bank Sta=4475,5200.4
XS Rating Curve= 0 ,0
Exp/Cntr=0.3,0.1

Type RM Length L Ch R = 1 ,34851   ,225,225,225
BEGIN DESCRIPTION:
Mapping XS 92311a1c
END DESCRIPTION:
XS GIS Cut Line= 3
      3662462.26     10671405.25      3661956.85     10671162.13
      3660909.96     10671253.27
#Sta/Elev= 30
  4111.4  267.72  4117.6  267.38  4132.8  268.23    4161   267.5    4246  268.21
  4338.6  265.82  4392.8  264.74  4477.8   264.8    4536  265.04  4558.2  266.12
  4580.4  265.55  4647.3  267.02  4668.7  264.71  4672.2  264.71  4679.5  266.69
  4778.7  265.59  4840.1  264.93  4911.4  263.61  4987.7  262.77  4990.4  262.27
  4993.7  262.77  5007.7  263.38  5111.1  263.27  5201.5  264.71  5372.1  266.98
  5392.2  267.83  5403.3  269.39  5516.1  274.04    5613  279.57  5723.1  283.79
#Mann= 8 ,-1 , 0
  4111.4     .08       0  4117.6     .05       0  4338.6     .12       0
  4778.7     .05       0  4911.4     .12       0  4987.7     .07       0
  4993.7     .12       0  5007.7     .05       0
Bank Sta=4840.1,5201.5
XS Rating Curve= 0 ,0
Exp/Cntr=0.3,0.1

Type RM Length L Ch R = 1 ,34562   ,375,375,375
BEGIN DESCRIPTION:
UNT 0415 IN LACR 28.0
END DESCRIPTION:
XS GIS Cut Line= 4
      3664223.61     10670967.45      3662925.04     10670804.26
      3662018.79     10670804.26      3660665.89     10671195.24
#Sta/Elev= 30
  2349.3  271.35  2367.9  271.07  2373.5  275.22  2383.6  275.59  2403.7  271.51
  2413.8  275.33  2716.2   264.7  2796.8   266.7  2937.9  264.55  2988.3   265.3
  2998.4  267.48  3028.6  266.37  3038.7  262.56  3048.8  262.37  3058.8  266.15
  3726.7  264.28  3850.5  260.84  3853.3  260.34  3856.5  260.84  4373.5   262.7
  4584.3  266.58  4674.3  264.54  4884.9   262.5  5002.9  261.13  5271.3  264.58
  5344.2     262  5359.9   264.3  5489.9  266.52    5771  283.39  5972.6  289.05
#Mann= 5 ,-1 , 0
  2349.3     .16       0  3726.7     .16       0  3850.5     .16       0
  3856.5     .16       0  4884.9     .16       0
#XS Ineff= 2 , 0
         4381.82  277.65 5288.64          275.09
Permanent Ineff=
       F       F
Bank Sta=4674.3,5271.3
XS Rating Curve= 0 ,0
Exp/Cntr=0.3,0.1

Type RM Length L Ch R = 1 ,34187   ,387,387,387
BEGIN DESCRIPTION:
UNT 0415 IN LACR 27.0
END DESCRIPTION:
XS GIS Cut Line= 4
      3664862.55      10670998.7       3662779.2     10670509.12
      3661758.37     10670493.49      3660517.65     10671029.98
#Sta/Elev= 30
  1546.4  272.81  1671.7   273.6  1732.9  275.56    1808  272.27  2155.5  269.42
  2196.6  271.75  2214.7  268.55  2237.7  270.85  2521.8  263.46  2689.7  265.71
  2823.2  265.06  2843.7  261.77  2871.3  265.23  3639.2   262.4  3746.1  259.27
  3776.1  261.71  4006.1  259.95  4496.2  264.71  4656.2  262.63  4719.8  262.03
    5033  259.61    5131  262.46  5182.2  258.55    5185  258.05  5188.2  258.55
  5261.2  262.74  5342.5  259.76  5577.7  262.32    5950  279.82  6059.2  280.99
#Mann= 7 ,-1 , 0
  1546.4     .16       0  1671.7     .16       0    1808     .16       0
  3639.2     .16       0  4719.8     .16       0  5182.2     .16       0
  5188.2     .16       0
#XS Ineff= 2 , 0
         3901.14  276.36 5407.95          275.01
Permanent Ineff=
       F       F
Bank Sta=4656.2,5261.2
XS Rating Curve= 0 ,0
Exp/Cntr=0.3,0.1

Type RM Length L Ch R = 1 ,33800   ,862,862,862
BEGIN DESCRIPTION:
UNT 0415 IN LACR 26.0
END DESCRIPTION:
XS GIS Cut Line= 5
      3665055.29     10670941.42      3662664.62     10670326.83
      3661607.33     10670207.03      3661128.16     10670321.62
       3659988.5     10670805.58
#Sta/Elev= 30
  1274.6  273.35  1373.4  271.09  1384.4  274.29  1425.1  274.47  1545.3  267.79
  1582.9  267.48  1590.2  270.85  1630.9  269.48  2382.1  262.63  2715.7  264.59
  2736.3  261.61  2748.6  264.22  3594.8  260.73  3686.2   258.6  3696.6  260.72
  4231.1  260.39  4378.2  263.48  4552.6  261.53  4713.9   259.4  4989.8  257.53
  5030.9  260.49  5130.7  256.23  5133.5  255.73  5136.7  256.23  5746.4  259.27
  6110.8  264.97  6281.2  269.02  6297.7  266.59    6352  273.71  6537.9  280.31
#Mann= 8 ,-1 , 0
  1274.6     .16       0  1545.3     .16       0  1630.9     .16       0
  3594.8     .16       0  4713.9     .16       0  5130.7     .16       0
  5136.7     .16       0  6110.8     .16       0
#XS Ineff= 2 , 0
         4361.36  274.26 5414.77          274.15
Permanent Ineff=
       F       F
Bank Sta=4552.6,5030.9
XS Rating Curve= 0 ,0
Exp/Cntr=0.3,0.1

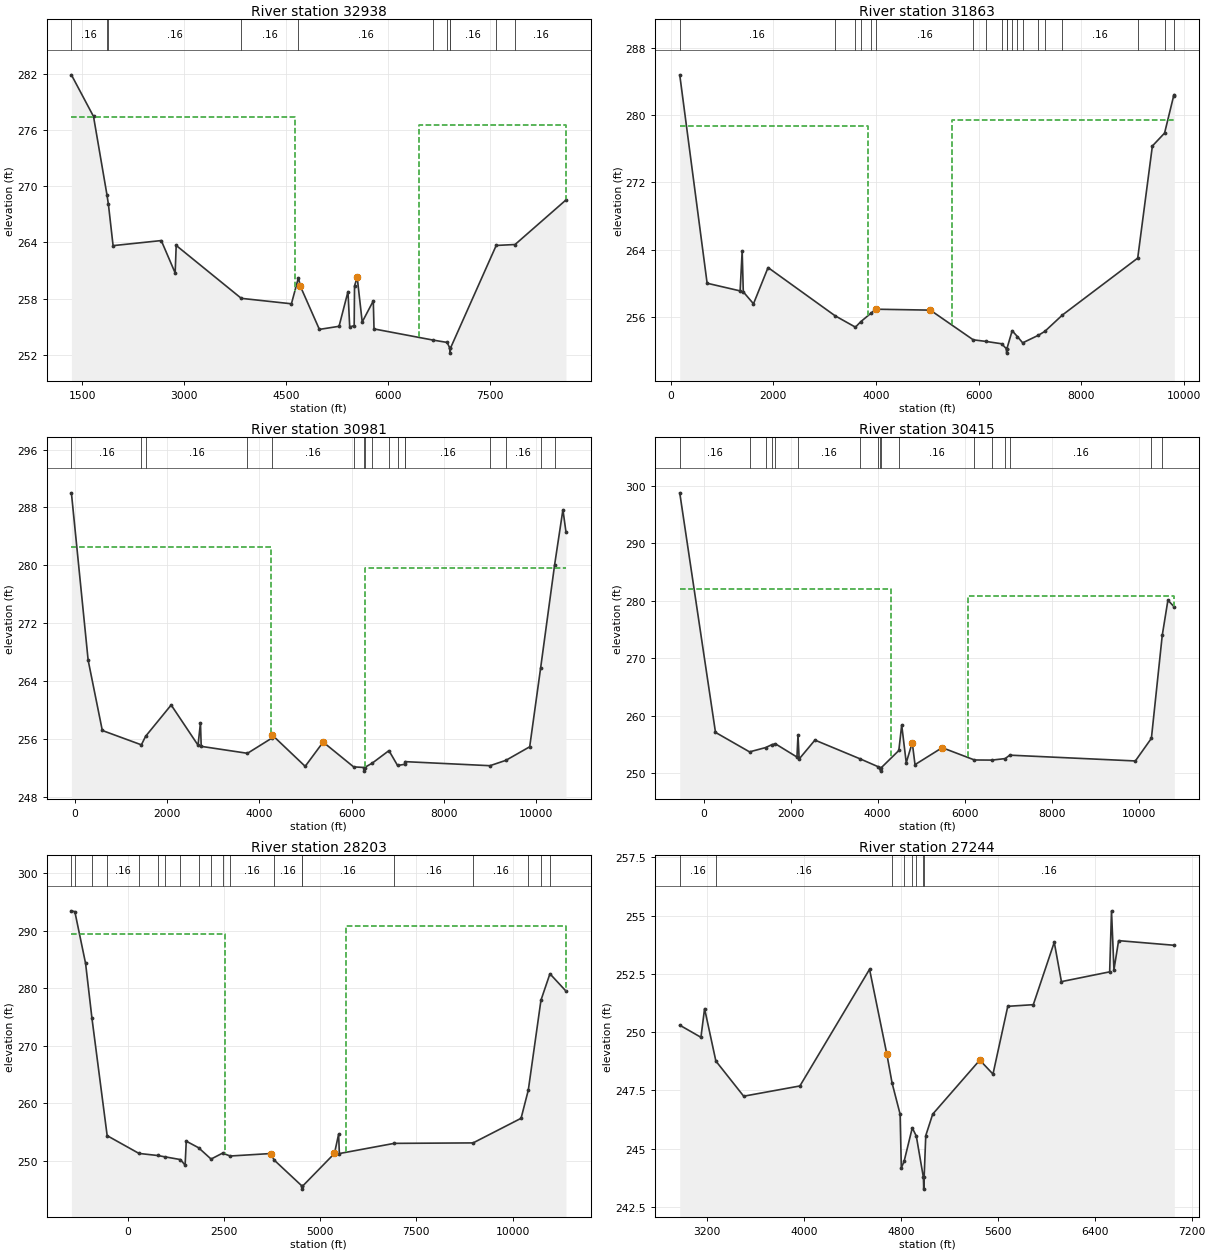
Type RM Length L Ch R = 1 ,32938   ,1075,1075,1075
BEGIN DESCRIPTION:
Mapping XS 5de97b28
END DESCRIPTION:
XS GIS Cut Line= 5
      3665190.63     10670722.65       3663466.7     10670238.28
      3661971.91     10669644.53      3661273.99     10669696.62
      3658206.32     10670550.77
#Sta/Elev= 30
    1337  281.86  1662.8  277.42  1860.4  269.08  1881.9  268.07  1950.9  263.65
  2660.5  264.19    2865  260.74  2880.4  263.67  3839.1  258.03  4577.2  257.45
    4680  260.22  4709.4  259.31  4989.1  254.72  5278.6  255.05  5410.2  258.75
  5435.6  254.96  5501.4  255.13  5506.6  259.36    5546  260.26  5619.6  255.51
    5783  257.76  5793.4  254.77  6663.2  253.58  6870.9  253.33  6911.5  252.69
  6914.3  252.19  6917.5  252.69  7592.9  263.67  7870.6  263.77  8620.3  268.52
#Mann= 11 ,-1 , 0
    1337     .16       0  1860.4     .16       0  1881.9     .16       0
  3839.1     .16       0    4680     .16       0  6663.2     .16       0
  6870.9     .16       0  6911.5     .16       0  6917.5     .16       0
  7592.9     .16       0  7870.6     .16       0
#XS Ineff= 2 , 0
         4627.27  277.38    6450           276.5
Permanent Ineff=
       F       F
Bank Sta=4709.4,5546
XS Rating Curve= 0 ,0
Exp/Cntr=0.3,0.1

Type RM Length L Ch R = 1 ,31863   ,882,882,882
BEGIN DESCRIPTION:
UNT 0415 IN LACR 25.0
END DESCRIPTION:
XS GIS Cut Line= 4
      3665561.76     10670397.14      3662386.69     10669073.31
      3661858.52       10669051.      3656335.47     10670298.84
#Sta/Elev= 30
   179.1  284.76   712.3  260.04  1355.2  259.13  1394.9  263.88  1416.6  259.02
  1615.2   257.6  1898.9   261.9  3201.8  256.19  3600.1  254.83  3706.2  255.49
  3897.9  256.46  3996.8  256.96  5059.1  256.85  5893.8  253.33  6140.7  253.14
  6447.7  252.86  6542.6  252.25  6545.4  251.75  6548.6  252.25  6652.4  254.41
  6754.7  253.71  6857.1  252.97  7163.6  253.87  7288.6  254.33  7630.5  256.27
  9097.1  263.02  9382.7  276.32  9620.3  277.85  9796.5  282.25    9810   282.4
#Mann= 20 ,-1 , 0
   179.1     .16       0  3201.8     .16       0  3600.1     .16       0
  3706.2     .16       0  3897.9     .16       0  3996.8     .16       0
  5893.8     .16       0  6140.7     .16       0  6447.7     .16       0
  6542.6     .16       0  6548.6     .16       0  6652.4     .16       0
  6754.7     .16       0  6857.1     .16       0  7163.6     .16       0
  7288.6     .16       0  7630.5     .16       0  9097.1     .16       0
  9620.3     .16       0  9796.5     .16       0
#XS Ineff= 2 , 0
         3840.91  278.65 5477.27          279.39
Permanent Ineff=
       F       F
Bank Sta=3996.8,5059.1
XS Rating Curve= 0 ,0
Exp/Cntr=0.3,0.1

Type RM Length L Ch R = 1 ,30981   ,566,566,566
BEGIN DESCRIPTION:
UNT 0415 IN LACR 24.0
END DESCRIPTION:
XS GIS Cut Line= 4
      3666212.81     10669937.07      3662211.94     10668549.58
      3660990.46     10668573.57      3655814.65     10669528.44
#Sta/Elev= 30
   -74.4  290.02   288.8  266.91   595.8  257.21  1442.3  255.23  1534.1  256.41
  2088.2  260.73  2670.3  255.18  2723.2  258.28  2739.2  255.02  3741.8  254.06
  4265.8  256.14  4282.6  256.56  4992.7  252.26  5381.9  255.61    6042  252.19
  6274.7   252.1  6277.5   251.6  6280.7   252.1  6447.4  252.71  6808.2  254.43
    6995  252.38    7147  252.54  7156.8  252.91    8998  252.35  9342.5  253.09
  9858.8  254.96 10095.8  265.84 10399.9  280.12   10579  287.69 10645.1  284.61
#Mann= 17 ,-1 , 0
   -74.4     .16       0  1442.3     .16       0  1534.1     .16       0
  3741.8     .16       0  4265.8     .16       0    6042     .16       0
  6274.7     .16       0  6280.7     .16       0  6447.4     .16       0
  6808.2     .16       0    6995     .16       0    7147     .16       0
  7156.8     .16       0    8998     .16       0  9342.5     .16       0
 10095.8     .16       0 10399.9     .16       0
#XS Ineff= 2 , 0
         4244.32   282.6 6296.59          279.66
Permanent Ineff=
       F       F
Bank Sta=4282.6,5381.9
XS Rating Curve= 0 ,0
Exp/Cntr=0.3,0.1

Type RM Length L Ch R = 1 ,30415   ,2212,2212,2212
BEGIN DESCRIPTION:
UNT 0415 IN LACR 23.0
END DESCRIPTION:
XS GIS Cut Line= 4
       3666846.5     10669381.52       3664155.5     10668452.69
      3662874.25      10667938.8      3655814.03     10669008.17
#Sta/Elev= 30
  -549.4  298.78   272.5   257.1  1055.3  253.71  1425.1  254.46  1561.4  254.94
    1648  255.12  2144.9  252.81  2168.6  256.64  2195.2  252.47  2558.1  255.76
  3604.5  252.47  4010.2  251.13  4063.9  250.86  4066.6  250.36  4069.9  250.86
  4486.7  253.95  4552.4  258.39  4656.9  251.81  4795.1  255.33  4858.3  251.49
  5482.8  254.44    6225   252.3  6627.6  252.28  6929.7  252.54  7036.9  253.14
  9922.9  252.13 10291.8  256.07 10541.4     274 10671.4   280.1 10818.6  278.92
#Mann= 17 ,-1 , 0
  -549.4     .16       0  1055.3     .16       0  1425.1     .16       0
  1561.4     .16       0    1648     .16       0  2168.6     .16       0
  3604.5     .16       0  4010.2     .16       0  4063.9     .16       0
  4069.9     .16       0  4486.7     .16       0    6225     .16       0
  6627.6     .16       0  6929.7     .16       0  7036.9     .16       0
 10291.8     .16       0 10541.4     .16       0
#XS Ineff= 2 , 0
            4300   282.1 6073.86          280.79
Permanent Ineff=
       F       F
Bank Sta=4795.1,5482.8
XS Rating Curve= 0 ,0
Exp/Cntr=0.3,0.1

Type RM Length L Ch R = 1 ,28203   ,959,959,959
BEGIN DESCRIPTION:
UNT 0415 IN LACR 22.0
END DESCRIPTION:
XS GIS Cut Line= 4
      3667307.75     10666449.01      3661292.11     10666774.53
      3660667.11     10667282.34       3654690.5     10667933.39
#Sta/Elev= 30
 -1457.7  293.44 -1367.9  293.29   -1089  284.28  -924.1  274.76    -529  254.33
   297.2  251.24   778.9  250.88   977.5  250.64  1374.7  250.17  1494.8  249.19
  1524.8  253.37  1844.4  252.23  2169.1  250.26    2467  251.29  2665.6  250.79
    3718  251.22  3808.4  250.08  4536.2  245.53    4539  245.03  4542.2  245.53
    5372  251.23  5480.2  254.57  5500.3  251.22  6923.6  252.99  8972.6  253.07
   10218  257.35 10405.7  262.25 10734.7   277.9 10967.4  282.49   11384  279.48
#Mann= 20 ,-1 , 0
 -1457.7     .16       0 -1367.9     .16       0  -924.1     .16       0
    -529     .16       0   297.2     .16       0   778.9     .16       0
   977.5     .16       0  1374.7     .16       0  1844.4     .16       0
  2169.1     .16       0    2467     .16       0  2665.6     .16       0
  3808.4     .16       0  4536.2     .16       0  4542.2     .16       0
  6923.6     .16       0  8972.6     .16       0 10405.7     .16       0
 10734.7     .16       0 10967.4     .16       0
#XS Ineff= 2 , 0
         2534.09  289.49 5660.23          290.76
Permanent Ineff=
       F       F
Bank Sta=3718,5372
XS Rating Curve= 0 ,0
Exp/Cntr=0.3,0.1

Type RM Length L Ch R = 1 ,27244   ,804,804,804
BEGIN DESCRIPTION:
UNT 0415 IN LACR 21.0
END DESCRIPTION:
XS GIS Cut Line= 2
      3662662.89     10666153.04      3658615.66     10666684.71
#Sta/Elev= 30
  2974.4   250.3  3149.3  249.78  3179.4  251.01  3272.6  248.76  3502.2  247.25
  3966.1  247.69    4541   252.7  4683.6  249.06  4726.8  247.82  4793.2  246.48
  4803.3  244.17  4826.5  244.46  4893.6  245.89  4926.8  245.54  4985.5  243.76
  4988.2  243.26  4991.5  243.76    5005  245.56  5062.2  246.48  5450.8   248.8
  5559.7   248.2  5681.9  251.11  5892.5  251.18  6065.5  253.86  6124.5  252.17
  6522.8  252.59    6538  255.21  6558.2  252.68  6596.5  253.93  7056.4  253.73
#Mann= 8 ,-1 , 0
  2974.4     .16       0  3272.6     .16       0  4726.8     .16       0
  4826.5     .16       0  4893.6     .16       0  4926.8     .16       0
  4985.5     .16       0  4991.5     .16       0
Bank Sta=4683.6,5450.8
XS Rating Curve= 0 ,0
Exp/Cntr=0.3,0.1

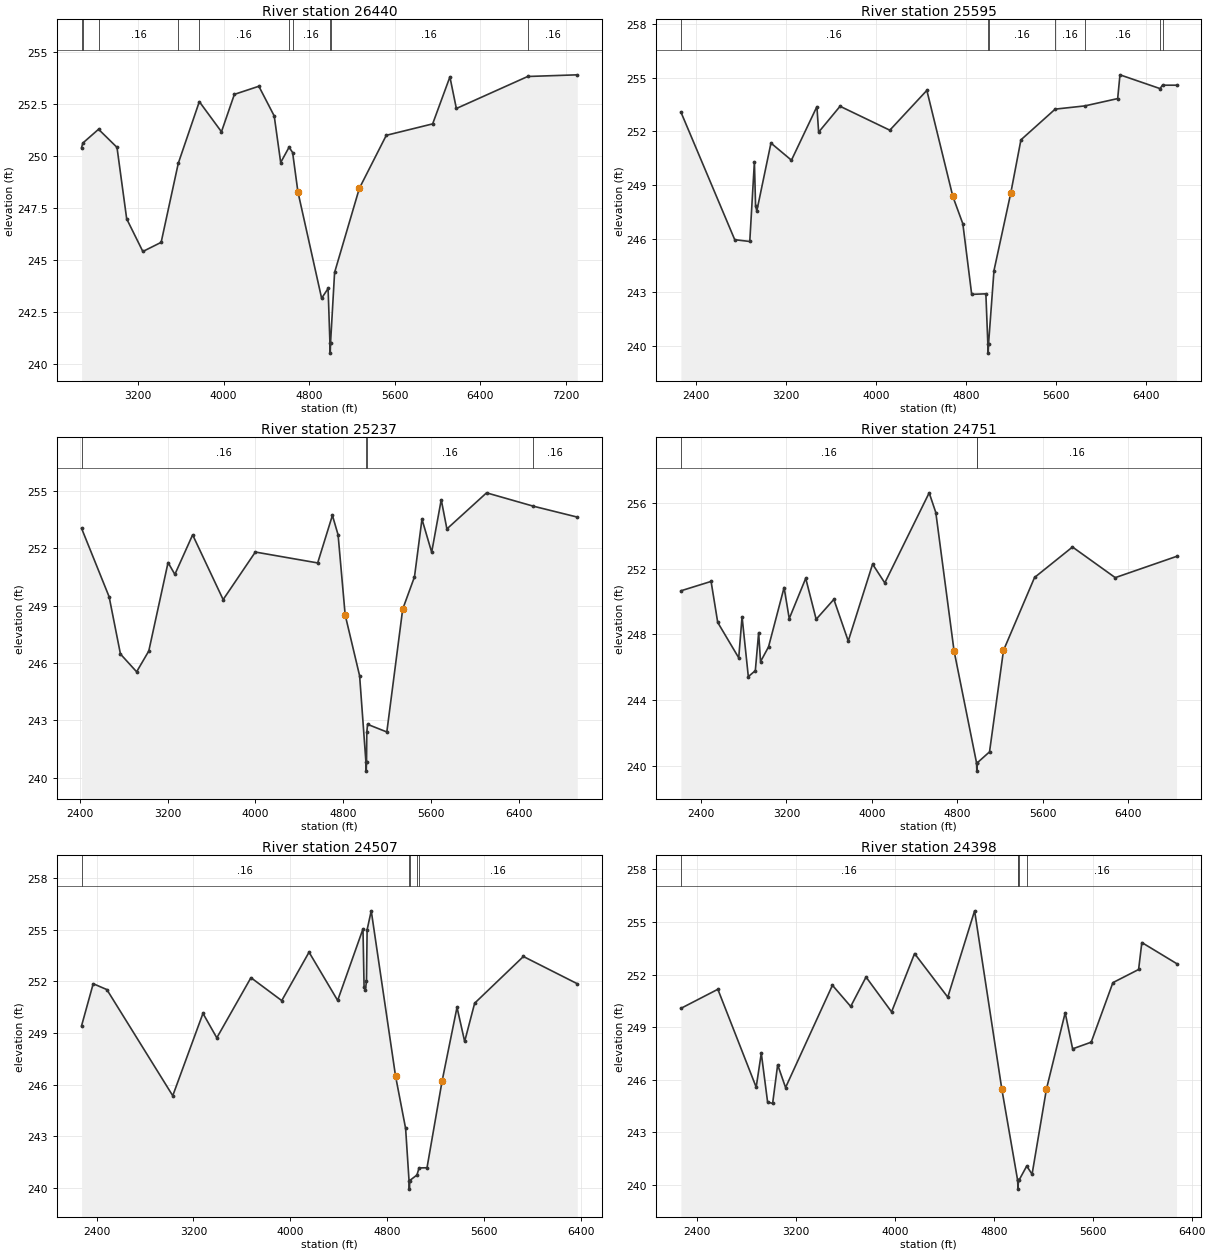
Type RM Length L Ch R = 1 ,26440   ,845,845,845
BEGIN DESCRIPTION:
UNT 0415 IN LACR 20.0
END DESCRIPTION:
XS GIS Cut Line= 3
      3663248.53     10665486.63      3661154.69     10665751.56
       3658648.2     10666087.93
#Sta/Elev= 30
  2670.3  250.42  2682.4  250.64  2829.2   251.3  3001.8  250.43  3092.6  246.99
  3243.8  245.42  3415.1  245.86  3575.3  249.66  3772.4  252.63  3979.6  251.18
  4100.5  252.98  4329.6  253.37  4473.5  251.94    4534   249.7  4612.6  250.44
  4645.7  250.18  4695.2  248.29  4917.1  243.17  4977.7  243.64  4994.8  241.03
  4997.6  240.53  5000.8  241.03  5038.5  244.41  5270.3  248.46  5522.5  251.01
  5956.4  251.56  6117.8  253.82  6178.3   252.3  6845.9  253.84  7309.8  253.92
#Mann= 10 ,-1 , 0
  2670.3     .16       0  2682.4     .16       0  2829.2     .16       0
  3575.3     .16       0  3772.4     .16       0  4612.6     .16       0
  4645.7     .16       0  4994.8     .16       0  5000.8     .16       0
  6845.9     .16       0
Bank Sta=4695.2,5270.3
XS Rating Curve= 0 ,0
Exp/Cntr=0.3,0.1

Type RM Length L Ch R = 1 ,25595   ,358,358,358
BEGIN DESCRIPTION:
UNT 0415 IN LACR 19.0
END DESCRIPTION:
XS GIS Cut Line= 3
      3663274.92     10664657.69      3660705.43     10665278.36
      3658990.23     10665683.97
#Sta/Elev= 30
  2268.1  253.09  2746.8  245.94  2880.5  245.84  2921.7   250.3    2932  247.84
  2943.1  247.55  3068.8  251.35  3250.9  250.39  3477.2  253.39  3492.6  251.96
    3683  253.41  4125.3  252.07  4454.5   254.3  4685.5  248.36  4774.4  246.83
    4853  242.88  4979.1  242.91  4996.7  240.09  4999.4  239.59  5002.7  240.09
  5051.1  244.21    5201  248.57  5290.7  251.53  5595.2  253.25  5858.6  253.43
  6150.6  253.84  6171.1  255.17  6526.8   254.4  6549.1  254.59    6674  254.59
#Mann= 7 ,-1 , 0
  2268.1     .16       0  4996.7     .16       0  5002.7     .16       0
  5595.2     .16       0  5858.6     .16       0  6526.8     .16       0
  6549.1     .16       0
Bank Sta=4685.5,5201
XS Rating Curve= 0 ,0
Exp/Cntr=0.3,0.1

Type RM Length L Ch R = 1 ,25237   ,486,486,486
BEGIN DESCRIPTION:
UNT 0415 IN LACR 18.0
END DESCRIPTION:
XS GIS Cut Line= 2
       3663172.6     10664369.01      3658799.65     10665510.18
#Sta/Elev= 30
  2414.5  253.05  2665.6  249.47    2769  246.47  2916.5  245.54  3027.4  246.63
    3203  251.26  3265.1  250.64  3427.1  252.71  3705.3  249.32  3998.8  251.81
  4567.2  251.24  4701.6  253.73  4753.3  252.71  4817.8  248.52  4949.6  245.33
  5006.8  240.84  5009.6  240.34  5012.8  240.84    5015  242.37    5022  242.79
  5197.7  242.39  5342.4  248.82  5449.8  250.51  5518.1  253.53  5606.6   251.8
  5693.8  254.55  5745.4  253.02  6107.1  254.91    6534  254.21  6933.9  253.64
#Mann= 4 ,-1 , 0
  2414.5     .16       0  5006.8     .16       0  5012.8     .16       0
    6534     .16       0
Bank Sta=4817.8,5342.4
XS Rating Curve= 0 ,0
Exp/Cntr=0.3,0.1

Type RM Length L Ch R = 1 ,24751   ,244,244,244
BEGIN DESCRIPTION:
UNT 0415 IN LACR 17.0
END DESCRIPTION:
XS GIS Cut Line= 3
      3663172.66     10663869.86      3661447.36     10664336.46
       3658699.6     10665110.19
#Sta/Elev= 30
  2211.6  250.65  2494.5  251.22  2556.6  248.73  2753.4  246.58  2784.5  249.08
  2843.2  245.44  2908.8   245.8  2939.9  248.11  2957.6  246.35  3032.2  247.24
  3178.2  250.85  3226.4  248.96  3380.7  251.41  3478.6  248.92  3644.2  250.13
    3779   247.6  4006.9  252.27  4121.2  251.13  4536.8   256.6  4599.1   255.4
  4769.7  247.01  4980.5   240.2  4983.2   239.7  4986.5   240.2    5102  240.87
  5232.8  247.03  5523.7  251.46    5879  253.31  6279.3  251.45  6853.5  252.74
#Mann= 3 ,-1 , 0
  2211.6     .16       0  4980.5     .16       0  4986.5     .16       0
Bank Sta=4769.7,5232.8
XS Rating Curve= 0 ,0
Exp/Cntr=0.3,0.1

Type RM Length L Ch R = 1 ,24507   ,109,109,109
BEGIN DESCRIPTION:
UNT 0415 IN LACR 16.0
END DESCRIPTION:
XS GIS Cut Line= 3
      3663133.97     10663658.36      3660218.14     10664477.22
      3659188.72      10664736.9
#Sta/Elev= 30
  2276.7  249.42  2372.7  251.86  2485.3  251.52  3029.1  245.36  3278.4  250.14
  3392.6  248.72  3674.3  252.21  3928.4  250.88  4153.7  253.69  4389.8  250.89
  4598.9  255.04  4607.9  251.68  4618.3  251.48  4627.8  252.01    4633  254.99
    4667  256.09  4867.6   246.5  4950.7  243.46  4978.8  240.44  4981.6  239.94
  4984.8  240.44  5044.4  240.76  5061.4  241.17  5127.2  241.18  5251.9  246.22
  5374.8  250.49  5437.9  248.51  5520.4  250.73  5922.6  253.44    6367  251.86
#Mann= 5 ,-1 , 0
  2276.7     .16       0  4978.8     .16       0  4984.8     .16       0
  5044.4     .16       0  5061.4     .16       0
Bank Sta=4867.6,5251.9
XS Rating Curve= 0 ,0
Exp/Cntr=0.3,0.1

Type RM Length L Ch R = 1 ,24398   ,1385,1385,1385
BEGIN DESCRIPTION:
UNT 0415 IN LACR 15.0
END DESCRIPTION:
XS GIS Cut Line= 3
      3663129.21     10663609.46      3660232.96     10664354.53
      3659233.82     10664541.87
#Sta/Elev= 30
  2270.9  250.07  2569.8  251.16  2879.7  245.57    2921  247.51  2971.8  244.73
  3012.6  244.64  3053.3  246.85  3117.2  245.55    3496  251.39  3643.8  250.18
  3767.7  251.86  3974.2  249.87  4160.1   253.2  4428.5  250.71  4645.4  255.64
    4865  245.48  4993.4  240.25  4996.2  239.75  4999.4  240.25  5004.4  240.26
  5066.9  241.07    5110   240.6  5226.4  245.47  5377.7  249.82  5437.8  247.76
    5588  248.14  5763.4  251.54  5971.2  252.29  5997.4  253.83    6278  252.63
#Mann= 5 ,-1 , 0
  2270.9     .16       0  4993.4     .16       0  4999.4     .16       0
  5004.4     .16       0  5066.9     .16       0
Bank Sta=4865,5226.4
XS Rating Curve= 0 ,0
Exp/Cntr=0.3,0.1

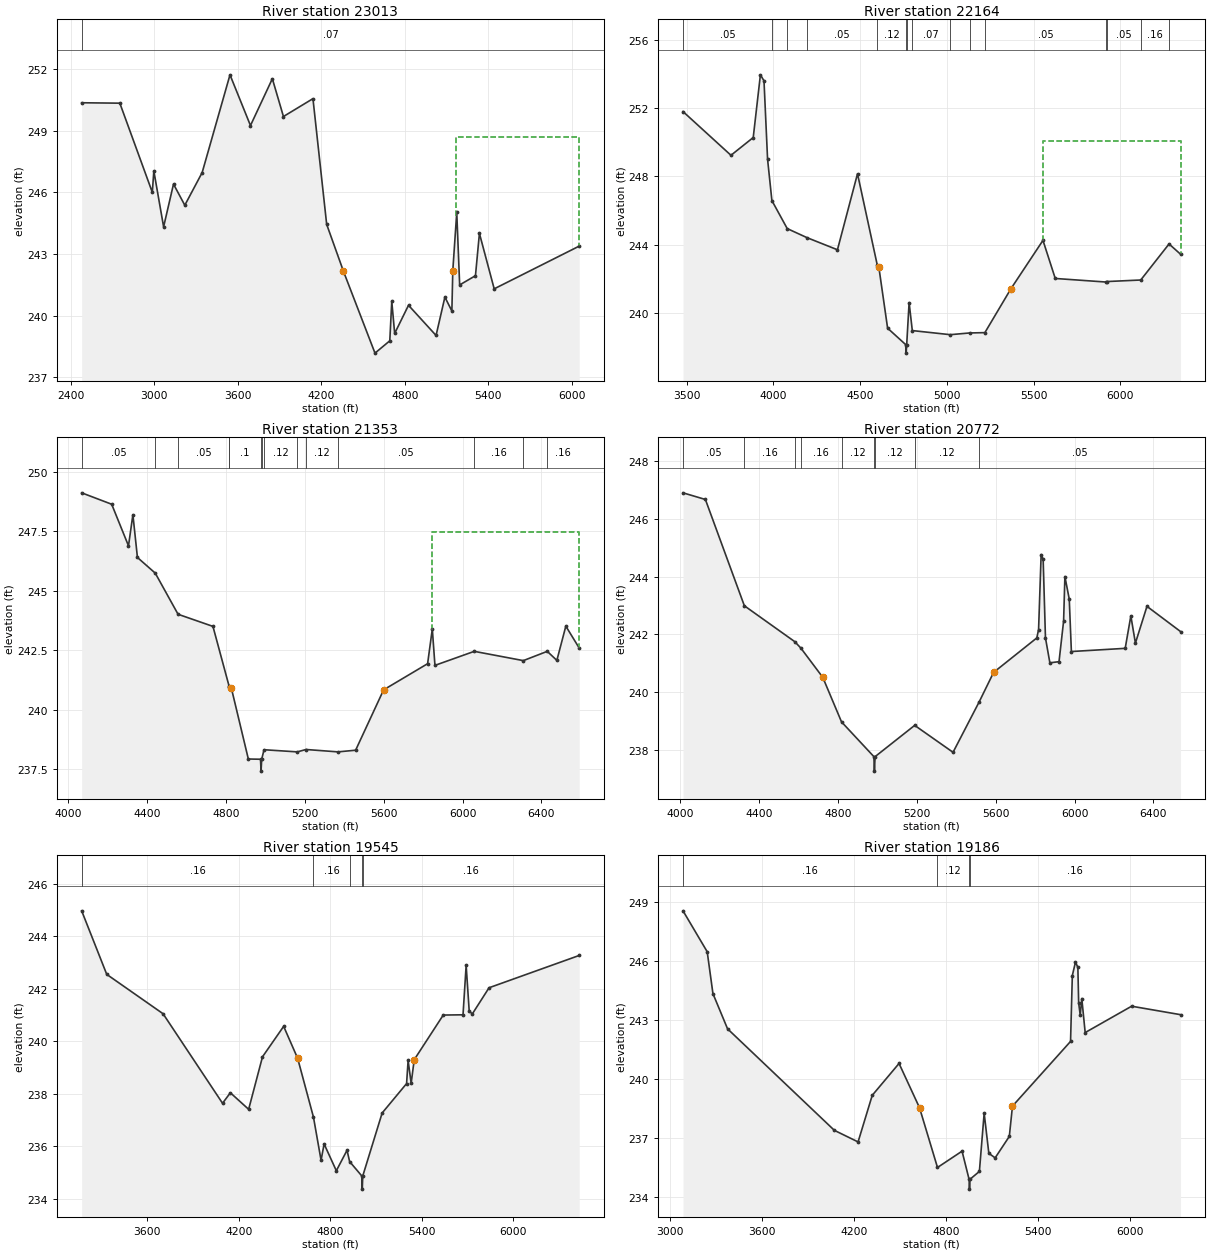
Type RM Length L Ch R = 1 ,23013   ,849,849,849
BEGIN DESCRIPTION:
UNT 0415 IN LACR 14.0
END DESCRIPTION:
XS GIS Cut Line= 3
      3663009.89      10663576.9      3661577.57     10663826.47
      3660000.88     10662405.98
#Sta/Elev= 30
  2477.9  250.36  2752.2  250.34  2985.7     246  2996.6  247.04  3066.9  244.32
    3138   246.4  3219.2  245.37  3343.9  246.96    3544  251.72  3691.2  249.25
  3848.5  251.53  3928.2  249.69  4140.3  250.56  4238.9  244.44  4359.8  242.15
  4586.2  238.17  4692.6  238.77  4706.8  240.69  4727.7  239.13  4827.1   240.5
  5025.2  239.03  5088.7   240.9  5138.8  240.22  5145.5  242.19  5173.9  245.02
  5194.8  241.49  5308.4  241.94  5336.8     244    5443   241.3    6054  243.38
#Mann= 1 ,-1 , 0
  2477.9     .07       0
#XS Ineff= 2 , 0
                         5172.04          248.71
Permanent Ineff=
       F       F
Bank Sta=4359.8,5145.5
XS Rating Curve= 0 ,0
Exp/Cntr=0.3,0.1

Type RM Length L Ch R = 1 ,22164   ,811,811,811
BEGIN DESCRIPTION:
UNT 0415 IN LACR 13.0
END DESCRIPTION:
XS GIS Cut Line= 3
      3663031.56     10663283.94      3661718.63     10662947.57
      3660399.59     10662210.18
#Sta/Elev= 30
  3479.7   251.8    3756  249.24  3884.3  250.28  3925.6  253.95  3946.3   253.6
  3966.9  249.01  3991.8  246.59  4080.1  244.95    4194  244.42  4369.5  243.71
  4485.1  248.16  4598.6  242.83  4607.5  242.73  4658.5  239.12  4762.5  238.16
  4765.2  237.66  4768.5  238.16  4782.4  240.62  4800.8  238.98  5019.4  238.74
  5130.4  238.84  5218.9  238.86  5369.7  241.44  5553.6  244.26  5624.4  242.03
  5918.6  241.82  5922.5  241.85  6116.9  241.94    6280  244.05  6346.2  243.45
#Mann= 15 ,-1 , 0
  3479.7     .05       0  3991.8     .07       0  4080.1     .12       0
    4194     .05       0  4598.6     .12       0  4762.5     .07       0
  4768.5     .12       0  4800.8     .07       0  5019.4     .05       0
  5130.4     .07       0  5218.9     .05       0  5918.6     .12       0
  5922.5     .05       0  6116.9     .16       0    6280     .12       0
#XS Ineff= 2 , 0
                         5554.96          250.06
Permanent Ineff=
       F       F
Bank Sta=4607.5,5369.7
XS Rating Curve= 0 ,0
Exp/Cntr=0.3,0.1

Type RM Length L Ch R = 1 ,21353   ,581,581,581
BEGIN DESCRIPTION:
UNT 0415 IN LACR 12.0
END DESCRIPTION:
XS GIS Cut Line= 3
        3662987.     10662952.84      3662058.14     10662345.18
      3660755.17     10661797.68
#Sta/Elev= 30
  4068.1  249.12  4220.3  248.64  4305.6  246.89  4327.9   248.2  4350.9   246.4
  4441.4  245.74    4557  244.01  4733.9   243.5  4815.6  240.99  4816.5  240.97
  4827.4   240.9  4913.4  237.92  4975.1  237.91  4977.9  237.41  4981.1  237.91
    4993  238.31  5161.5  238.22  5206.2  238.32  5367.9  238.22  5457.5  238.29
  5599.5  240.83  5822.6  241.93  5846.4  243.39  5859.8  241.86  6059.2  242.45
  6308.1  242.06  6429.4  242.45  6478.1  242.07  6523.6  243.51  6591.4  242.59
#Mann= 14 ,-1 , 0
  4068.1     .05       0  4441.4     .16       0    4557     .05       0
  4815.6     .16       0  4816.5      .1       0  4975.1     .07       0
  4981.1      .1       0    4993     .12       0  5161.5     .07       0
  5206.2     .12       0  5367.9     .05       0  6059.2     .16       0
  6308.1     .12       0  6429.4     .16       0
#XS Ineff= 2 , 0
                         5845.88          247.47
Permanent Ineff=
       F       F
Bank Sta=4827.4,5599.5
XS Rating Curve= 0 ,0
Exp/Cntr=0.3,0.1

Type RM Length L Ch R = 1 ,20772   ,1227,1227,1227
BEGIN DESCRIPTION:
UNT 0415 IN LACR 11.0
END DESCRIPTION:
XS GIS Cut Line= 3
       3663148.1     10662602.24       3662640.9     10662031.64
       3661034.2     10661312.36
#Sta/Elev= 30
    4014  246.89  4127.6  246.66  4325.2  242.99    4581  241.75  4611.6  241.53
  4722.9  240.52  4818.1  238.98  4982.3  237.78    4985  237.28  4988.3  237.78
  5189.2  238.86  5383.8  237.93    5517  239.68  5589.6  240.69  5808.8  241.88
  5817.7  242.17  5830.7  244.76  5840.9  244.59  5852.6  241.88    5875  241.02
  5921.4  241.06  5944.6  242.46  5951.2     244  5973.3  243.22  5984.1  241.41
  6257.1  241.52  6285.7  242.64  6308.9   241.7  6367.5  242.97  6537.8   242.1
#Mann= 9 ,-1 , 0
    4014     .05       0  4325.2     .16       0    4581     .05       0
  4611.6     .16       0  4818.1     .12       0  4982.3     .07       0
  4988.3     .12       0  5189.2     .12       0    5517     .05       0
Bank Sta=4722.9,5589.6
XS Rating Curve= 0 ,0
Exp/Cntr=0.3,0.1

Type RM Length L Ch R = 1 ,19545   ,359,359,359
BEGIN DESCRIPTION:
UNT 0415 IN LACR 10.0
END DESCRIPTION:
XS GIS Cut Line= 3
      3664349.77     10661320.87      3662839.39     10660973.65
      3661129.37     10660886.77
#Sta/Elev= 30
  3170.2  244.96  3334.6  242.54  3703.9  241.04  4093.8  237.63  4145.1  238.03
    4265   237.4  4355.8   239.4  4494.5  240.56  4586.4  239.34    4690   237.1
  4739.8  235.46  4759.8  236.08  4839.9  235.06    4910  235.84    4927  235.41
  5007.1  234.86  5009.9  234.36  5013.1  234.86  5140.3  237.26  5300.5  238.38
  5310.5  239.26  5330.5  238.39  5350.6  239.29  5540.8  240.99  5670.5     241
    5691  242.88    5711  241.15  5731.1  241.03  5841.2  242.03  6432.2  243.26
#Mann= 5 ,-1 , 0
  3170.2     .16       0    4690     .16       0    4927     .16       0
  5007.1     .07       0  5013.1     .16       0
Bank Sta=4586.4,5350.6
XS Rating Curve= 0 ,0
Exp/Cntr=0.3,0.1

Type RM Length L Ch R = 1 ,19186   ,961,961,961
BEGIN DESCRIPTION:
Mapping XS ca4377a4
END DESCRIPTION:
XS GIS Cut Line= 2
      3664540.77     10661060.46      3661382.83     10660323.02
#Sta/Elev= 30
  3086.9  248.53  3244.6  246.45    3282  244.32  3377.3  242.53  4073.2  237.37
    4228  236.78  4320.4  239.15    4495  240.77  4628.4  238.52  4745.6  235.48
  4905.7  236.31  4951.5  234.88  4954.2  234.38  4957.5  234.88  5018.7  235.28
  5049.8  238.24  5080.3   236.2  5121.4  235.97  5213.8  237.06  5234.3   238.6
  5612.9  241.89  5624.5  245.24  5645.1  245.93  5660.6  245.65  5665.7  243.85
  5675.9  243.23  5686.2  244.07  5708.2  242.34    6011  243.68  6329.8  243.25
#Mann= 4 ,-1 , 0
  3086.9     .16       0  4745.6     .12       0  4951.5     .07       0
  4957.5     .16       0
Bank Sta=4628.4,5234.3
XS Rating Curve= 0 ,0
Exp/Cntr=0.3,0.1

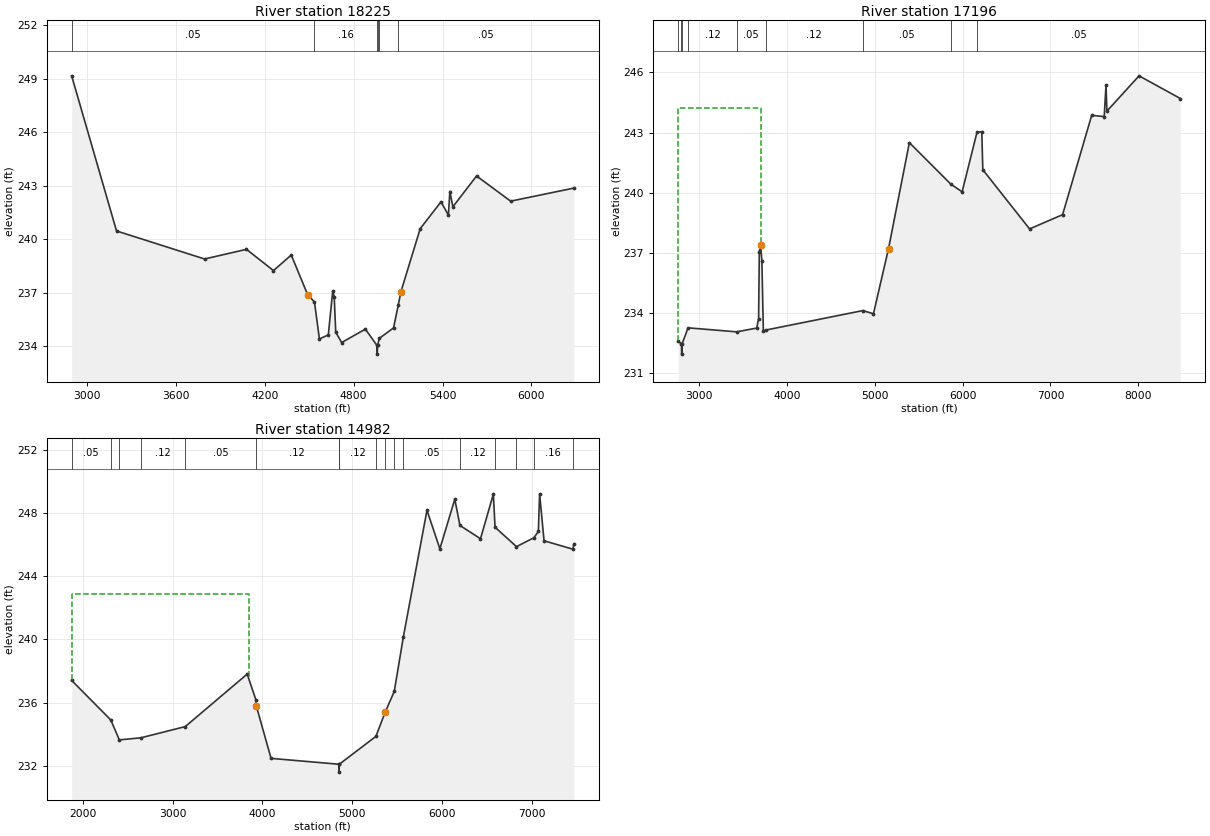
Type RM Length L Ch R = 1 ,18225   ,1029,1029,1029
BEGIN DESCRIPTION:
UNT 0415 IN LACR 9.0
END DESCRIPTION:
XS GIS Cut Line= 3
       3664575.5     10660652.47      3663629.32     10659714.97
      3661573.29     10659749.67
#Sta/Elev= 30
  2897.7  249.16  3200.5  240.47  3794.4   238.9  4077.3  239.44  4259.4  238.25
  4379.4  239.12  4489.4  236.91    4536  236.49  4569.4  234.42  4629.4  234.65
  4659.5  237.12  4669.5  236.75  4679.5   234.8  4719.5  234.22  4879.5  234.97
  4956.5  234.07  4959.2  233.57  4962.5  234.07    4973  234.45  5069.5  235.04
  5102.1  236.34  5119.5  237.07  5249.5   240.6  5389.6   242.1  5439.6  241.36
  5449.6  242.68  5469.6  241.82  5629.6  243.55  5859.6  242.14    6286  242.87
#Mann= 6 ,-1 , 0
  2897.7     .05       0    4536     .16       0  4956.5     .07       0
  4962.5     .12       0    4973     .16       0  5102.1     .05       0
Bank Sta=4489.4,5119.5
XS Rating Curve= 0 ,0
Exp/Cntr=0.3,0.1

Type RM Length L Ch R = 1 ,17196   ,2214,2214,2214
BEGIN DESCRIPTION:
UNT 0415 IN LACR 8.0
END DESCRIPTION:
XS GIS Cut Line= 3
      3664297.72     10658412.89       3661719.6     10659471.92
      3658838.08     10658925.12
#Sta/Elev= 30
  2759.3  232.62  2797.5  232.46  2800.3  231.96  2803.5  232.46  2872.7  233.27
  3427.2  233.07  3654.6  233.26  3676.2  233.73    3684  237.03  3697.8   237.4
  3713.4  236.62  3730.2  233.12  3758.8  233.16  4863.3  234.13  4984.3  233.97
  5156.1  237.22  5393.4   242.5    5866  240.43  5994.3  240.05  6163.2  243.01
  6218.2  243.05  6229.9  241.15  6762.7   238.2  7138.7  238.91  7470.2  243.86
  7612.7   243.8    7633  245.36  7643.2  244.07  8009.6  245.83  8479.4   244.7
#Mann= 9 ,-1 , 0
  2759.3     .05       0  2797.5     .03       0  2803.5     .05       0
  2872.7     .12       0  3427.2     .05       0  3758.8     .12       0
  4863.3     .05       0    5866     .16       0  6163.2     .05       0
#XS Ineff= 2 , 0
         3697.73  244.22
Permanent Ineff=
       F       F
Bank Sta=3697.8,5156.1
XS Rating Curve= 0 ,0
Exp/Cntr=0.3,0.1

Type RM Length L Ch R = 1 ,14982   ,0,0,0
BEGIN DESCRIPTION:
UNT 0415 IN LACR 7.0
END DESCRIPTION:
XS GIS Cut Line= 2
      3664080.67     10657011.85      3658613.28     10658174.76
#Sta/Elev= 30
  1876.6  237.41    2312  234.91  2407.3  233.65    2647  233.78  3141.2  234.49
  3830.4  237.81  3926.9  236.19  3932.7  235.78  4096.2  232.48  4849.8  232.11
  4852.5  231.61  4855.8  232.11  5263.3  233.87  5365.3  235.39  5467.3  236.71
  5569.3  240.18  5831.6  248.17  5975.3  245.73    6141  248.87  6198.8  247.21
  6427.2  246.37  6570.4  249.19  6589.3   247.1  6827.7  245.87  7021.3  246.43
  7071.3  246.83  7085.2  249.21  7134.8  246.24  7455.2  245.71  7466.3  246.04
#Mann= 17 ,-1 , 0
  1876.6     .05       0    2312     .12       0  2407.3     .07       0
    2647     .12       0  3141.2     .05       0  3926.9     .12       0
  4849.8     .07       0  4855.8     .12       0  5263.3     .07       0
  5365.3     .05       0  5467.3     .07       0  5569.3     .05       0
  6198.8     .12       0  6589.3     .16       0  6827.7     .12       0
  7021.3     .16       0  7455.2     .12       0
#XS Ineff= 2 , 0
         3851.85  242.88
Permanent Ineff=
       F       F
Bank Sta=3932.7,5365.3
XS Rating Curve= 0 ,0
Exp/Cntr=0.3,0.1

Chan Stop Cuts=-1
Use User Specified Reach Order=0
Composite Channel Slope=5