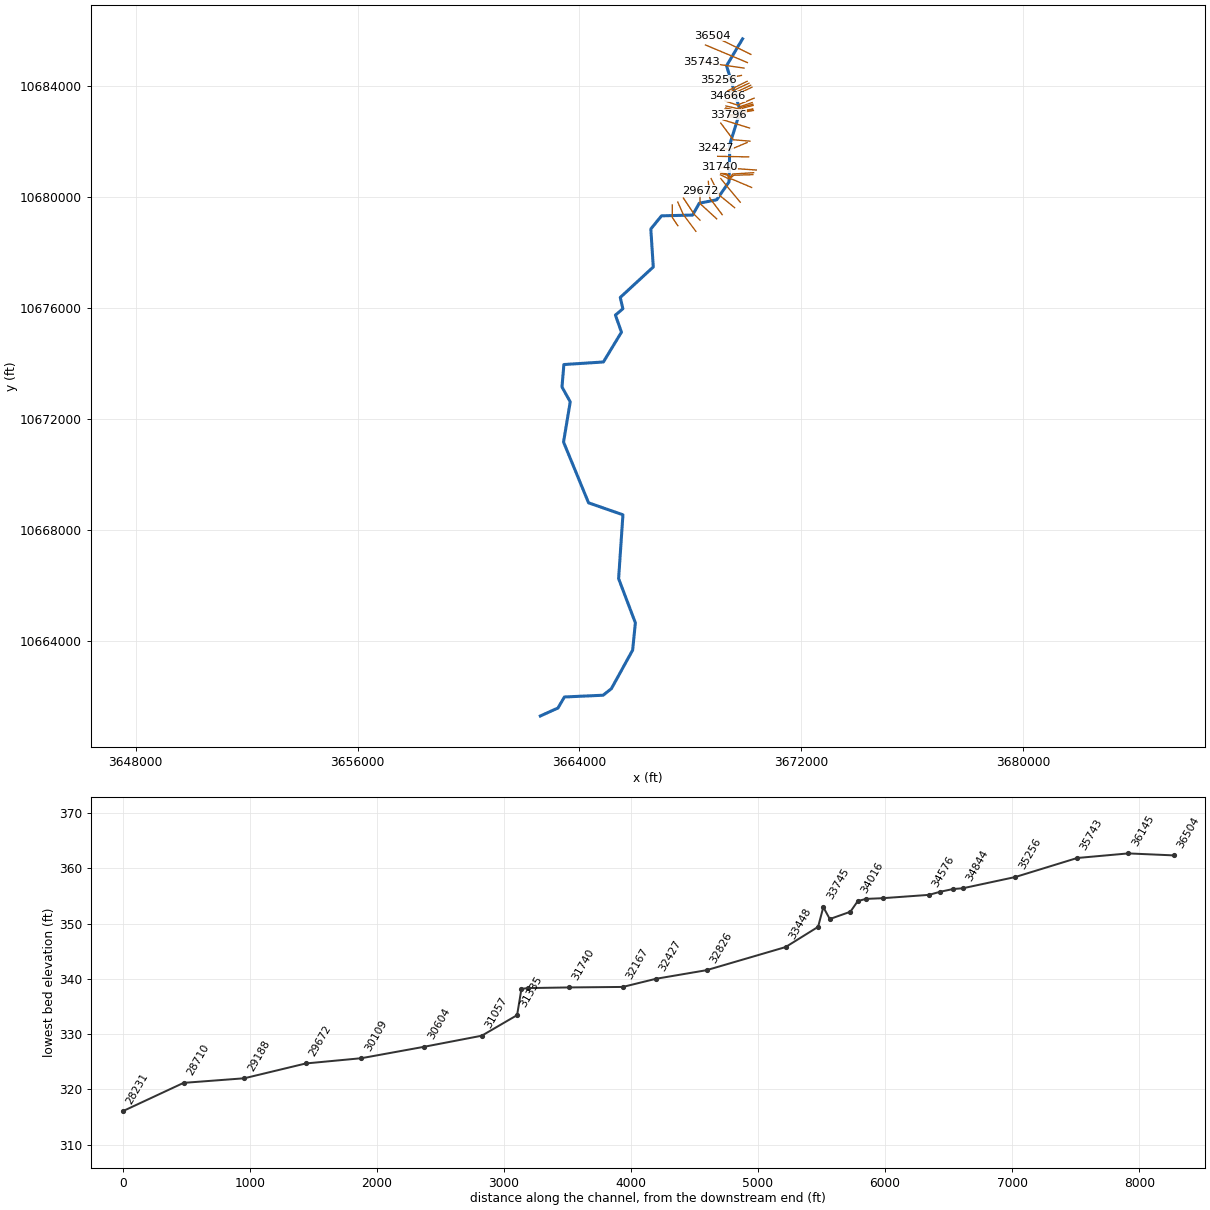
--- UNT 0417 IN LACR.prj (project) ---

Proj Title=UNT 0417 IN LACR Base Level Engineering
Current Plan=p01
Default Exp/Contr=0.3,0.1
English Units
Geom File=g01
Flow File=f01
Plan File=p01
Y Axis Title=Elevation
X Axis Title(PF)=Main Channel Distance
X Axis Title(XS)=Station
BEGIN DESCRIPTION:
UNT 0417 IN LACR
END DESCRIPTION:
DSS Export Rating Curves= 0
DSS Export Rating Curve Sorted= 0
DSS Export Volume Flow Curves= 0
DXF OffsetX= 0
DXF OffsetY= 0
DXF ScaleX= 1
DXF ScaleY= 10

--- UNT 0417 IN LACR.p01 (plan) ---

Plan Title=Multiple Run
Short Identifier=Multiple
Geom File=g01
Flow File=f01
Subcritical Flow
K Sum by GR= 0
Std Step Tol= 0.01
Critical Tol= 0.01
Num of Std Step Trials= 20
Max Error Tol= 0.3
Flow Tol Ratio= 0.001
Split Flow NTrial= 30
Split Flow Tol= 0.02
Split Flow Ratio= 0.02
Log Output Level= 0
Friction Slope Method= 1
Unsteady Friction Slope Method= 2
Unsteady Bridges Friction Slope Method= 1
Parabolic Critical Depth
Global Vel Dist=  1 , 1 , 1
Global Log Level= 0
CheckData=True
Encroach Param= -1, 0, 0, 0
BEGIN DESCRIPTION:
Multiple Run
END DESCRIPTION:

--- UNT 0417 IN LACR.f01 (steady flow) ---

Flow Title=Multiple
Program Version=4.10
Number of Profiles= 7
Profile Names=10-year,25-year,50-year,1pct_min,100-year,1pct_plu,500-year
River Rch & RM=UNT 0417 IN LACR,Reach-1         ,36504
     519     694     836     740    1001    1353    1439
River Rch & RM=UNT 0417 IN LACR,Reach-1         ,27468
     719     974    1184    1055    1427    1930    2082
River Rch & RM=UNT 0417 IN LACR,Reach-1         ,15071
     865    1179    1438    1286    1739    2351    2553
River Rch & RM=UNT 0417 IN LACR,Reach-1         ,14595
    1797    2526    3145    2862    3871    5235    5897
River Rch & RM=UNT 0417 IN LACR,Reach-1         ,7566
    1797    2526    3145    2862    3871    5235    5897
Boundary for River Rch & Prof#=UNT 0417 IN LACR,Reach-1         , 1
Up Type= 0
Dn Type= 3
Dn Slope=0.005
Boundary for River Rch & Prof#=UNT 0417 IN LACR,Reach-1         , 2
Up Type= 0
Dn Type= 3
Dn Slope=0.005
Boundary for River Rch & Prof#=UNT 0417 IN LACR,Reach-1         , 3
Up Type= 0
Dn Type= 3
Dn Slope=0.005
Boundary for River Rch & Prof#=UNT 0417 IN LACR,Reach-1         , 4
Up Type= 0
Dn Type= 3
Dn Slope=0.005
Boundary for River Rch & Prof#=UNT 0417 IN LACR,Reach-1         , 5
Up Type= 0
Dn Type= 3
Dn Slope=0.005
Boundary for River Rch & Prof#=UNT 0417 IN LACR,Reach-1         , 6
Up Type= 0
Dn Type= 3
Dn Slope=0.005
Boundary for River Rch & Prof#=UNT 0417 IN LACR,Reach-1         , 7
Up Type= 0
Dn Type= 3
Dn Slope=0.005
DSS Import GetInterval= 0
DSS Import GetPeak= 0
DSS Import FillOption= 0

--- UNT 0417 IN LACR.f02 (steady flow) ---

Flow Title=Flow 02
Program Version=4.10
Number of Profiles= 1
Profile Names=PF 1
DSS Import GetInterval= 0
DSS Import GetPeak= 0
DSS Import FillOption= 0

--- UNT 0417 IN LACR.g01 (geometry) ---

Geom Title=Existing Conditions
Program Version=4.10

River Reach=UNT 0417 IN LACR,Reach-1
Reach XY= 30
      3669884.11     10685698.87        3669307.       10684730.
        3669800.       10683095.       3669423.5       10681895.
        3669396.       10680542.      3668950.75       10679896.
      3668323.25       10679772.      3668082.25       10679345.
        3666961.       10679317.      3666575.25       10678843.
      3666664.25       10677473.      3665473.75       10676374.
      3665567.75       10675966.      3665299.25       10675738.
        3665517.       10675122.       3664865.5       10674047.
      3663441.25       10673955.      3663371.75       10673146.
      3663670.25       10672610.      3663428.25       10671160.
      3664330.75       10668968.        3665570.       10668537.
      3665414.25       10666235.      3666018.75       10664640.
      3665921.25       10663659.      3665152.75       10662265.
       3664854.5       10662030.        3663461.       10661967.
        3663226.       10661568.      3662589.75       10661281.

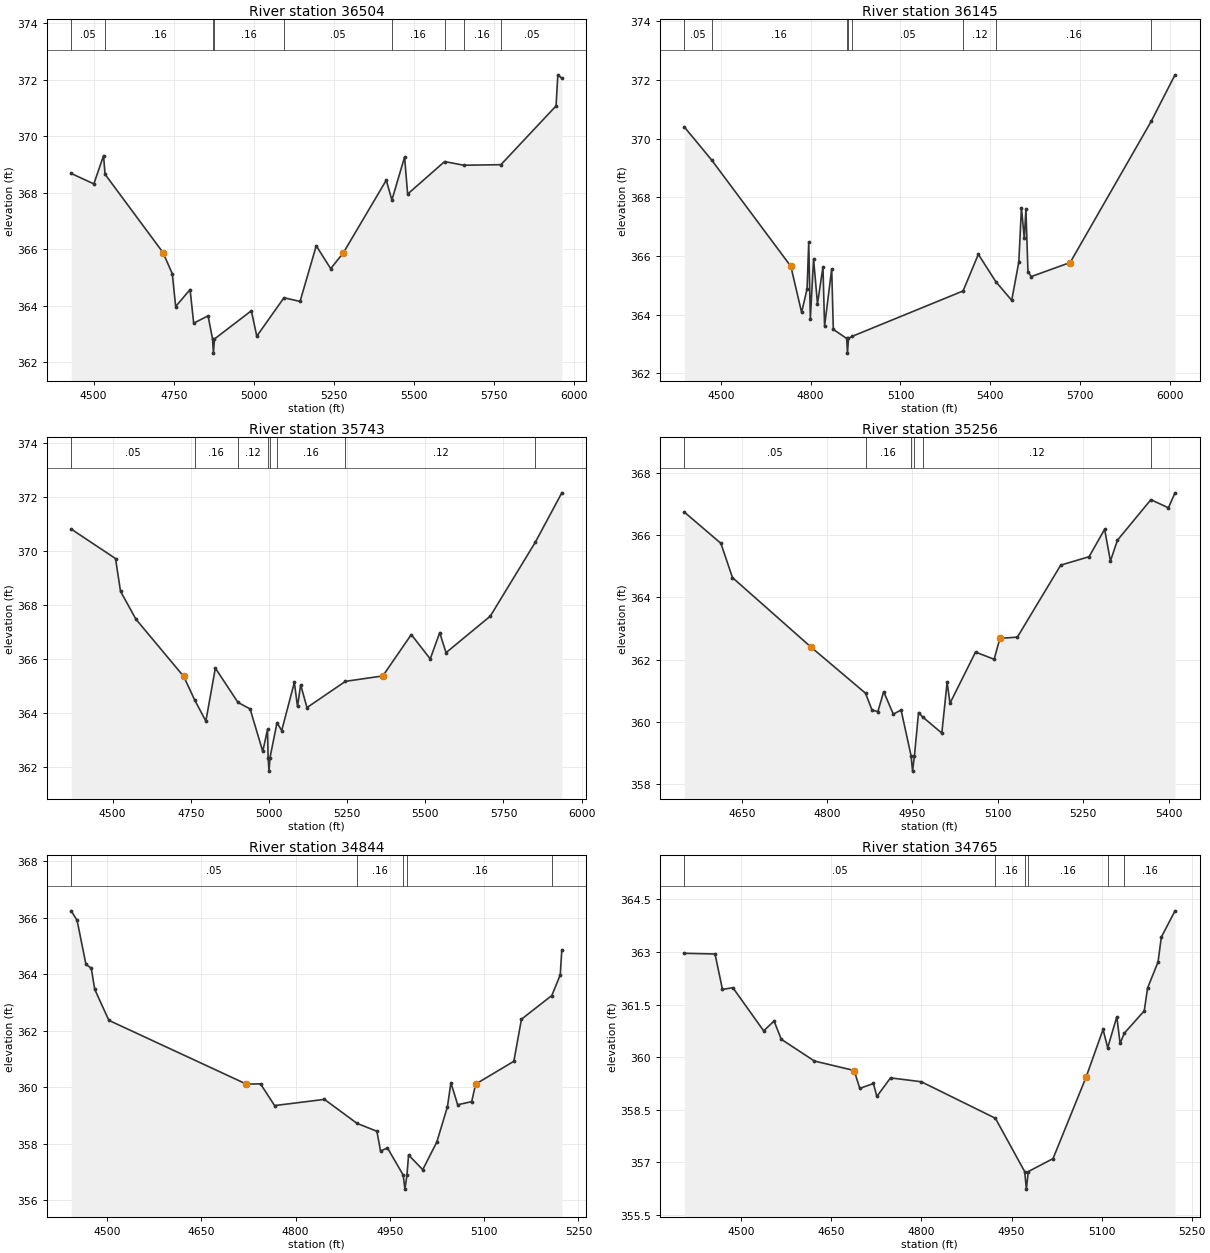
Type RM Length L Ch R = 1 ,36504   ,359,359,359
BEGIN DESCRIPTION:
UNT 0417 IN LACR 62.0
END DESCRIPTION:
XS GIS Cut Line= 2
       3670183.1     10685139.76      3668807.26     10685812.49
#Sta/Elev= 30
  4429.9  368.69  4500.6  368.32  4530.9  369.32  4535.6  368.66  4716.5  365.89
  4745.5  365.14    4756  363.98    4801  364.58  4812.3  363.39  4857.2  363.65
  4871.1  362.83  4873.9  362.33  4877.1  362.83  4992.3  363.83  5009.2  362.93
  5094.1  364.29  5144.3  364.16  5194.9  366.13  5239.9  365.32  5279.4  365.88
  5413.4  368.45    5431  367.75  5470.6  369.27  5480.1  367.96  5595.6  369.11
  5655.5  368.98  5771.3     369  5943.4  371.08    5949  372.18  5961.4  372.06
#Mann= 9 ,-1 , 0
  4429.9     .05       0  4535.6     .16       0  4871.1     .07       0
  4877.1     .16       0  5094.1     .05       0    5431     .16       0
  5595.6     .05       0  5655.5     .16       0  5771.3     .05       0
Bank Sta=4716.5,5279.4
XS Rating Curve= 0 ,0
Exp/Cntr=0.3,0.1

Type RM Length L Ch R = 1 ,36145   ,402,402,402
BEGIN DESCRIPTION:
UNT 0417 IN LACR 61.0
END DESCRIPTION:
XS GIS Cut Line= 2
      3670057.31     10684844.58      3668546.86     10685478.28
#Sta/Elev= 30
  4378.7   370.4  4470.1  369.27  4734.1  365.65    4770  364.08  4788.3  364.88
  4793.8  366.48  4799.2  363.87    4810   365.9    4823  364.37  4841.3  365.63
  4846.7  363.61  4870.5  365.56  4875.9   363.5  4920.5  363.19  4923.2  362.69
  4926.5  363.19  4938.2  363.26  5309.1  364.81  5360.1  366.06  5418.2  365.13
  5471.5  364.49  5495.2   365.8    5504  367.65  5513.5   366.6  5518.9   367.6
  5525.7  365.47  5536.6   365.3  5666.7  365.78  5936.9  370.59  6016.7  372.18
#Mann= 8 ,-1 , 0
  4378.7     .05       0  4470.1     .16       0  4920.5     .03       0
  4926.5     .16       0  4938.2     .05       0  5309.1     .12       0
  5418.2     .16       0  5936.9     .12       0
Bank Sta=4734.1,5666.7
XS Rating Curve= 0 ,0
Exp/Cntr=0.3,0.1

Type RM Length L Ch R = 1 ,35743   ,487,487,487
BEGIN DESCRIPTION:
UNT 0417 IN LACR 60.0
END DESCRIPTION:
XS GIS Cut Line= 2
      3669935.71     10684644.95       3668383.3     10684870.44
#Sta/Elev= 30
  4367.8  370.81  4509.5  369.72  4525.5  368.51  4574.6  367.48  4727.6  365.36
  4762.6  364.49  4798.4  363.71  4828.7  365.67  4901.1   364.4  4939.8  364.16
  4980.3  362.59  4995.5   363.4  4997.5  362.36  5000.3  361.86  5003.5  362.36
  5025.8  363.65  5040.9  363.36  5081.3  365.14  5091.4  364.25  5101.5  365.05
  5121.7  364.21  5244.7  365.18  5364.2  365.38  5455.2  366.91  5515.8  366.01
  5546.1  366.98  5566.3  366.24  5707.8  367.59  5852.1  370.33  5936.5  372.15
#Mann= 8 ,-1 , 0
  4367.8     .05       0  4762.6     .16       0  4901.1     .12       0
  4997.5     .07       0  5003.5     .12       0  5025.8     .16       0
  5244.7     .12       0  5852.1     .16       0
Bank Sta=4727.6,5364.2
XS Rating Curve= 0 ,0
Exp/Cntr=0.3,0.1

Type RM Length L Ch R = 1 ,35256   ,412,412,412
BEGIN DESCRIPTION:
UNT 0417 IN LACR 59.0
END DESCRIPTION:
XS GIS Cut Line= 2
      3669842.31      10684380.9       3668998.5     10684203.81
#Sta/Elev= 30
  4549.2  366.73  4613.3  365.73  4633.7  364.63  4771.7   362.4  4867.5  360.92
  4878.9  360.38  4889.2  360.33  4899.4  360.97  4916.3  360.25    4930  360.38
  4947.5  358.92  4950.2  358.42  4953.5  358.92  4960.7   360.3  4967.8  360.16
  5001.6  359.64  5010.9  361.27    5016   360.6  5060.8  362.24  5093.5  362.01
  5103.7  362.68  5134.4  362.72  5210.5  365.03  5260.4   365.3  5287.7  366.18
  5297.9  365.16  5310.2  365.83    5369  367.13  5399.8  366.87  5411.4  367.35
#Mann= 6 ,-1 , 0
  4549.2     .05       0  4867.5     .16       0  4947.5     .07       0
  4953.5     .16       0  4967.8     .12       0    5369     .05       0
Bank Sta=4771.7,5103.7
XS Rating Curve= 0 ,0
Exp/Cntr=0.3,0.1

Type RM Length L Ch R = 1 ,34844   ,79,79,79
BEGIN DESCRIPTION:
Mapping XS b12c4633
END DESCRIPTION:
XS GIS Cut Line= 2
      3670050.66     10684170.55      3669351.19     10683824.71
#Sta/Elev= 30
  4443.2  366.25  4452.6  365.91  4466.7  364.35  4475.1  364.22  4480.6  363.47
  4503.1  362.37  4721.9  360.11  4744.3  360.12  4766.7  359.35    4846  359.57
  4897.8  358.72  4929.4  358.44  4935.2  357.74  4946.2  357.85  4971.2  356.89
    4974  356.39  4977.2  356.89  4979.8   357.6  5002.3  357.08  5024.7  358.06
  5041.6  359.31  5047.1  360.16  5057.9  359.38  5080.2  359.49  5086.4  360.11
  5147.2  360.92  5159.3  362.41  5207.6  363.25    5221  363.98  5223.5  364.86
#Mann= 5 ,-1 , 0
  4443.2     .05       0  4897.8     .16       0  4971.2     .07       0
  4977.2     .16       0  5207.6     .12       0
Bank Sta=4721.9,5086.4
XS Rating Curve= 0 ,0
Exp/Cntr=0.3,0.1

Type RM Length L Ch R = 1 ,34765   ,99,99,99
BEGIN DESCRIPTION:
Mapping XS 6a3986c0
END DESCRIPTION:
XS GIS Cut Line= 2
       3670115.8     10684100.25      3669375.54     10683754.79
#Sta/Elev= 30
  4405.3  362.96  4456.3  362.94  4468.7  361.93    4486  361.98  4537.3  360.75
  4554.6  361.03  4566.6  360.51  4621.8  359.89    4688  359.62  4697.3  359.11
  4720.1  359.25  4725.7  358.88  4748.5  359.41  4799.7   359.3  4923.1  358.26
  4971.9  356.74  4974.7  356.24  4977.9  356.74  5019.1  357.11  5074.1  359.43
  5102.4  360.79  5110.1  360.27  5125.3  361.15  5130.8  360.39  5137.6  360.68
    5171  361.32  5176.5  361.97  5193.9  362.71  5199.4  363.42  5222.2  364.17
#Mann= 6 ,-1 , 0
  4405.3     .05       0  4923.1     .16       0  4971.9     .07       0
  4977.9     .16       0  5110.1     .05       0  5137.6     .16       0
Bank Sta=4688,5074.1
XS Rating Curve= 0 ,0
Exp/Cntr=0.3,0.1

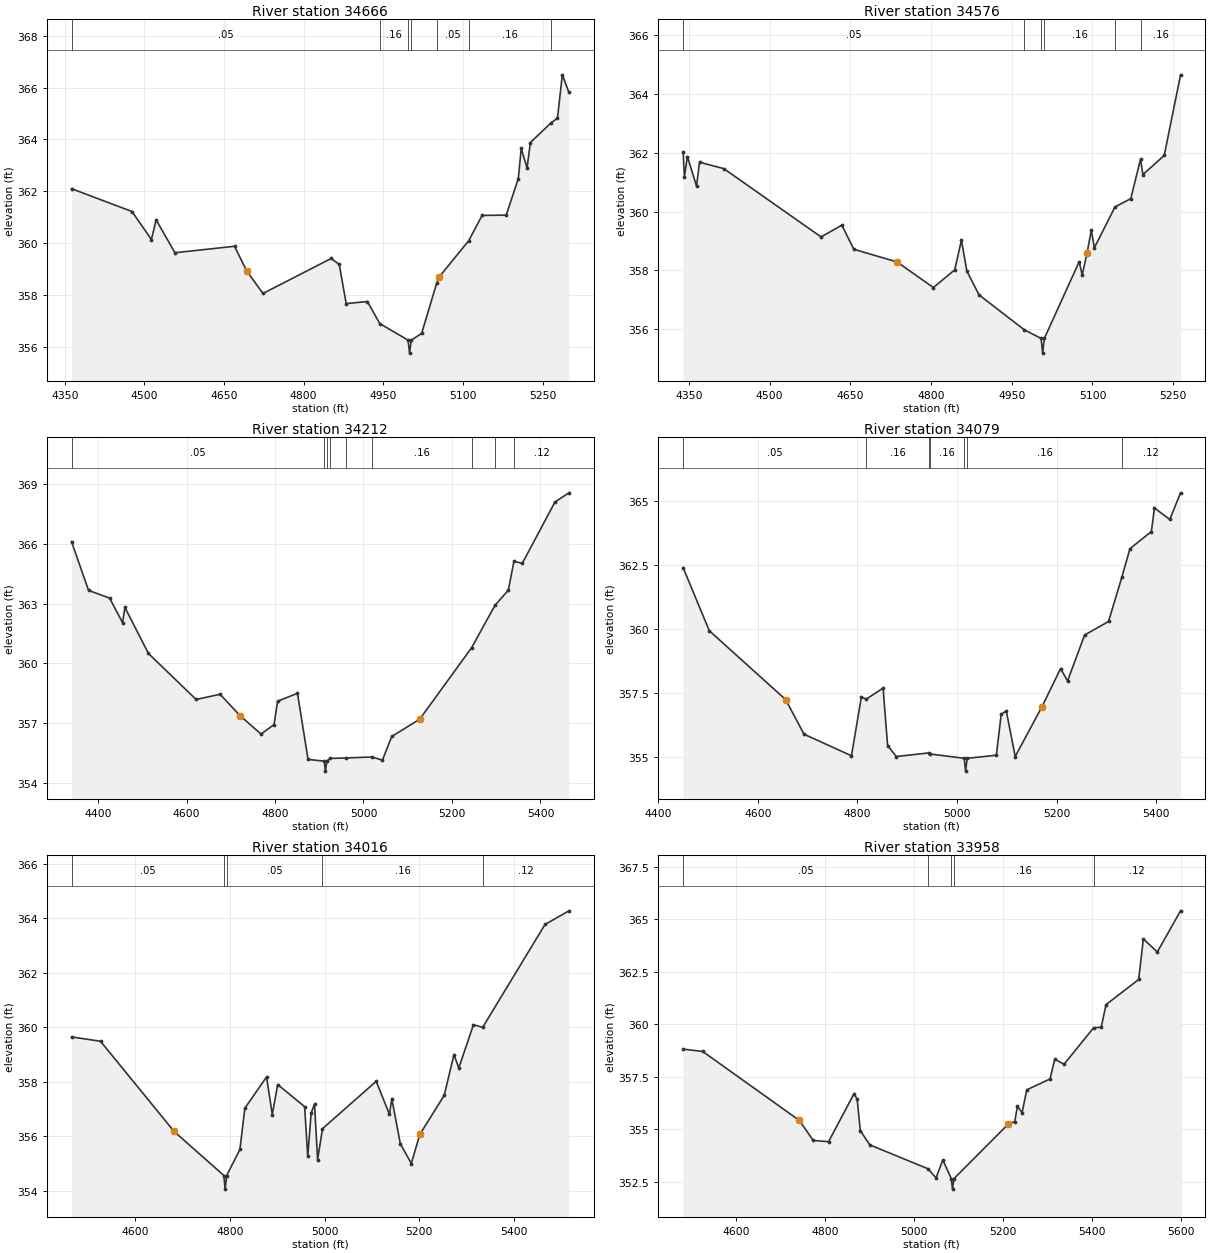
Type RM Length L Ch R = 1 ,34666   ,90,90,90
BEGIN DESCRIPTION:
UNT 0417 IN LACR 58.0
END DESCRIPTION:
XS GIS Cut Line= 2
      3670175.71     10684024.73       3669328.3     10683624.43
#Sta/Elev= 30
  4362.6   362.1  4476.5  361.22  4513.1  360.14    4522   360.9  4557.4  359.63
  4669.7  359.88  4692.5  358.93  4723.3  358.06  4851.8  359.41    4867  359.18
  4880.1  357.67  4920.1  357.75  4943.3   356.9  4996.7  356.26  4999.5  355.76
  5002.7  356.26  5022.2  356.52  5050.8  358.47    5055  358.69  5111.1   360.1
  5136.1  361.07  5181.6  361.08  5204.4  362.49  5209.9  363.65  5220.9   362.9
  5227.1  363.88  5265.7  364.63  5278.2  364.82  5287.3  366.49  5299.8  365.81
#Mann= 7 ,-1 , 0
  4362.6     .05       0  4943.3     .16       0  4996.7     .07       0
  5002.7     .16       0  5050.8     .05       0  5111.1     .16       0
  5265.7     .12       0
Bank Sta=4692.5,5055
XS Rating Curve= 0 ,0
Exp/Cntr=0.3,0.1

Type RM Length L Ch R = 1 ,34576   ,364,364,364
BEGIN DESCRIPTION:
Mapping XS 162a7857
END DESCRIPTION:
XS GIS Cut Line= 2
      3670225.12       10683957.      3669393.18     10683554.02
#Sta/Elev= 30
  4339.3  362.03  4341.7  361.18  4347.2  361.87  4364.2  360.87  4369.8  361.68
    4415  361.46  4595.6  359.14  4634.3  359.54  4656.5  358.72  4736.7  358.29
  4804.4  357.42    4844  358.02  4856.5  359.03  4866.6  357.98  4889.2  357.17
  4973.5  355.98  5004.6  355.69  5007.4  355.19  5010.6  355.69  5075.4   358.3
  5080.9  357.84  5089.9  358.59  5097.9  359.37  5103.5  358.77  5141.9  360.16
  5171.2  360.44  5189.3  361.78  5193.8  361.26  5233.4  361.91  5263.7  364.65
#Mann= 6 ,-1 , 0
  4339.3     .05       0  4973.5     .16       0  5004.6     .07       0
  5010.6     .16       0  5141.9     .12       0  5189.3     .16       0
Bank Sta=4736.7,5089.9
XS Rating Curve= 0 ,0
Exp/Cntr=0.3,0.1

Type RM Length L Ch R = 1 ,34212   ,133,133,133
BEGIN DESCRIPTION:
UNT 0417 IN LACR 57.0
END DESCRIPTION:
XS GIS Cut Line= 3
      3670299.56     10683560.17      3669699.61     10683310.19
       3669249.6     10683460.19
#Sta/Elev= 30
  4340.1  366.12  4378.5  363.67  4426.2  363.28  4455.4  362.05  4460.8  362.81
  4513.9   360.5  4621.7  358.19  4675.9  358.45  4720.8  357.38  4768.5  356.45
  4797.8  356.93  4805.9   358.1  4850.8   358.5  4874.7  355.18  4911.2  355.09
    4914  354.59  4917.2  355.09  4924.3  355.23  4960.1  355.25  5019.6   355.3
  5042.8  355.14  5063.8  356.33  5127.1   357.2  5244.4  360.79  5297.3  362.92
  5327.4  363.68    5340  365.13    5359  365.03  5432.8  368.11  5464.4  368.57
#Mann= 9 ,-1 , 0
  4340.1     .05       0  4911.2    .033       0  4917.2     .05       0
  4924.3     .16       0  4960.1     .05       0  5019.6     .16       0
  5244.4     .12       0  5297.3     .16       0    5340     .12       0
Bank Sta=4720.8,5127.1
XS Rating Curve= 0 ,0
Exp/Cntr=0.3,0.1

Type RM Length L Ch R = 1 ,34079   ,63,63,63
BEGIN DESCRIPTION:
Mapping XS 1b7ae9ec
END DESCRIPTION:
XS GIS Cut Line= 6
      3670229.45       10683400.      3669809.29      10683261.1
      3669765.89     10683219.44      3669724.22     10683191.66
      3669684.29     10683188.19       3669288.5     10683278.45
#Sta/Elev= 30
  4449.9   362.4  4502.4  359.94  4655.8  357.25  4692.7   355.9  4787.9  355.06
  4807.8  357.35  4817.8  357.27  4851.4   357.7  4860.5  355.46  4877.9  355.03
  4942.9  355.17  4945.4  355.13  5014.3  354.96  5017.1  354.46  5020.3  354.96
  5078.8  355.08  5088.6  356.68  5098.8  356.81  5116.7  355.03  5170.6  356.98
  5207.8  358.46  5221.9  357.98    5256  359.77  5304.1   360.3  5330.9  362.03
  5347.1  363.14  5390.1  363.81  5396.3  364.73  5427.1  364.28  5448.7  365.32
#Mann= 7 ,-1 , 0
  4449.9     .05       0  4817.8     .16       0  4942.9     .05       0
  4945.4     .16       0  5014.3     .07       0  5020.3     .16       0
  5330.9     .12       0
Bank Sta=4655.8,5170.6
XS Rating Curve= 0 ,0
Exp/Cntr=0.3,0.1

Type RM Length L Ch R = 1 ,34016   ,58,58,58
BEGIN DESCRIPTION:
Mapping XS 421e73e6
END DESCRIPTION:
XS GIS Cut Line= 6
      3670253.77     10683340.97      3669842.28     10683231.59
      3669767.62     10683144.79      3669725.96     10683122.22
       3669646.1     10683113.54      3669273.75     10683207.05
#Sta/Elev= 30
  4464.9  359.65  4526.2  359.49  4681.7  356.18    4787  354.56  4789.7  354.06
    4793  354.56    4821  355.52  4831.4  357.03  4877.3  358.18  4889.5   356.8
  4900.8   357.9  4957.8  357.09  4964.4  355.26  4971.7  356.86  4978.7  357.18
  4985.3  355.14  4995.6  356.28  5109.2  358.02  5137.1  356.81  5142.2  357.38
  5160.2  355.73  5183.4     355  5201.4  356.07    5253   357.5  5273.6     359
  5283.9  358.51  5314.9   360.1  5334.3     360  5466.2  363.78  5516.8  364.28
#Mann= 5 ,-1 , 0
  4464.9     .05       0    4787     .07       0    4793     .05       0
  4995.6     .16       0  5334.3     .12       0
Bank Sta=4681.7,5201.4
XS Rating Curve= 0 ,0
Exp/Cntr=0.3,0.1

Type RM Length L Ch R = 1 ,33958   ,162,162,162
BEGIN DESCRIPTION:
Mapping XS 92bfe004
END DESCRIPTION:
XS GIS Cut Line= 6
      3670262.45     10683297.57      3669897.83     10683202.08
      3669765.89     10683066.66      3669696.44     10683035.41
      3669620.05     10683047.56      3669239.86     10683167.35
#Sta/Elev= 30
  4481.8  358.81  4525.8   358.7  4743.2  355.41  4774.2  354.46  4808.7   354.4
  4865.8  356.68    4873  356.44    4880  354.93  4901.3  354.25  5032.1  353.11
  5050.3  352.68  5065.6  353.53  5084.6  352.64  5087.3  352.14  5090.6  352.64
  5212.2  355.23  5227.3  355.36  5233.2  356.09  5243.7  355.78  5254.2  356.87
  5306.6  357.39  5317.1  358.33  5338.1  358.09  5404.5  359.83  5421.5  359.85
  5432.4  360.93  5505.8  362.13  5516.3  364.06  5547.7  363.44  5599.9   365.4
#Mann= 5 ,-1 , 0
  4481.8     .05       0  5032.1     .16       0  5084.6     .03       0
  5090.6     .16       0  5404.5     .12       0
Bank Sta=4743.2,5212.2
XS Rating Curve= 0 ,0
Exp/Cntr=0.3,0.1

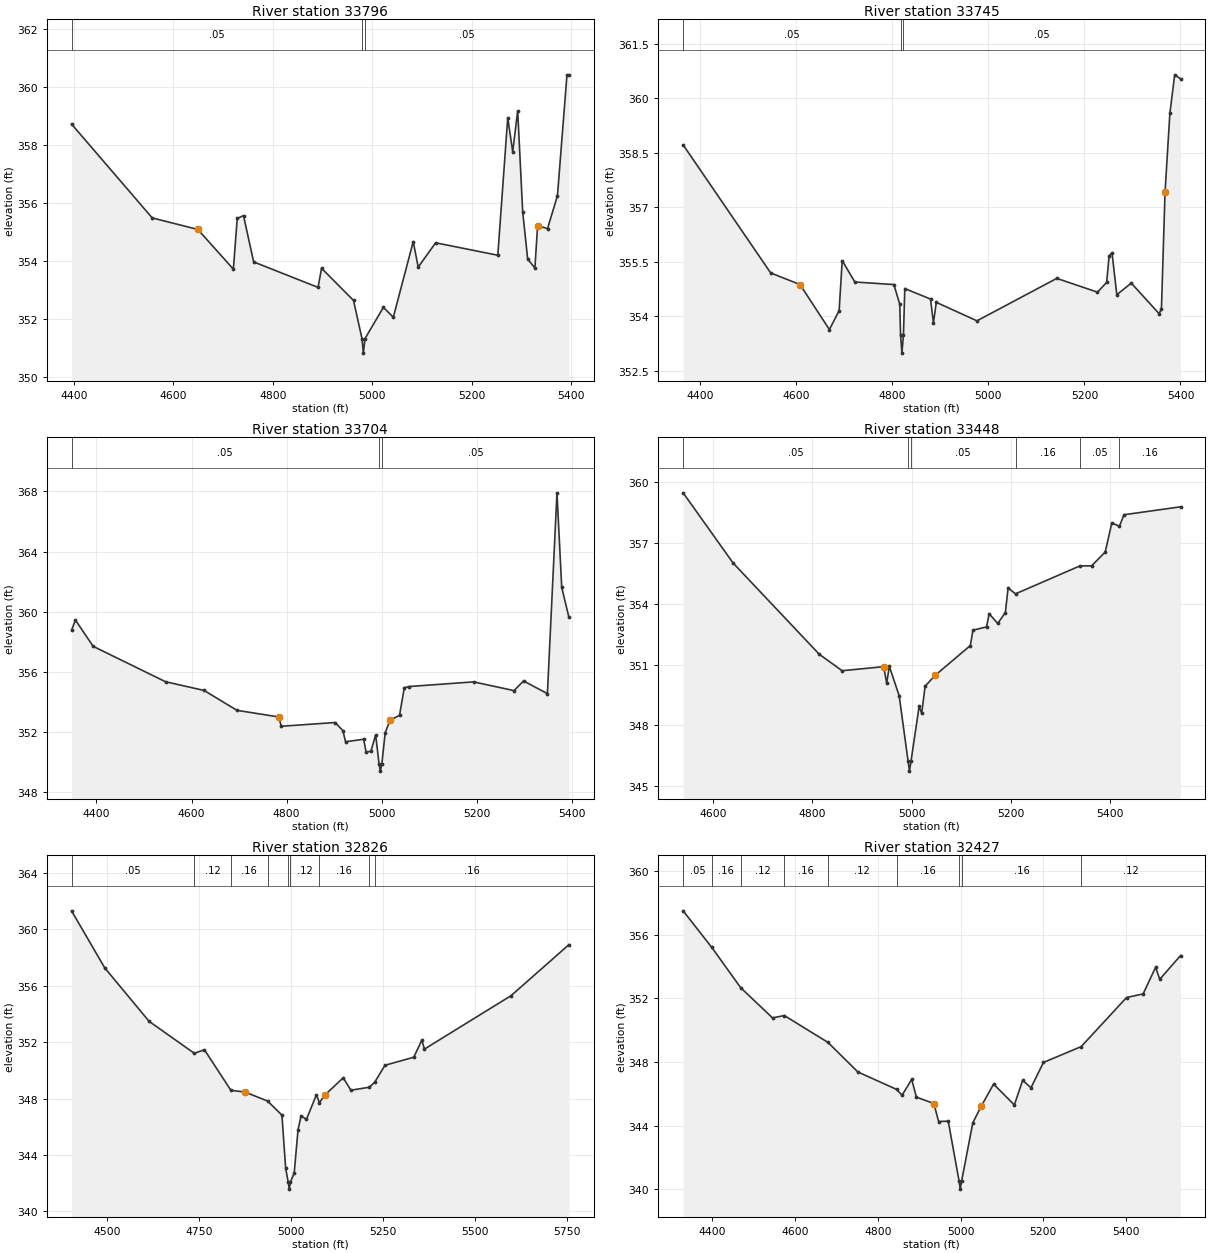
Type RM Length L Ch R = 1 ,33796   ,51,51,51
BEGIN DESCRIPTION:
Mapping XS b7c0ec45
END DESCRIPTION:
XS GIS Cut Line= 5
      3670248.48      10683173.5      3669880.44     10683097.11
       3669873.5     10683003.36       3669816.2     10682946.07
      3669366.58     10682968.64
#Sta/Elev= 30
  4394.9  358.73  4557.2  355.49  4649.1  355.09  4720.6  353.72  4728.4  355.47
    4741  355.57  4761.4  353.97    4891  353.09  4898.1  353.75  4962.4  352.64
  4979.5  351.32  4982.2  350.82  4985.5  351.32  5022.5   352.4  5042.5  352.06
  5082.6  354.67  5092.6  353.79  5127.7  354.63  5252.8   354.2  5272.8  358.95
  5282.8  357.77  5292.8  359.19  5302.9   355.7  5312.9  354.07  5327.5  353.76
  5332.9  355.22  5352.9  355.12  5372.9  356.26    5392  360.43    5396  360.43
#Mann= 3 ,-1 , 0
  4394.9     .05       0  4979.5     .03       0  4985.5     .05       0
Bank Sta=4649.1,5332.9
XS Rating Curve= 0 ,0
Exp/Cntr=0.3,0.1

Type RM Length L Ch R = 1 ,33745   ,41,41,41
BEGIN DESCRIPTION:
UNT 0417 IN LACR 56.0
END DESCRIPTION:
XS GIS Cut Line= 6
      3670248.61     10683147.98      3669910.04     10683082.88
      3669897.45     10682978.36       3669828.7     10682908.22
      3669759.95     10682900.58      3669347.49     10682939.12
#Sta/Elev= 30
  4364.5  358.72  4546.8  355.19  4607.9  354.87    4669  353.63  4689.3  354.15
  4695.7  355.53    4722  354.94  4803.2  354.87  4815.5  354.33  4817.2  353.48
    4820  352.98  4823.2  353.48    4826  354.76  4879.6  354.47  4885.6  353.81
  4891.6  354.38  4976.2  353.87  5142.4  355.04  5227.2  354.66  5246.3  354.93
  5251.3  355.65  5257.4  355.75  5267.4  354.59  5297.5  354.91  5355.3  354.07
  5360.3  354.19  5367.8  357.41  5377.9  359.59  5387.9  360.65  5400.1  360.54
#Mann= 3 ,-1 , 0
  4364.5     .05       0  4817.2     .03       0  4823.2     .05       0
Bank Sta=4607.9,5367.8
XS Rating Curve= 0 ,0
Exp/Cntr=0.3,0.1

Type RM Length L Ch R = 1 ,33704   ,256,256,256
BEGIN DESCRIPTION:
Mapping XS d3ffecc7
END DESCRIPTION:
XS GIS Cut Line= 6
      3670274.53     10683116.21      3669949.88     10683062.39
      3669930.79     10682994.68      3669890.86      10682904.4
      3669784.95     10682857.53      3669354.47     10682890.51
#Sta/Elev= 30
  4347.8  358.76  4355.9  359.45  4393.3   357.7  4545.4  355.35  4626.5  354.77
  4695.5  353.45  4783.4  353.01  4788.8  352.39    4902  352.64  4918.3   352.1
  4923.9  351.36  4961.8  351.53  4967.1  350.68  4977.1  350.73  4987.2  351.82
  4994.2  349.91    4997  349.41  5000.2  349.91  5007.2  351.96  5017.3  352.79
  5037.3  353.12  5047.4  354.95  5057.2  355.03  5192.9  355.34    5278  354.76
  5298.1   355.4  5348.2  354.56  5368.3   367.9  5378.3  361.62  5393.5  359.62
#Mann= 3 ,-1 , 0
  4347.8     .05       0  4994.2     .03       0  5000.2     .05       0
Bank Sta=4783.4,5017.3
XS Rating Curve= 0 ,0
Exp/Cntr=0.3,0.1

Type RM Length L Ch R = 1 ,33448   ,622,622,622
BEGIN DESCRIPTION:
UNT 0417 IN LACR 55.0
END DESCRIPTION:
XS GIS Cut Line= 2
      3670136.23     10682484.11      3669177.11     10682779.23
#Sta/Elev= 30
  4539.1  359.47  4639.9  356.01  4813.8  351.51  4859.9   350.7  4943.6   350.9
  4949.8  350.09  4955.1  350.92    4975  349.46  4992.9  346.25  4995.7  345.75
  4998.9  346.25  5015.2  348.94  5020.4   348.6  5027.3  349.94  5047.9  350.48
  5118.5  351.94  5123.8   352.7  5151.2  352.86  5156.5  353.51  5173.8  353.03
  5189.2  353.57  5194.7  354.78  5209.7  354.49  5339.8  355.87  5363.1  355.87
  5390.6  356.55    5404  357.99  5419.3  357.82  5428.5  358.39  5542.6  358.78
#Mann= 6 ,-1 , 0
  4539.1     .05       0  4992.9     .03       0  4998.9     .05       0
  5209.7     .16       0  5339.8     .05       0  5419.3     .16       0
Bank Sta=4943.6,5047.9
XS Rating Curve= 0 ,0
Exp/Cntr=0.3,0.1

Type RM Length L Ch R = 1 ,32826   ,399,399,399
BEGIN DESCRIPTION:
UNT 0417 IN LACR 54.0
END DESCRIPTION:
XS GIS Cut Line= 3
      3670149.57     10682010.19      3669549.61     10682060.19
      3669099.63     10682660.16
#Sta/Elev= 30
  4403.7  361.32    4494  357.27  4614.4  353.48  4737.3  351.21  4764.9  351.46
  4836.9  348.58  4875.3  348.46  4936.6  347.82  4975.6  346.82  4985.7  343.04
  4992.7  342.07  4995.5  341.57  4998.7  342.07  5008.9  342.71  5019.3  345.78
  5027.6  346.77  5042.2  346.52  5069.3  348.27  5077.4   347.7  5092.2  348.25
  5142.2  349.47    5163  348.59  5212.7   348.8  5227.3  349.14  5255.7  350.36
  5333.9  350.93  5355.7  352.14    5363  351.51  5598.4   355.3  5755.7  358.92
#Mann= 9 ,-1 , 0
  4403.7     .05       0  4737.3     .12       0  4836.9     .16       0
  4936.6     .12       0  4992.7     .07       0  4998.7     .12       0
  5077.4     .16       0  5212.7     .12       0  5227.3     .16       0
Bank Sta=4875.3,5092.2
XS Rating Curve= 0 ,0
Exp/Cntr=0.3,0.1

Type RM Length L Ch R = 1 ,32427   ,260,260,260
BEGIN DESCRIPTION:
UNT 0417 IN LACR 53.0
END DESCRIPTION:
XS GIS Cut Line= 3
       3670049.6     10681960.19      3669449.61     10681710.19
      3668899.57     10681760.19
#Sta/Elev= 30
  4329.5   357.5  4398.5  355.21  4468.6  352.67  4545.6  350.77  4574.1  350.92
  4679.6  349.23    4752  347.37  4845.3  346.28  4858.7  345.91    4882  346.91
  4893.4  345.79  4935.6  345.39    4947  344.26  4970.3  344.28  4996.6  340.51
  4999.3  340.01  5002.6  340.51  5029.7  344.18  5049.8  345.21  5079.9  346.61
  5130.1   345.3  5150.2  346.85  5170.3  346.38  5200.4  347.97  5291.8  348.97
  5401.2  352.05  5441.4  352.28  5471.5  353.95  5481.6   353.2  5531.8  354.69
#Mann= 9 ,-1 , 0
  4329.5     .05       0  4398.5     .16       0  4468.6     .12       0
  4574.1     .16       0  4679.6     .12       0  4845.3     .16       0
  4996.6     .07       0  5002.6     .16       0  5291.8     .12       0
Bank Sta=4935.6,5049.8
XS Rating Curve= 0 ,0
Exp/Cntr=0.3,0.1

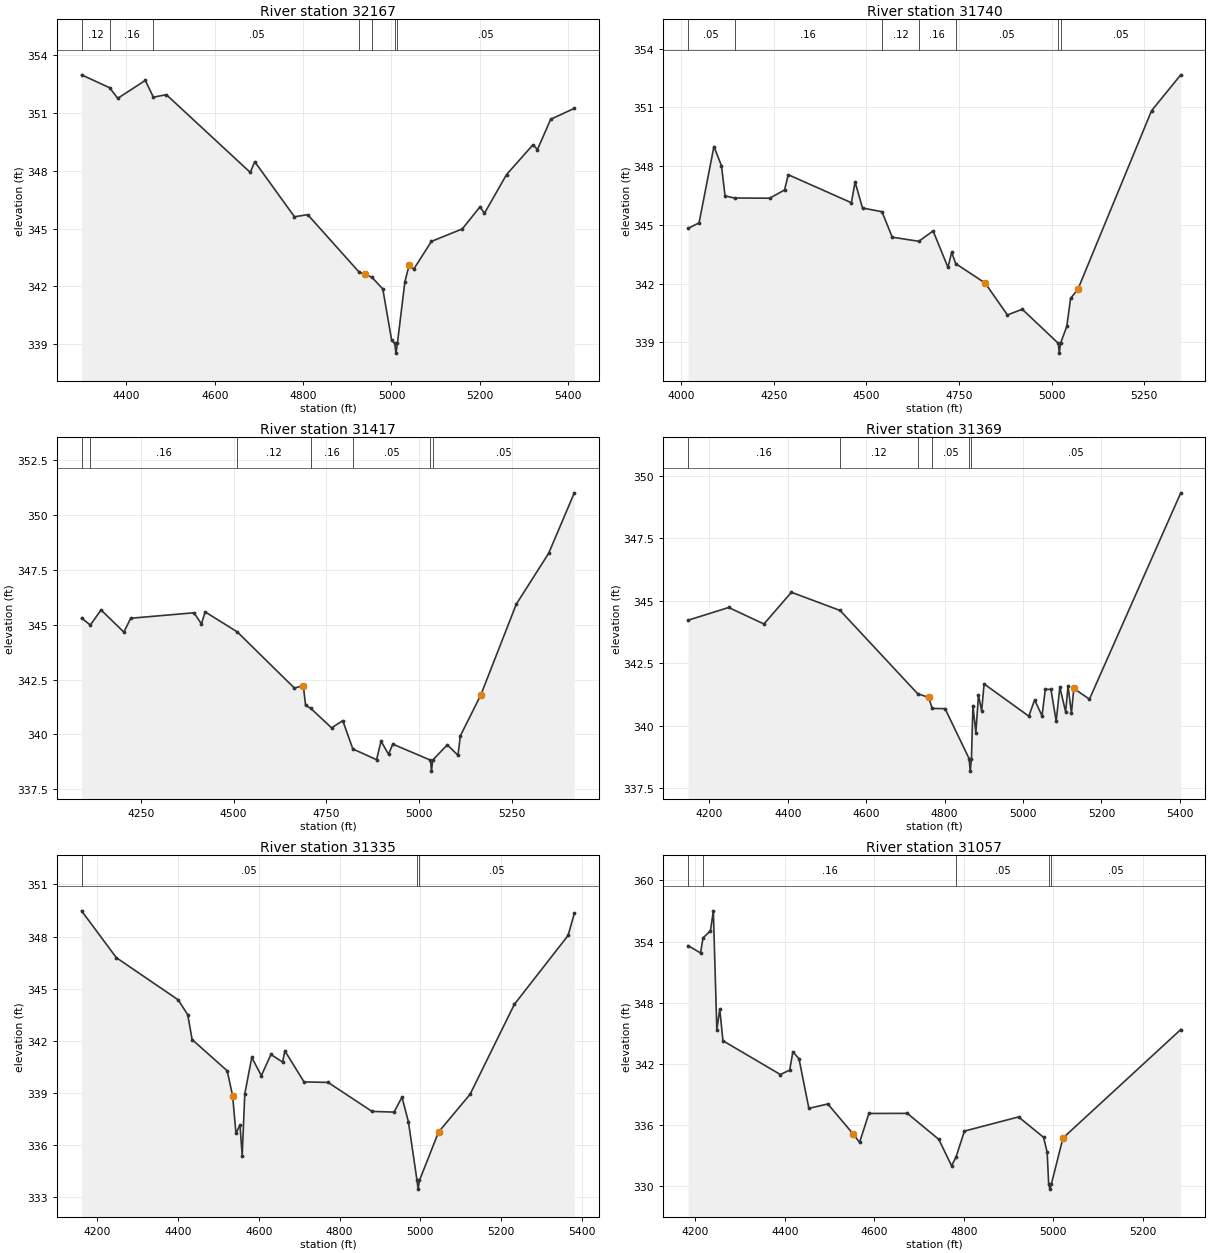
Type RM Length L Ch R = 1 ,32167   ,427,427,427
BEGIN DESCRIPTION:
UNT 0417 IN LACR 52.0
END DESCRIPTION:
XS GIS Cut Line= 2
      3670101.59     10681442.43       3668986.1     10681464.14
#Sta/Elev= 30
  4298.3  352.99  4361.8  352.32  4380.3  351.77  4442.6   352.7  4460.9  351.83
  4490.3  351.96  4680.4  347.92  4690.4  348.48  4780.4  345.62  4810.4  345.73
  4927.4  342.73  4940.4  342.64  4956.1  342.47  4980.4  341.87  5000.4  339.21
  5007.4  339.04  5010.2  338.54  5013.4  339.04  5030.4  342.25  5040.4  343.14
  5050.4   342.9  5090.4  344.34  5160.4  344.99  5200.5  346.14  5210.5   345.8
  5260.5  347.81  5320.5  349.36  5330.5  349.11  5360.5  350.68    5414  351.25
#Mann= 7 ,-1 , 0
  4298.3     .12       0  4361.8     .16       0  4460.9     .05       0
  4927.4     .16       0  4956.1     .05       0  5007.4     .03       0
  5013.4     .05       0
Bank Sta=4940.4,5040.4
XS Rating Curve= 0 ,0
Exp/Cntr=0.3,0.1

Type RM Length L Ch R = 1 ,31740   ,323,323,323
BEGIN DESCRIPTION:
UNT 0417 IN LACR 51.0
END DESCRIPTION:
XS GIS Cut Line= 2
      3670379.35     10680969.34      3669052.87     10681060.38
#Sta/Elev= 30
  4018.8  344.82  4048.6   345.1  4088.7     349    4109  348.02  4118.8  346.48
  4144.4  346.37  4239.1  346.36  4279.2  346.78  4289.2  347.56  4459.6  346.13
  4469.6  347.19  4489.6  345.86  4542.2  345.67  4569.8  344.37  4641.6  344.16
  4680.1  344.69  4720.2  342.83  4730.2   343.6  4741.1  343.02  4820.4  342.03
  4880.6   340.4  4920.7  340.69  5017.9  338.95  5020.6  338.45  5023.9  338.95
  5040.9  339.82    5051  341.24    5071  341.72  5269.6  350.83  5348.4  352.66
#Mann= 7 ,-1 , 0
  4018.8     .05       0  4144.4     .16       0  4542.2     .12       0
  4641.6     .16       0  4741.1     .05       0  5017.9     .03       0
  5023.9     .05       0
Bank Sta=4820.4,5071
XS Rating Curve= 0 ,0
Exp/Cntr=0.3,0.1

Type RM Length L Ch R = 1 ,31417   ,48,48,48
BEGIN DESCRIPTION:
Mapping XS de0d851b
END DESCRIPTION:
XS GIS Cut Line= 6
       3670281.9       10680872.      3669524.13     10680825.12
      3669469.45     10680726.17      3669427.78     10680733.98
      3669352.26      10680812.1      3669074.06      10680903.1
#Sta/Elev= 30
  4090.7   345.3  4114.4  344.98  4143.1  345.67  4204.6  344.66  4223.2  345.29
  4393.6  345.54  4413.6  345.03  4423.6  345.58    4510  344.67  4664.1  342.11
    4688  342.22  4694.1  341.33  4707.8  341.19  4764.3   340.3  4794.3  340.63
  4821.4  339.34  4885.3  338.85  4897.4  339.69  4917.6   339.1    4929  339.56
  5030.5  338.83  5033.3  338.33  5036.5  338.83  5075.9  339.53  5104.6  339.05
  5111.1  339.94  5166.2   341.8  5261.7  345.93    5349  348.25    5418     351
#Mann= 7 ,-1 , 0
  4090.7     .05       0  4114.4     .16       0    4510     .12       0
  4707.8     .16       0  4821.4     .05       0  5030.5     .03       0
  5036.5     .05       0
Bank Sta=4688,5166.2
XS Rating Curve= 0 ,0
Exp/Cntr=0.3,0.1

Type RM Length L Ch R = 1 ,31369   ,34,34,34
BEGIN DESCRIPTION:
Mapping XS 8a9ea4ff
END DESCRIPTION:
XS GIS Cut Line= 6
      3670253.29     10680801.69      3669571.01     10680780.85
      3669446.01     10680681.89      3669393.93     10680689.71
      3669341.84     10680778.25      3669099.68     10680853.76
#Sta/Elev= 30
  4145.6  344.22  4249.3  344.73  4339.3  344.07  4409.3  345.34  4533.6  344.61
  4731.3  341.28  4759.4  341.13  4768.5  340.69  4801.3  340.68  4862.6  338.68
  4865.4  338.18  4868.6  338.68  4872.3   340.8  4879.8  339.72  4886.5  341.22
  4894.6  340.59  4900.8  341.67  5014.9  340.38  5029.7  341.03  5048.6  340.39
    5057  341.46  5071.3  341.45  5084.7  340.18    5094  341.54  5108.8  340.55
  5114.9  341.59  5123.6   340.5  5129.7  341.49  5169.5  341.06  5402.5  349.32
#Mann= 6 ,-1 , 0
  4145.6     .16       0  4533.6     .12       0  4731.3     .16       0
  4768.5     .05       0  4862.6     .03       0  4868.6     .05       0
Bank Sta=4759.4,5129.7
XS Rating Curve= 0 ,0
Exp/Cntr=0.3,0.1

Type RM Length L Ch R = 1 ,31335   ,278,278,278
BEGIN DESCRIPTION:
Mapping XS 18ba804d
END DESCRIPTION:
XS GIS Cut Line= 5
      3670211.67     10680340.73       3669503.3     10680640.23
       3669375.7     10680655.85      3669318.41      10680684.5
       3669085.7     10680795.68
#Sta/Elev= 30
  4161.5  349.48  4247.6  346.78  4400.6  344.35  4424.3  343.49  4435.2  342.06
    4522  340.26  4535.4  338.82  4543.7  336.66  4553.6  337.14  4559.1  335.37
  4565.5  338.93  4582.8  341.03  4606.5  339.98  4630.2   341.2  4659.3  340.76
  4664.7  341.41  4712.1  339.62  4771.7  339.59  4880.3  337.92    4935  337.88
  4954.5  338.74  4970.5  337.32  4991.8  333.94  4994.5  333.44  4997.8  333.94
  5045.1  336.73  5123.2  338.91  5232.7  344.09  5365.7  348.06  5381.1  349.33
#Mann= 3 ,-1 , 0
  4161.5     .05       0  4991.8     .03       0  4997.8     .05       0
Bank Sta=4535.4,5045.1
XS Rating Curve= 0 ,0
Exp/Cntr=0.3,0.1

Type RM Length L Ch R = 1 ,31057   ,453,453,453
BEGIN DESCRIPTION:
UNT 0417 IN LACR 50.0
END DESCRIPTION:
XS GIS Cut Line= 3
      3669799.61     10679810.19      3669299.61     10680410.19
       3669099.6      10680660.2
#Sta/Elev= 30
  4183.6   353.6  4211.6  352.88  4217.1  354.35  4233.7  355.05  4240.2  357.01
    4248  345.34  4254.5  347.37  4261.7  344.27  4389.9  340.96  4410.8  341.39
  4417.9  343.19  4431.6   342.5  4453.7  337.64    4496  338.07  4552.6  335.13
    4567   334.3  4587.8  337.14  4673.7  337.15    4744   334.6  4772.6  332.01
  4782.4  332.85  4801.3  335.41  4922.3   336.8  4978.2   334.8  4986.2  333.33
  4989.6  330.22  4992.4  329.72  4995.6  330.22  5021.5  334.73  5284.8  345.37
#Mann= 5 ,-1 , 0
  4183.6     .05       0  4217.1     .16       0  4782.4     .05       0
  4989.6     .03       0  4995.6     .05       0
Bank Sta=4552.6,5021.5
XS Rating Curve= 0 ,0
Exp/Cntr=0.3,0.1

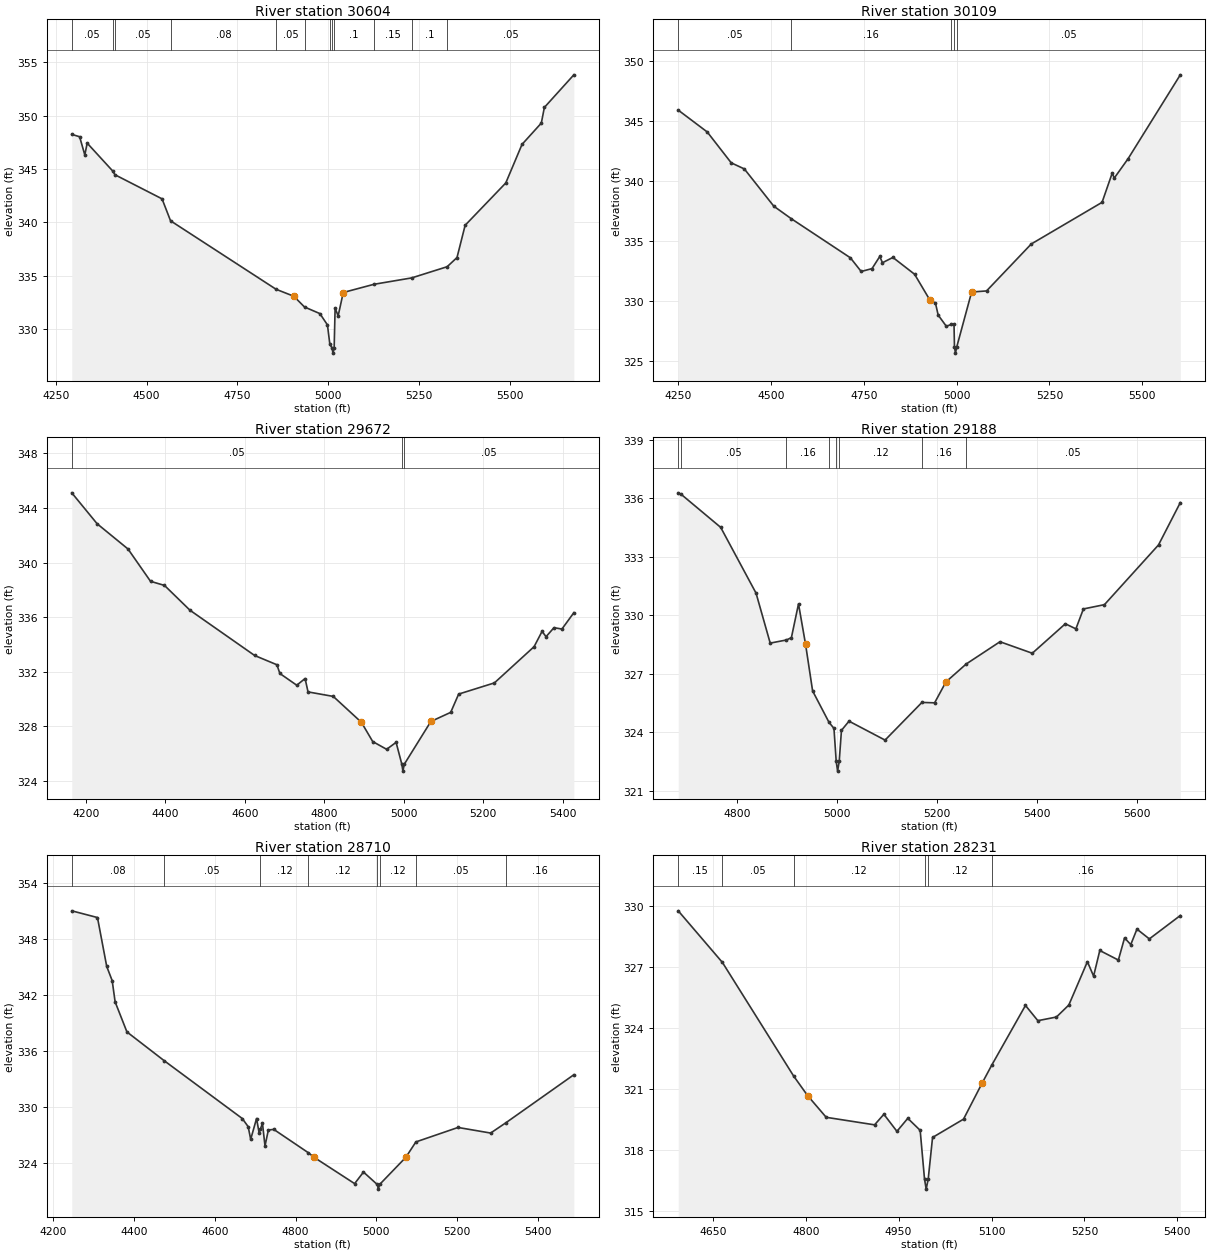
Type RM Length L Ch R = 1 ,30604   ,495,495,495
BEGIN DESCRIPTION:
UNT 0417 IN LACR 49.0
END DESCRIPTION:
XS GIS Cut Line= 3
      3669599.63     10679610.18      3669049.61     10680060.19
       3668749.6     10680660.21
#Sta/Elev= 30
  4294.3  348.25  4315.9  348.03  4330.2  346.32  4336.7  347.43  4406.5  344.83
  4413.2  344.46  4542.7   342.2  4566.1  340.14  4856.6  333.71  4905.2  333.06
  4934.7  332.05    4977  331.43  4997.8  330.37  5004.5  328.53  5010.3  328.22
  5013.1  327.72  5016.3  328.22  5018.9  331.94  5027.3  331.22  5041.3  333.41
  5125.8  334.18  5229.6  334.78  5327.2  335.83  5354.3  336.69  5376.7  339.72
  5488.5  343.69  5533.2  347.31  5586.3  349.31  5594.7  350.78  5675.8  353.84
#Mann= 12 ,-1 , 0
  4294.3     .05       0  4406.5     .08       0  4413.2     .05       0
  4566.1     .08       0  4856.6     .05       0  4934.7     .08       0
  5004.5      .1       0  5010.3     .07       0  5016.3      .1       0
  5125.8     .15       0  5229.6      .1       0  5327.2     .05       0
Bank Sta=4905.2,5041.3
XS Rating Curve= 0 ,0
Exp/Cntr=0.3,0.1

Type RM Length L Ch R = 1 ,30109   ,437,437,437
BEGIN DESCRIPTION:
UNT 0417 IN LACR 48.0
END DESCRIPTION:
XS GIS Cut Line= 3
      3669149.62     10679360.18      3668699.61     10679960.19
      3668649.61      10680560.2
#Sta/Elev= 30
  4250.5  345.89  4328.6  344.07  4393.2   341.5  4428.6  340.99  4507.8  337.89
  4554.3  336.86  4714.1  333.59  4743.2  332.45  4772.4  332.69  4793.2   333.7
  4800.5  333.18  4828.6  333.62    4887  332.22  4928.6  330.05  4943.2  329.82
  4950.5  328.82  4972.4  327.89    4986  328.04  4993.2  328.04  4994.4  326.15
  4997.1  325.65  5000.4  326.15  5040.6  330.74  5080.8  330.83  5201.2  334.74
  5391.9  338.21  5419.5  340.67  5424.5  340.22  5462.1  341.85  5602.6  348.83
#Mann= 5 ,-1 , 0
  4250.5     .05       0  4554.3     .16       0    4986     .05       0
  4994.4     .03       0  5000.4     .05       0
Bank Sta=4928.6,5040.6
XS Rating Curve= 0 ,0
Exp/Cntr=0.3,0.1

Type RM Length L Ch R = 1 ,29672   ,484,484,484
BEGIN DESCRIPTION:
UNT 0417 IN LACR 47.0
END DESCRIPTION:
XS GIS Cut Line= 3
      3668949.65     10679210.16      3668349.61     10679760.19
      3668349.61      10680210.2
#Sta/Elev= 30
  4164.2  345.11  4228.1  342.84  4305.8  340.99  4362.5  338.62  4397.6  338.32
  4461.8   336.5  4624.6  333.18  4680.7   332.5  4688.1  331.86  4730.6     331
  4751.6  331.49    4759  330.51  4822.5  330.18  4893.4  328.28  4921.8  326.87
  4956.9   326.3  4980.7  326.81  4995.2   325.2  4997.9   324.7  5001.2   325.2
  5068.2  328.34  5118.2  329.01  5138.2  330.35  5228.2  331.17  5328.2  333.83
  5348.2  334.95  5358.2  334.56  5378.2  335.22  5398.2  335.12  5428.2  336.32
#Mann= 3 ,-1 , 0
  4164.2     .05       0  4995.2     .03       0  5001.2     .05       0
Bank Sta=4893.4,5068.2
XS Rating Curve= 0 ,0
Exp/Cntr=0.3,0.1

Type RM Length L Ch R = 1 ,29188   ,478,478,478
BEGIN DESCRIPTION:
UNT 0417 IN LACR 46.0
END DESCRIPTION:
XS GIS Cut Line= 3
      3668349.63     10679160.16      3668149.61     10679360.19
       3667749.6      10679960.2
#Sta/Elev= 30
  4682.4  336.28  4688.4   336.2  4767.3  334.51    4838  331.14  4866.3  328.58
  4898.8  328.74  4908.7  328.86  4922.9  330.59    4937  328.52  4951.1  326.13
  4983.9  324.52  4993.8  324.21  4998.3  322.52  5001.1  322.02  5004.3  322.52
  5008.8  324.11  5023.9  324.58    5096  323.61  5169.7  325.54  5195.1  325.52
  5217.7  326.59  5258.3  327.51  5325.8  328.65  5390.4  328.06  5456.5  329.57
  5477.6  329.31  5492.6  330.33  5534.7  330.55  5642.8  333.61  5686.4  335.78
#Mann= 8 ,-1 , 0
  4682.4     .16       0  4688.4     .05       0  4898.8     .16       0
  4983.9     .12       0  4998.3     .07       0  5004.3     .12       0
  5169.7     .16       0  5258.3     .05       0
Bank Sta=4937,5217.7
XS Rating Curve= 0 ,0
Exp/Cntr=0.3,0.1

Type RM Length L Ch R = 1 ,28710   ,479,479,479
BEGIN DESCRIPTION:
UNT 0417 IN LACR 45.0
END DESCRIPTION:
XS GIS Cut Line= 3
      3668199.64     10678760.15      3667749.61     10679360.19
      3667549.61      10679810.2
#Sta/Elev= 30
  4246.3  351.02  4309.9   350.3  4332.8  345.06  4346.3  343.54  4353.6  341.26
  4382.8  338.04  4474.9  334.96  4668.2  328.76  4682.8  327.89  4689.1  326.53
  4703.6  328.76  4709.9  327.23    4713  327.61  4718.2  328.24  4724.5  325.82
  4732.8  327.53  4746.3  327.59  4832.1  325.08  4846.3  324.59  4946.3  321.78
  4968.2  323.02  5002.2  321.69    5005  321.19  5008.2  321.69    5073   324.6
  5097.9  326.25  5202.2   327.8  5282.9   327.2  5321.5  328.33  5488.8  333.45
#Mann= 8 ,-1 , 0
  4246.3     .08       0  4474.9     .05       0    4713     .12       0
  4832.1     .12       0  5002.2     .07       0  5008.2     .12       0
  5097.9     .05       0  5321.5     .16       0
Bank Sta=4846.3,5073
XS Rating Curve= 0 ,0
Exp/Cntr=0.3,0.1

Type RM Length L Ch R = 1 ,28231   ,115,115,115
BEGIN DESCRIPTION:
UNT 0417 IN LACR 44.0
END DESCRIPTION:
XS GIS Cut Line= 3
      3667549.62     10678960.17      3667349.61     10679260.19
      3667349.61     10679710.21
#Sta/Elev= 30
  4594.2  329.74  4665.6   327.2  4780.5  321.62    4803  320.66  4833.1  319.59
  4911.2  319.22  4926.2  319.74  4947.3   318.9  4964.8  319.54  4984.8  318.95
  4991.8  316.56  4994.5  316.06  4997.8  316.56  5004.8   318.6  5054.8   319.5
  5084.8  321.27  5100.1  322.14  5154.8  325.09  5174.8  324.34  5204.8  324.52
  5224.8  325.11  5254.8  327.24  5264.8  326.53  5274.8  327.79  5304.8  327.32
  5314.8  328.41  5324.8  328.08  5334.8  328.84  5354.8  328.36  5404.8  329.51
#Mann= 6 ,-1 , 0
  4594.2     .15       0  4665.6     .05       0  4780.5     .12       0
  4991.8     .07       0  4997.8     .12       0  5100.1     .16       0
Bank Sta=4803,5084.8
XS Rating Curve= 0 ,0
Exp/Cntr=0.3,0.1