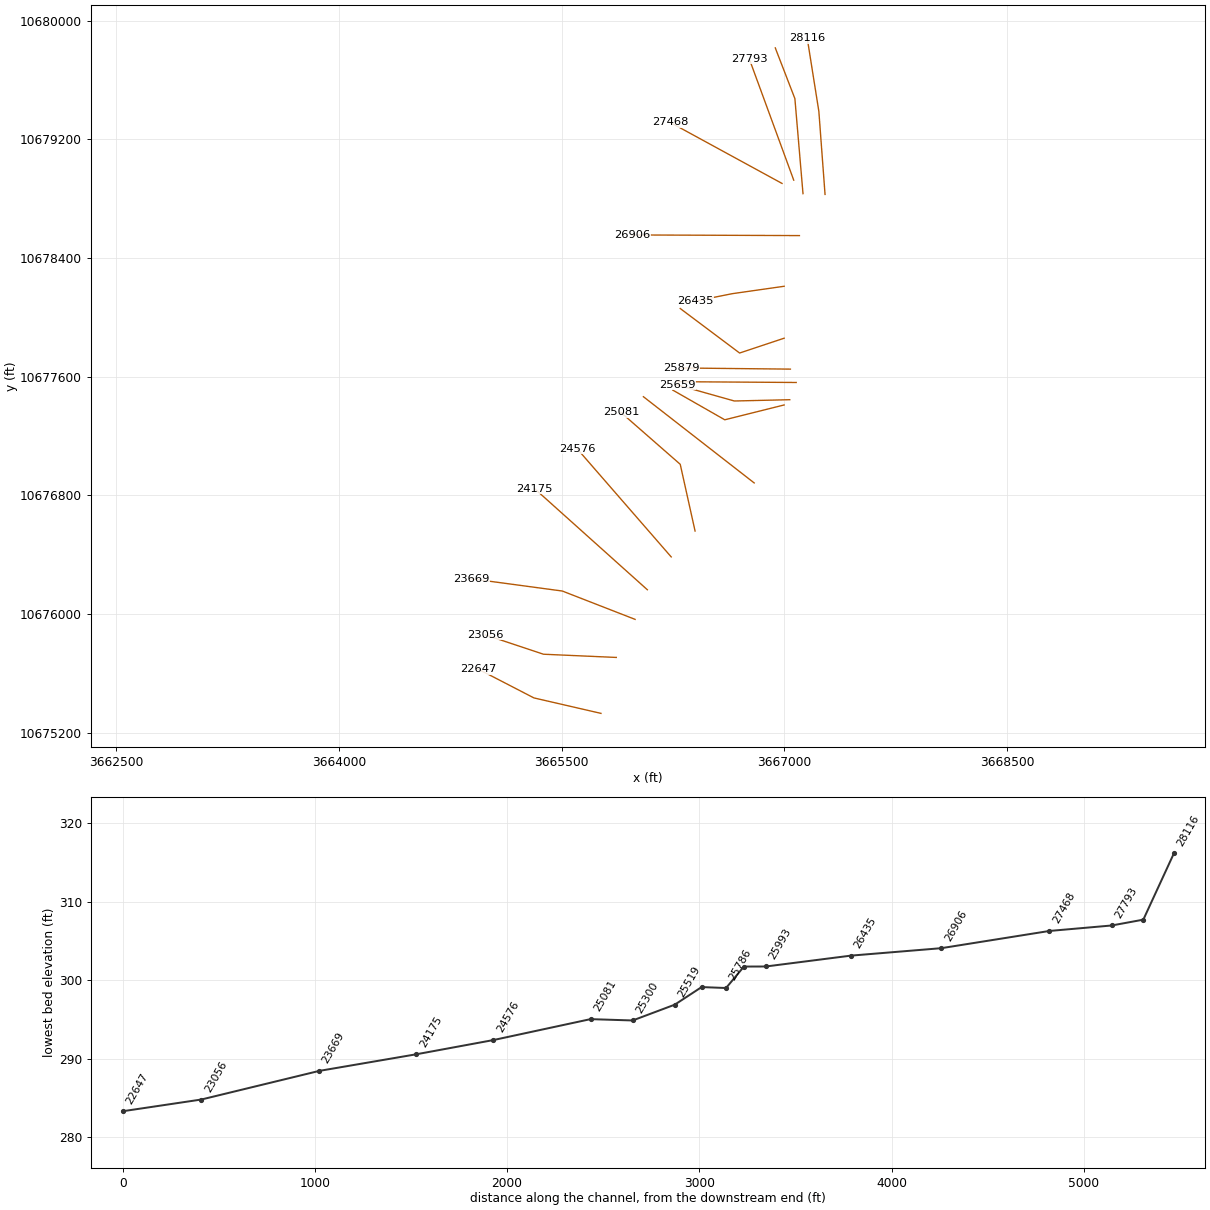
HEC-RAS study UNT 0417 IN LACR.prj: UNT 0417 IN LACR Base Level Engineering

--- UNT 0417 IN LACR.g01 (geometry) --- (continued)

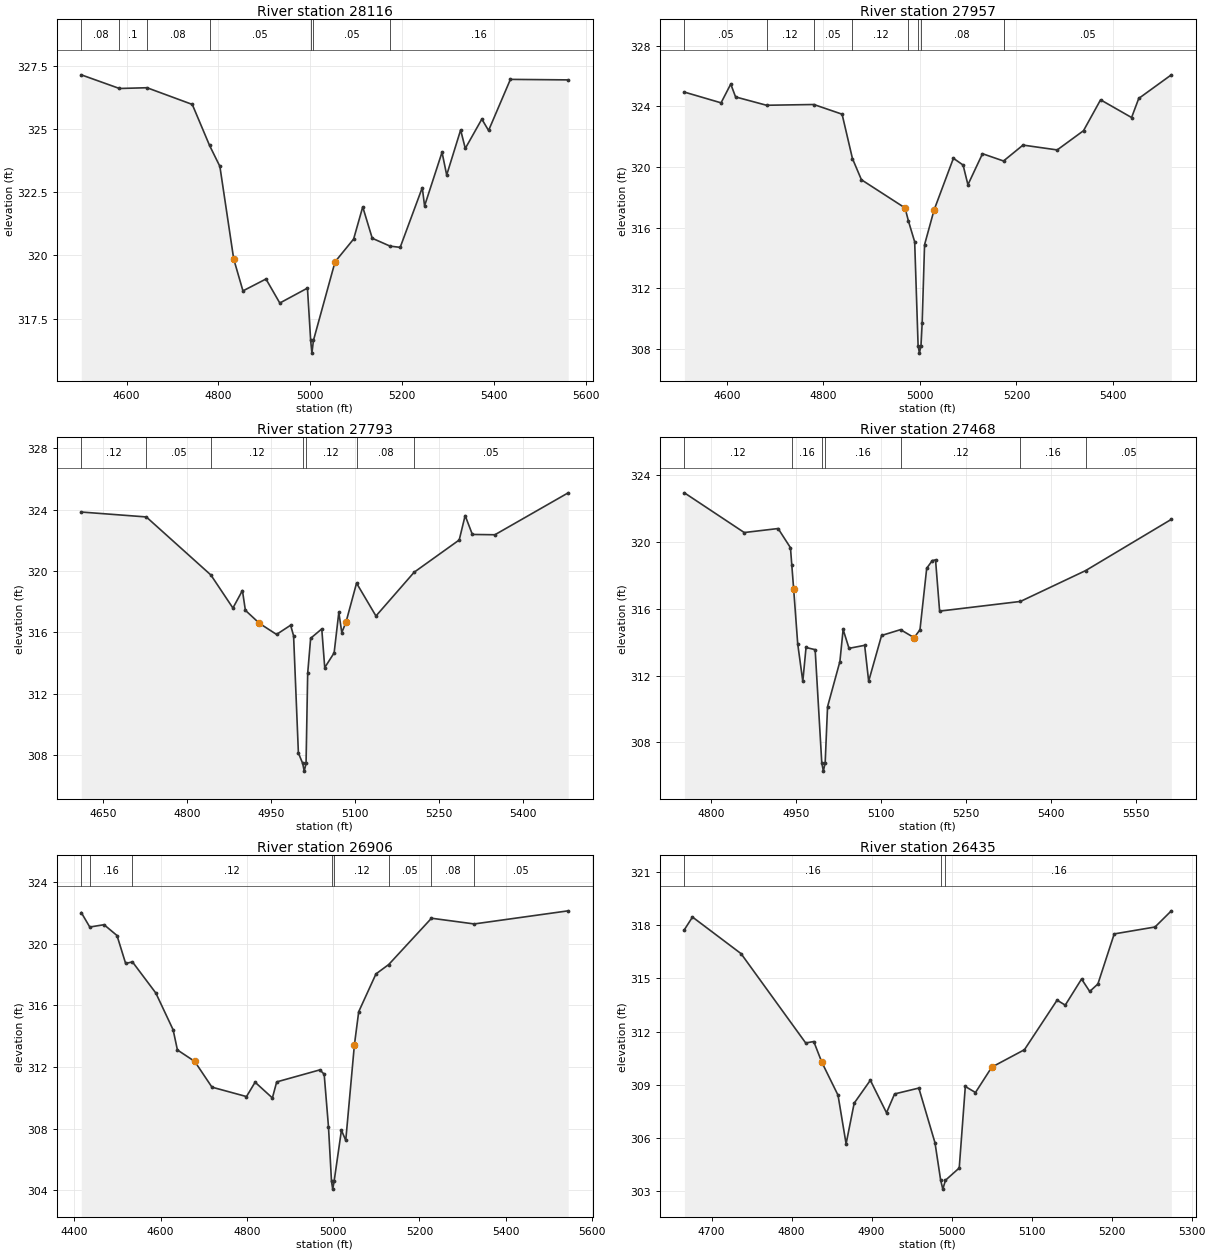
Type RM Length L Ch R = 1 ,28116   ,159,159,159
BEGIN DESCRIPTION:
Mapping XS d1054359
END DESCRIPTION:
XS GIS Cut Line= 3
        3667275.     10678829.28      3667233.34     10679389.14
       3667155.2     10679881.37
#Sta/Elev= 30
  4501.5  327.14  4584.6   326.6  4644.6  326.63  4743.1  325.97  4780.7  324.35
  4803.2  323.52  4833.3  319.86  4853.4   318.6  4903.5  319.07  4933.6  318.12
  4993.8  318.71  5000.8  316.64  5003.5  316.14  5006.8  316.64  5053.9  319.75
  5094.3  320.65  5114.1  321.92  5134.8  320.68  5173.5  320.37  5195.6  320.32
  5243.7  322.68  5248.7  321.96  5286.7  324.08  5296.8  323.18  5327.2  324.96
  5337.3  324.23  5373.3  325.39    5388  324.94  5435.5  326.96  5561.3  326.94
#Mann= 7 ,-1 , 0
  4501.5     .08       0  4584.6      .1       0  4644.6     .08       0
  4780.7     .05       0  5000.8     .04       0  5006.8     .05       0
  5173.5     .16       0
Bank Sta=4833.3,5053.9
XS Rating Curve= 0 ,0
Exp/Cntr=0.3,0.1

Type RM Length L Ch R = 1 ,27957   ,164,164,164
BEGIN DESCRIPTION:
UNT 0417 IN LACR 43.0
END DESCRIPTION:
XS GIS Cut Line= 3
      3667126.56     10678834.47      3667071.88     10679475.08
      3666939.77     10679817.01
#Sta/Elev= 30
  4511.7  324.95  4587.7  324.24  4607.8  325.48  4617.8  324.63    4682  324.08
    4780  324.13  4838.6  323.49  4860.1  320.56  4878.7  319.16  4969.1   317.3
  4976.2  316.43  4989.1  315.06  4996.2  308.21  4998.9  307.71  5002.2  308.21
  5004.6  309.68  5009.6  314.87  5029.3  317.16  5069.4  320.58  5089.5  320.13
  5099.5  318.83  5129.7  320.88  5173.3   320.4  5213.7  321.45  5284.6  321.13
  5339.1   322.4  5374.5  324.44  5438.8  323.27  5453.6  324.53  5521.2  326.09
#Mann= 8 ,-1 , 0
  4511.7     .05       0    4682     .12       0    4780     .05       0
  4860.1     .12       0  4976.2     .08       0  4996.2     .07       0
  5002.2     .08       0  5173.3     .05       0
Bank Sta=4969.1,5029.3
XS Rating Curve= 0 ,0
Exp/Cntr=0.3,0.1

Type RM Length L Ch R = 1 ,27793   ,325,325,325
BEGIN DESCRIPTION:
Mapping XS 1657ae83
END DESCRIPTION:
XS GIS Cut Line= 2
      3667064.08     10678925.56      3666764.61     10679743.25
#Sta/Elev= 30
  4610.3  323.84  4726.6  323.52  4842.1  319.74  4881.5  317.59  4898.5  318.73
  4903.8  317.44    4929  316.59  4959.5  315.87  4984.7  316.47    4990  315.78
  4998.6  308.15  5006.3  307.47    5009  306.97  5012.3  307.47  5015.2  313.33
  5020.5  315.62  5040.4  316.23  5045.7  313.71  5062.5  314.67  5070.9  317.31
  5076.2  315.99  5083.8  316.68  5102.6  319.21  5137.3  317.07  5205.6  319.92
  5286.2  322.02  5296.8  323.61  5309.7  322.38    5350  322.36  5481.1  325.09
#Mann= 7 ,-1 , 0
  4610.3     .12       0  4726.6     .05       0  4842.1     .12       0
  5006.3     .07       0  5012.3     .12       0  5102.6     .08       0
  5205.6     .05       0
Bank Sta=4929,5083.8
XS Rating Curve= 0 ,0
Exp/Cntr=0.3,0.1

Type RM Length L Ch R = 1 ,27468   ,562,562,562
BEGIN DESCRIPTION:
UNT 0417 IN LACR 42.0
END DESCRIPTION:
XS GIS Cut Line= 2
      3666985.22     10678903.38      3666230.48     10679315.45
#Sta/Elev= 30
  4753.2  322.95  4858.9  320.57  4918.7  320.81  4940.5  319.66  4942.8  318.65
  4946.2  317.16  4953.3   313.9  4962.3  311.65    4968  313.68  4984.1  313.55
  4995.8  306.77  4998.6  306.27  5001.8  306.77    5006  310.13  5027.8  312.84
  5033.5  314.76  5043.9  313.63  5071.5  313.81  5078.6  311.66  5101.4   314.4
  5134.9  314.75  5158.8  314.27  5169.2  314.74  5181.1  318.43    5191  318.89
  5196.7  318.93  5203.9  315.86  5346.6  316.44  5461.8  318.29  5613.1  321.36
#Mann= 7 ,-1 , 0
  4753.2     .12       0  4942.8     .16       0  4995.8     .07       0
  5001.8     .16       0  5134.9     .12       0  5346.6     .16       0
  5461.8     .05       0
Bank Sta=4946.2,5158.8
XS Rating Curve= 0 ,0
Exp/Cntr=0.3,0.1

Type RM Length L Ch R = 1 ,26906   ,471,471,471
BEGIN DESCRIPTION:
UNT 0417 IN LACR 41.0
END DESCRIPTION:
XS GIS Cut Line= 2
      3667102.45     10678551.81      3665974.26     10678556.15
#Sta/Elev= 30
  4416.4  322.01  4436.1  321.07  4469.2  321.22  4499.2  320.52  4519.2  318.71
    4535  318.81  4589.2  316.79  4629.2  314.41  4639.2   313.1  4679.2  312.36
  4719.2  310.69  4799.2  310.08  4819.2  311.01  4859.2  309.99  4869.2  311.03
  4969.2  311.81  4979.2  311.53  4989.2  308.11  4996.2  304.58    4999  304.08
  5002.2  304.58  5019.2   307.9  5029.2  307.24  5049.2  313.42  5059.2  315.58
  5099.2  318.03  5128.8  318.64  5227.8  321.64  5326.8  321.27  5544.6  322.12
#Mann= 8 ,-1 , 0
  4416.4     .05       0  4436.1     .16       0    4535     .12       0
  4996.2     .07       0  5002.2     .12       0  5128.8     .05       0
  5227.8     .08       0  5326.8     .05       0
Bank Sta=4679.2,5049.2
XS Rating Curve= 0 ,0
Exp/Cntr=0.3,0.1

Type RM Length L Ch R = 1 ,26435   ,442,442,442
BEGIN DESCRIPTION:
UNT 0417 IN LACR 40.0
END DESCRIPTION:
XS GIS Cut Line= 3
      3666999.65      10678210.2      3666649.61     10678160.19
      3666399.56     10678110.18
#Sta/Elev= 30
    4666  317.74  4676.1  318.45  4736.8  316.39  4817.6  311.36  4827.7  311.44
  4837.8  310.27    4858  308.42  4868.1  305.68  4878.2  307.97  4898.4  309.26
  4918.6  307.43  4928.7  308.49    4959  308.82  4979.2  305.74  4986.3  303.63
    4989  303.13  4992.3  303.63  5009.5  304.32  5017.1  308.91  5029.8  308.57
  5050.2     310    5091  310.98  5131.8  313.77    5142  313.49  5162.4  314.96
  5172.6  314.26  5182.8  314.68  5203.2   317.5  5254.2  317.89  5274.6   318.8
#Mann= 3 ,-1 , 0
    4666     .16       0  4986.3     .07       0  4992.3     .16       0
Bank Sta=4837.8,5050.2
XS Rating Curve= 0 ,0
Exp/Cntr=0.3,0.1

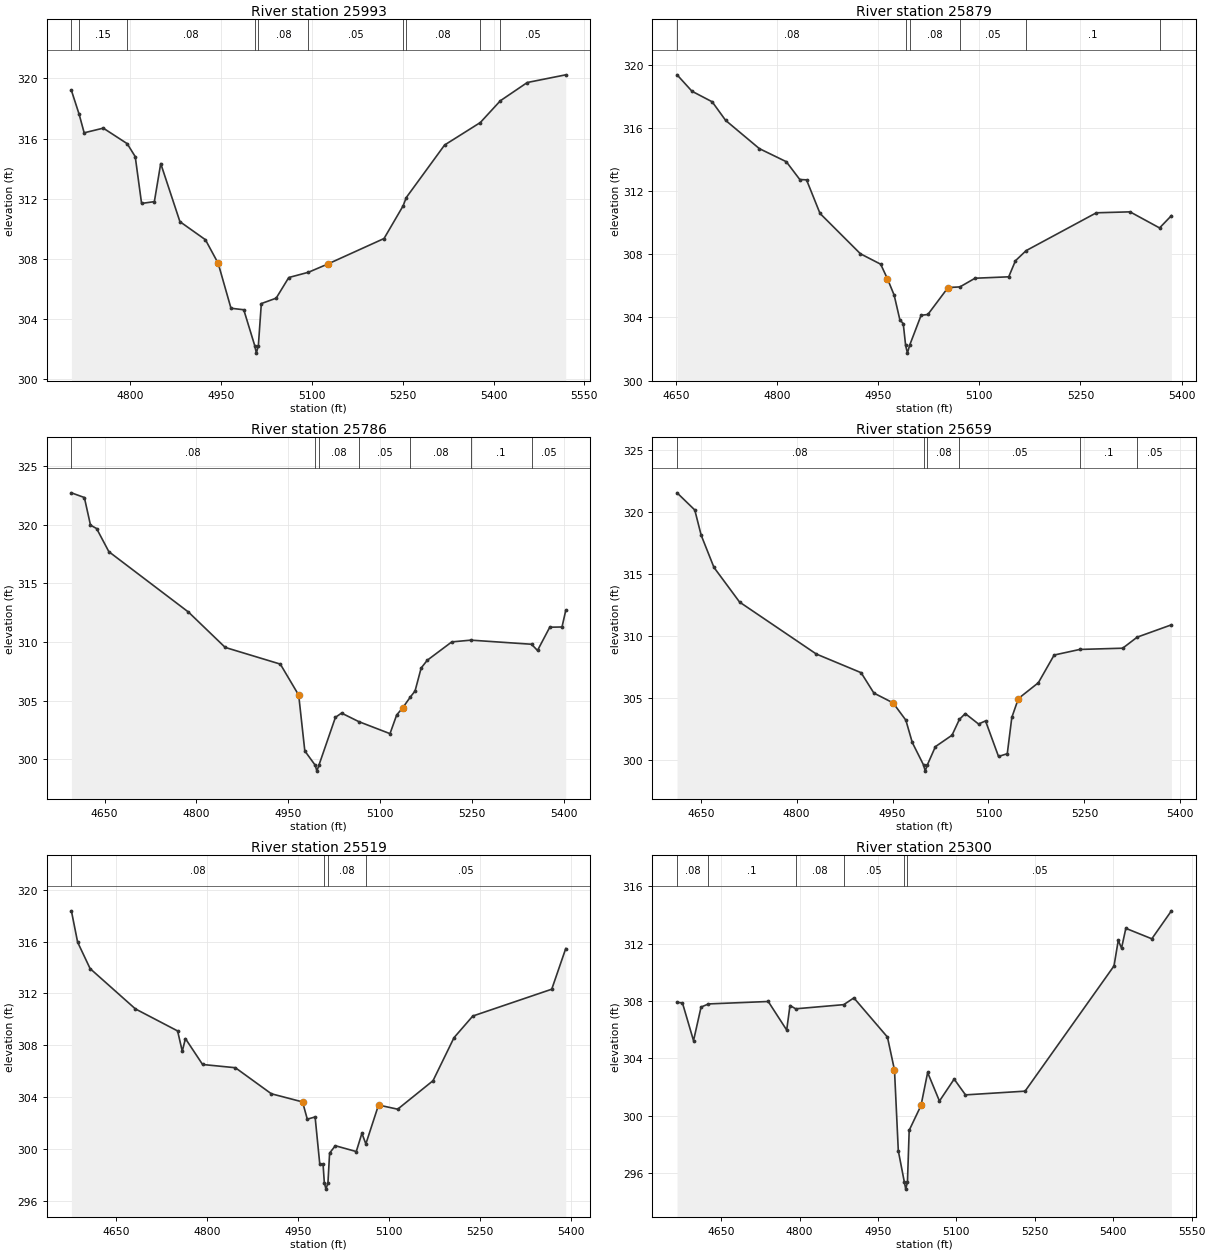
Type RM Length L Ch R = 1 ,25993   ,114,114,114
BEGIN DESCRIPTION:
UNT 0417 IN LACR 39.0
END DESCRIPTION:
XS GIS Cut Line= 3
      3666999.59     10677860.18      3666699.61     10677760.19
      3666299.61     10678060.19
#Sta/Elev= 30
    4703   319.2  4715.8  317.61  4724.1  316.38  4755.7  316.69  4795.1  315.66
  4808.4   314.8  4818.9  311.69    4840  311.81  4850.5  314.34  4882.2  310.48
  4924.3  309.28  4945.4  307.71  4966.5  304.73  4987.6  304.63  5005.7  302.25
  5008.4  301.75  5011.7  302.25  5016.6  305.04  5041.1   305.4  5061.9  306.77
  5094.4  307.12  5126.5  307.67  5219.2  309.36  5250.7  311.53  5255.9  312.08
  5319.2  315.57  5378.1  317.06  5411.3  318.51  5455.7  319.72  5519.2  320.23
#Mann= 10 ,-1 , 0
    4703     .08       0  4715.8     .15       0  4795.1     .08       0
  5005.7     .07       0  5011.7     .08       0  5094.4     .05       0
  5250.7      .1       0  5255.9     .08       0  5378.1      .1       0
  5411.3     .05       0
Bank Sta=4945.4,5126.5
XS Rating Curve= 0 ,0
Exp/Cntr=0.3,0.1

Type RM Length L Ch R = 1 ,25879   ,93,93,93
BEGIN DESCRIPTION:
Mapping XS 3e31ddd3
END DESCRIPTION:
XS GIS Cut Line= 2
      3667041.69     10677651.73      3666308.23     10677659.32
#Sta/Elev= 30
  4651.5  319.39  4673.6  318.35  4703.6  317.68  4723.6   316.5  4773.6  314.71
  4813.6  313.88  4833.6  312.75  4843.6  312.73  4863.6   310.6  4923.6  308.04
  4953.6  307.38  4963.6  306.46  4973.6  305.42  4982.1  303.85  4987.1  303.61
  4990.6  302.24  4993.3  301.74  4996.6  302.24  5013.6  304.14  5023.6  304.19
  5053.6   305.9  5071.2  305.94  5093.6  306.49  5143.6  306.58  5153.6   307.6
  5169.4  308.24  5273.6  310.64  5323.6   310.7  5367.4  309.68    5385  310.46
#Mann= 6 ,-1 , 0
  4651.5     .08       0  4990.6     .07       0  4996.6     .08       0
  5071.2     .05       0  5169.4      .1       0  5367.4     .05       0
Bank Sta=4963.6,5053.6
XS Rating Curve= 0 ,0
Exp/Cntr=0.3,0.1

Type RM Length L Ch R = 1 ,25786   ,127,127,127
BEGIN DESCRIPTION:
Mapping XS 977b961c
END DESCRIPTION:
XS GIS Cut Line= 2
      3667080.78     10677561.67      3666273.49     10677567.09
#Sta/Elev= 30
  4595.8   322.7    4617   322.3    4627  319.95    4637  319.66    4657  317.69
    4787  312.55    4847  309.54    4937  308.12    4967  305.48    4977  300.73
    4994  299.51  4996.7  299.01    5000  299.51    5027  303.59    5037  303.95
  5065.3  303.22  5116.1   302.2    5127  303.79    5137  304.41  5149.2  305.31
    5157  305.83    5167  307.79    5177  308.45    5217  310.01  5248.2  310.16
  5347.2  309.81    5357  309.28    5377  311.26    5397  311.28  5403.1  312.69
#Mann= 7 ,-1 , 0
  4595.8     .08       0    4994     .07       0    5000     .08       0
  5065.3     .05       0  5149.2     .08       0  5248.2      .1       0
  5347.2     .05       0
Bank Sta=4967,5137
XS Rating Curve= 0 ,0
Exp/Cntr=0.3,0.1

Type RM Length L Ch R = 1 ,25659   ,140,140,140
BEGIN DESCRIPTION:
Mapping XS 80ad564f
END DESCRIPTION:
XS GIS Cut Line= 3
      3667037.34     10677445.57      3666664.11     10677436.89
      3666279.31     10677545.28
#Sta/Elev= 30
    4613  321.52  4640.7  320.14  4650.7  318.11  4670.7  315.52  4710.8  312.73
  4830.8  308.55  4900.8  307.05  4920.8  305.41  4950.8  304.62  4970.8  303.23
  4980.8  301.44  4998.4  299.63  5001.1  299.13  5004.4  299.63    5017   301.1
    5043  302.02  5054.5  303.29  5063.7  303.76  5084.5  302.92  5095.4  303.17
  5115.7  300.31  5129.4  300.53  5136.5  303.45  5146.8  304.97    5178  306.24
  5202.7  308.47  5242.8  308.92  5309.9  309.02  5332.6  309.91  5386.1   310.9
#Mann= 6 ,-1 , 0
    4613     .08       0  4998.4     .07       0  5004.4     .08       0
  5054.5     .05       0  5242.8      .1       0  5332.6     .05       0
Bank Sta=4950.8,5146.8
XS Rating Curve= 0 ,0
Exp/Cntr=0.3,0.1

Type RM Length L Ch R = 1 ,25519   ,219,219,219
BEGIN DESCRIPTION:
UNT 0417 IN LACR 38.0
END DESCRIPTION:
XS GIS Cut Line= 3
      3666999.56     10677410.18      3666599.61     10677310.19
      3666249.59      10677510.2
#Sta/Elev= 30
  4576.2  318.37  4586.5  315.95  4607.1  313.91  4681.8   310.8  4751.4   309.1
  4759.1  307.53  4764.3  308.51  4792.6  306.51  4846.7  306.26    4906  304.25
  4957.5  303.62  4965.3  302.29  4978.2  302.46  4985.9  298.82  4991.3  298.82
  4993.4  297.39  4996.1  296.89  4999.4  297.39  5002.1  299.67  5011.5  300.24
  5046.1  299.79  5055.4   301.2  5061.9  300.38  5082.8  303.38  5114.4  303.06
  5172.7  305.26  5207.3  308.58  5238.3  310.25  5368.5  312.32  5391.6  315.46
#Mann= 4 ,-1 , 0
  4576.2     .08       0  4993.4     .07       0  4999.4     .08       0
  5061.9     .05       0
Bank Sta=4957.5,5082.8
XS Rating Curve= 0 ,0
Exp/Cntr=0.3,0.1

Type RM Length L Ch R = 1 ,25300   ,219,219,219
BEGIN DESCRIPTION:
Mapping XS b36d022b
END DESCRIPTION:
XS GIS Cut Line= 2
      3666797.72     10676884.53      3666051.78     10677465.67
#Sta/Elev= 30
  4565.7   307.9    4576  307.86  4597.2  305.23  4611.6  307.57  4625.8  307.79
  4740.1  307.96  4775.4  305.97  4781.7  307.68  4792.6  307.45  4884.5  307.74
  4903.9  308.21  4968.1  305.48  4981.6  303.18  4988.9  297.55  5000.4  295.38
  5003.1  294.88  5006.4  295.38  5009.7  298.98  5032.3  300.71    5045  303.01
  5067.6  301.02  5095.7  302.55  5117.4  301.45  5231.4  301.71  5401.5  310.44
  5409.6  312.22  5415.9  311.68  5424.1  313.06  5473.8  312.33  5511.3  314.28
#Mann= 6 ,-1 , 0
  4565.7     .08       0  4625.8      .1       0  4792.6     .08       0
  4884.5     .05       0  5000.4     .03       0  5006.4     .05       0
Bank Sta=4981.6,5032.3
XS Rating Curve= 0 ,0
Exp/Cntr=0.3,0.1

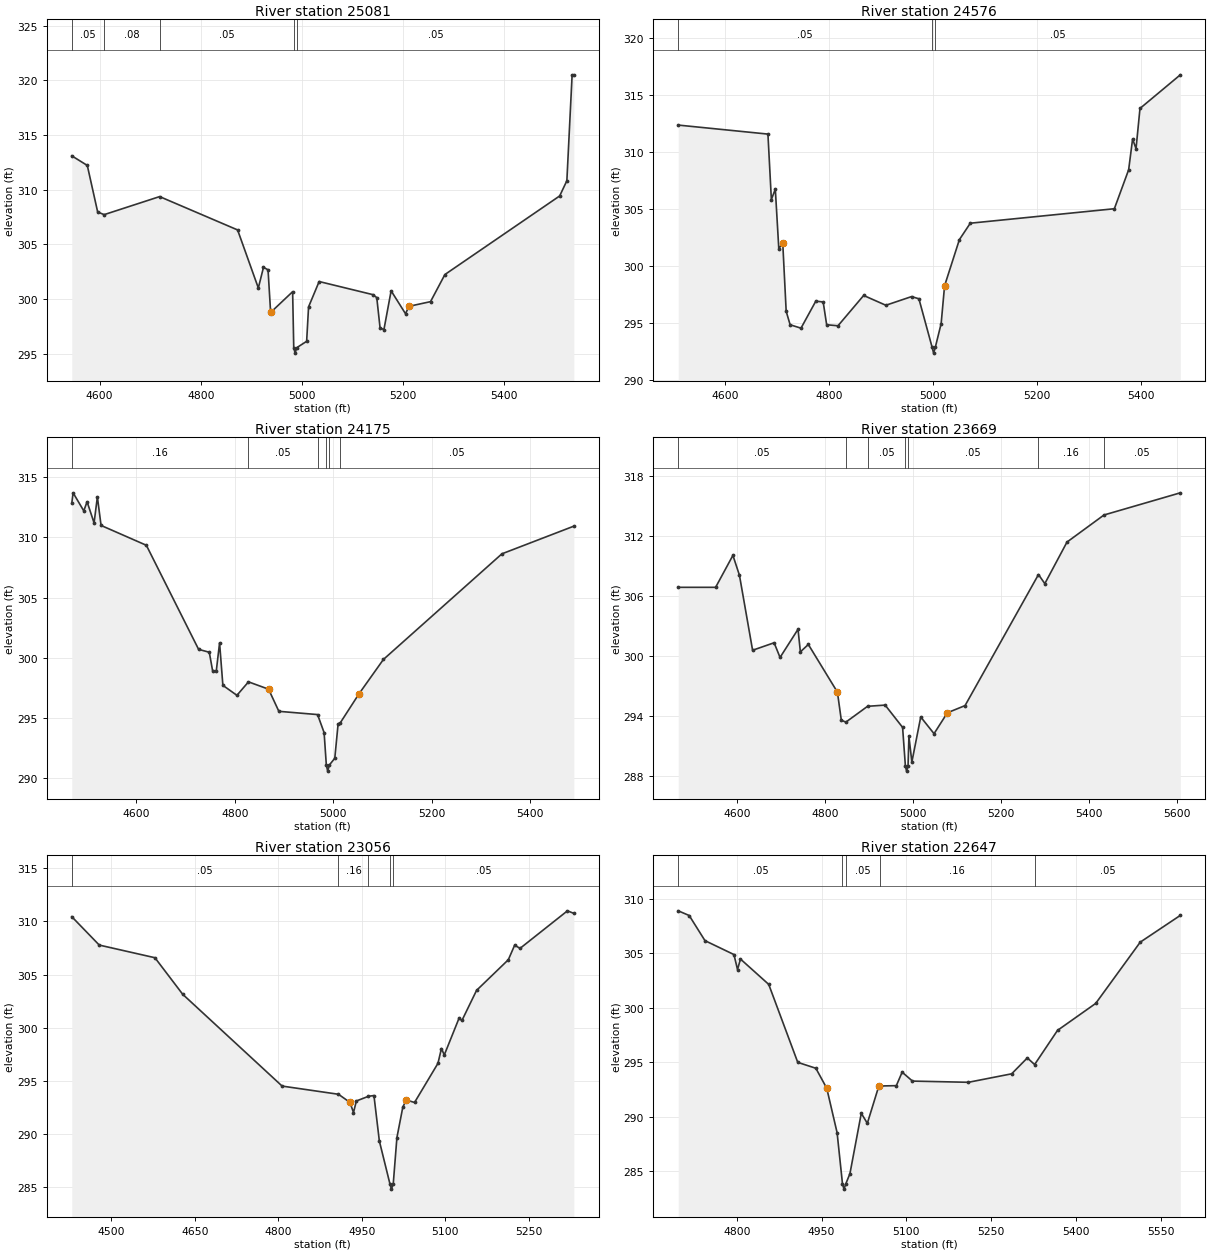
Type RM Length L Ch R = 1 ,25081   ,505,505,505
BEGIN DESCRIPTION:
UNT 0417 IN LACR 37.0
END DESCRIPTION:
XS GIS Cut Line= 3
      3666399.61     10676560.21      3666299.61     10677010.19
      3665899.58     10677360.21
#Sta/Elev= 30
  4545.1   313.1  4575.8  312.22  4596.3  307.96  4609.2  307.72  4718.8  309.37
  4872.9  306.32  4913.9  301.01  4924.1   302.9  4933.1  302.67  4938.2  298.77
  4981.7  300.67  4983.9  295.55  4986.6  295.05  4989.9  295.55  5009.4  296.13
  5013.2  299.28  5034.1   301.6  5140.4   300.4    5148  300.13  5154.6  297.34
  5162.2  297.21  5176.4  300.75  5204.9  298.65  5211.5  299.33  5254.3  299.76
  5282.7  302.24  5509.6  309.43  5523.8  310.82  5534.2  320.51  5537.6  320.51
#Mann= 5 ,-1 , 0
  4545.1     .05       0  4609.2     .08       0  4718.8     .05       0
  4983.9     .04       0  4989.9     .05       0
Bank Sta=4938.2,5211.5
XS Rating Curve= 0 ,0
Exp/Cntr=0.3,0.1

Type RM Length L Ch R = 1 ,24576   ,401,401,401
BEGIN DESCRIPTION:
UNT 0417 IN LACR 36.0
END DESCRIPTION:
XS GIS Cut Line= 2
      3666238.73     10676385.98      3665605.01     10677115.19
#Sta/Elev= 30
  4509.8   312.4  4682.4  311.61    4689  305.87  4696.6  306.78  4703.3  301.56
  4710.9  302.06  4717.5  296.06  4725.1  294.88    4746  294.58  4774.5  296.95
  4788.7  296.88  4795.4  294.88  4817.2  294.79  4866.6  297.45  4909.3  296.59
  4958.7  297.35  4972.9  297.16  4998.4  292.89  5001.2  292.39  5004.4  292.89
  5015.7  294.98  5022.3   298.3  5050.8  302.35  5071.8  303.79    5349  305.06
  5376.5  308.48  5384.1  311.18  5390.7  310.33  5398.3  313.86  5475.9  316.81
#Mann= 3 ,-1 , 0
  4509.8     .05       0  4998.4     .03       0  5004.4     .05       0
Bank Sta=4710.9,5022.3
XS Rating Curve= 0 ,0
Exp/Cntr=0.3,0.1

Type RM Length L Ch R = 1 ,24175   ,506,506,506
BEGIN DESCRIPTION:
UNT 0417 IN LACR 35.0
END DESCRIPTION:
XS GIS Cut Line= 2
      3666078.07     10676164.69      3665319.06     10676845.63
#Sta/Elev= 30
  4468.8  312.83  4471.5  313.71  4493.2  312.21  4499.9  312.97  4514.1  311.21
  4520.8  313.37  4528.3     311  4620.3  309.35  4726.4   300.7  4748.1  300.46
  4754.8  298.93  4762.3   298.9    4769  301.24  4775.7  297.71  4804.2  296.88
  4827.7     298  4868.5  297.39  4889.4  295.55    4968  295.28  4981.3  293.78
  4985.8  291.08  4988.6  290.58  4991.8  291.08    5003  291.65  5009.7   294.5
  5014.2   294.6  5052.4  297.02  5101.7  299.86  5342.4  308.64  5488.5  310.94
#Mann= 6 ,-1 , 0
  4468.8     .16       0  4827.7     .05       0    4968     .16       0
  4985.8     .07       0  4991.8     .16       0  5014.2     .05       0
Bank Sta=4868.5,5052.4
XS Rating Curve= 0 ,0
Exp/Cntr=0.3,0.1

Type RM Length L Ch R = 1 ,23669   ,613,613,613
BEGIN DESCRIPTION:
UNT 0417 IN LACR 34.0
END DESCRIPTION:
XS GIS Cut Line= 3
      3665995.62     10675965.01      3665505.19     10676155.98
      3664893.92     10676238.35
#Sta/Elev= 30
  4465.3  306.86  4550.4  306.86  4589.8  310.06  4604.7  308.06  4634.6  300.56
  4683.6  301.31  4697.1  299.84    4738  302.66  4743.4   300.4  4761.5  301.14
  4827.7  296.37  4836.6  293.55  4847.1  293.37  4896.4  294.95  4936.4  295.07
  4976.1  292.84  4982.5  288.96  4985.2  288.46  4988.5  288.96  4990.5  291.96
  4997.2  289.37  5017.4  293.88  5047.7  292.21    5078   294.3  5118.3  295.02
  5285.5  308.14  5299.9  307.23  5350.4  311.39  5434.6   314.1  5608.4  316.32
#Mann= 7 ,-1 , 0
  4465.3     .05       0  4847.1     .16       0  4896.4     .05       0
  4982.5     .03       0  4988.5     .05       0  5285.5     .16       0
  5434.6     .05       0
Bank Sta=4827.7,5078
XS Rating Curve= 0 ,0
Exp/Cntr=0.3,0.1

Type RM Length L Ch R = 1 ,23056   ,409,409,409
BEGIN DESCRIPTION:
UNT 0417 IN LACR 33.0
END DESCRIPTION:
XS GIS Cut Line= 3
      3665868.95     10675708.31      3665378.45     10675730.02
      3664987.86     10675860.22
#Sta/Elev= 30
  4428.6  310.44    4478  307.77  4578.1  306.58  4628.1  303.14  4806.8  294.51
  4908.1  293.74  4928.9  292.97  4935.1  292.02  4940.3  293.11  4962.1  293.55
  4971.9  293.62  4981.6  289.35  5000.6  285.32  5003.3  284.82  5006.6  285.32
  5013.2  289.67  5023.8  292.53  5029.9   293.2  5044.9  292.97    5087  296.65
  5093.2  298.04  5098.4  297.44  5124.8  300.88  5130.1  300.68  5156.4  303.51
  5213.5  306.39  5224.9  307.76  5234.6  307.46  5319.8  310.99  5331.3  310.75
#Mann= 5 ,-1 , 0
  4428.6     .05       0  4908.1     .16       0  4962.1     .05       0
  5000.6     .03       0  5006.6     .05       0
Bank Sta=4928.9,5029.9
XS Rating Curve= 0 ,0
Exp/Cntr=0.3,0.1

Type RM Length L Ch R = 1 ,22647   ,305,305,305
BEGIN DESCRIPTION:
UNT 0417 IN LACR 32.0
END DESCRIPTION:
XS GIS Cut Line= 3
      3665765.65     10675331.31      3665314.22     10675435.49
      3664936.64     10675630.79
#Sta/Elev= 30
  4696.3  308.91  4715.7  308.48  4743.6  306.17  4794.9  304.89  4801.2  303.51
  4806.4  304.48  4856.4  302.15  4907.8  294.98  4939.8  294.44  4959.1   292.6
  4977.4  288.52  4986.9  283.83  4989.6  283.33  4992.9  283.83  5000.1  284.75
  5020.2   290.3  5030.9  289.38  5051.4  292.83  5052.6  292.81  5082.2  292.84
  5092.5  294.08  5110.8  293.26  5209.8  293.15  5286.3  293.93    5314  295.39
  5326.9  294.78  5367.4  297.92    5435   300.4  5513.8  306.03  5584.7  308.49
#Mann= 5 ,-1 , 0
  4696.3     .05       0  4986.9     .03       0  4992.9     .05       0
  5052.6     .16       0  5326.9     .05       0
Bank Sta=4959.1,5051.4
XS Rating Curve= 0 ,0
Exp/Cntr=0.3,0.1