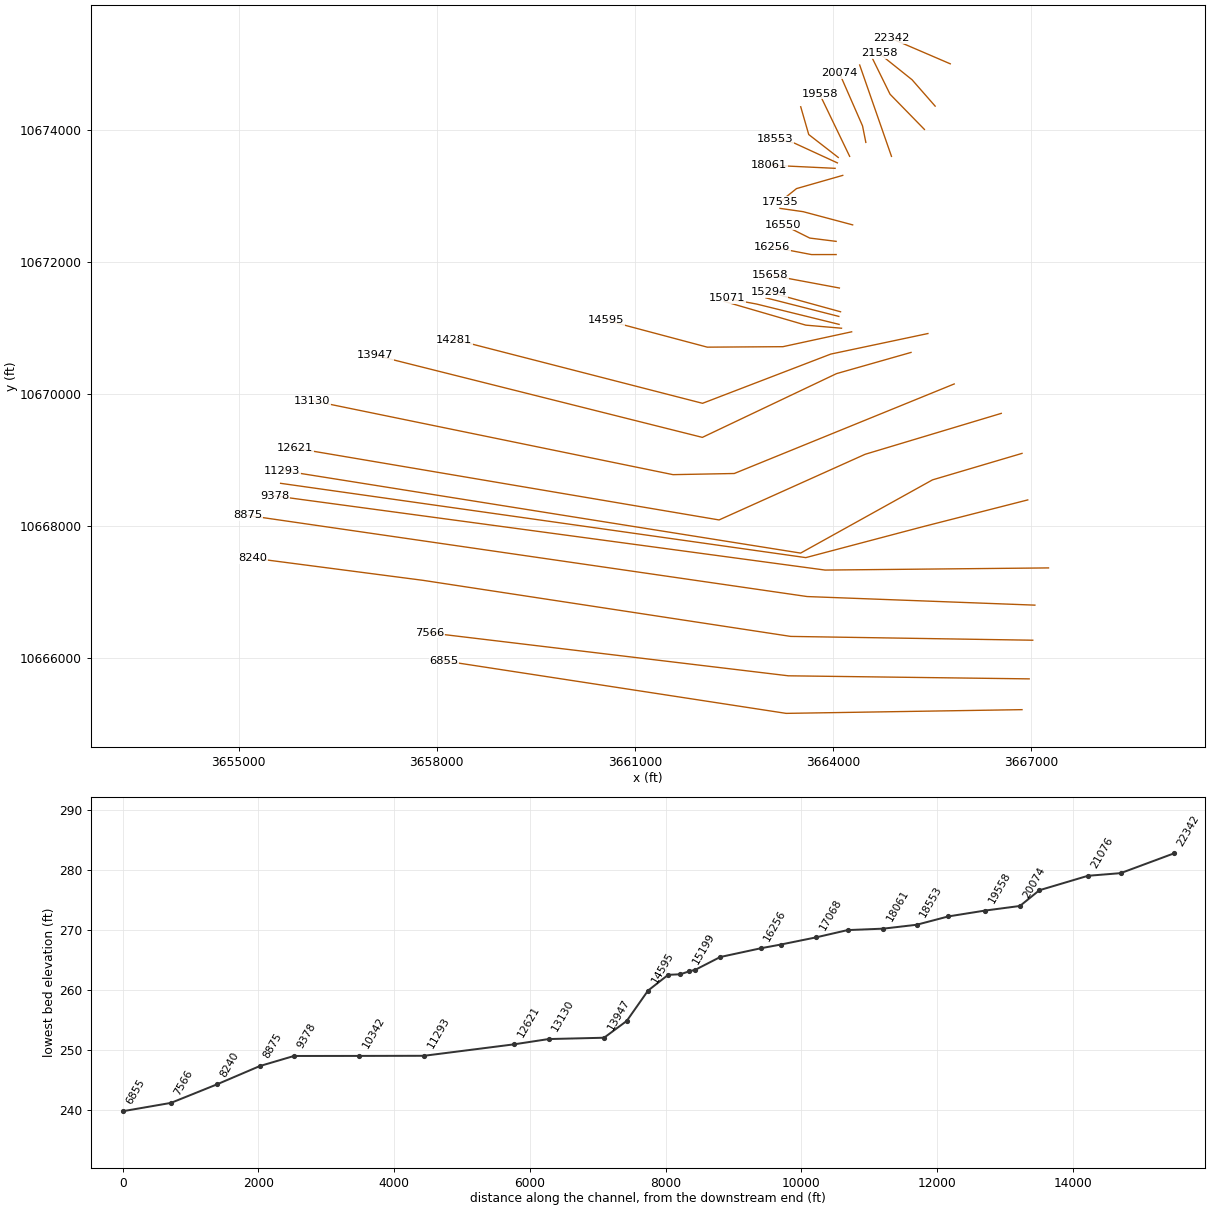
HEC-RAS study UNT 0417 IN LACR.prj: UNT 0417 IN LACR Base Level Engineering

--- UNT 0417 IN LACR.g01 (geometry) --- (continued)

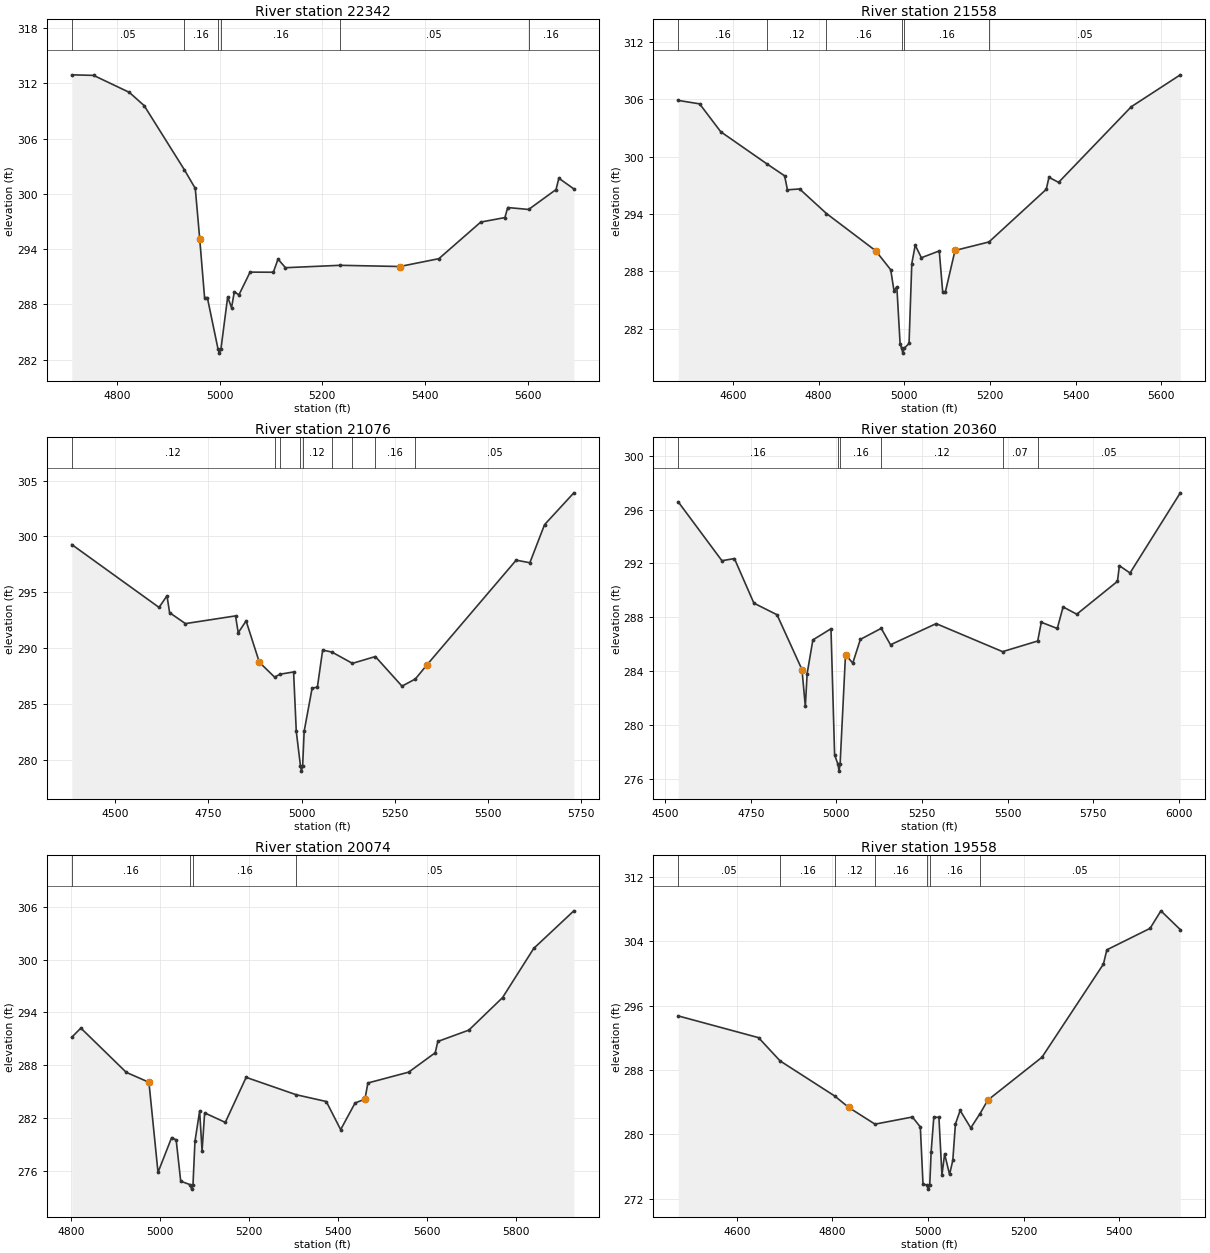
Type RM Length L Ch R = 1 ,22342   ,784,784,784
BEGIN DESCRIPTION:
UNT 0417 IN LACR 31.0
END DESCRIPTION:
XS GIS Cut Line= 2
      3665778.65     10675001.46      3664880.17     10675387.76
#Sta/Elev= 30
  4712.1  312.92  4754.6  312.86  4824.1  311.02  4853.1  309.58  4931.3  302.63
  4952.7  300.59  4961.4  295.07  4970.8  288.74  4976.2  288.74  4996.8  283.22
  4999.5  282.72  5002.8  283.22  5015.8  288.82  5023.3  287.65  5028.8  289.39
  5037.6  289.03  5059.4  291.51  5104.8   291.5  5113.8  292.92  5128.4  291.99
  5234.6  292.25  5351.2  292.12  5427.2  292.97  5508.7  296.94  5555.8  297.43
  5561.3  298.52    5602  298.31  5655.4  300.47  5660.9   301.7  5690.1  300.54
#Mann= 6 ,-1 , 0
  4712.1     .05       0  4931.3     .16       0  4996.8     .07       0
  5002.8     .16       0  5234.6     .05       0    5602     .16       0
Bank Sta=4961.4,5351.2
XS Rating Curve= 0 ,0
Exp/Cntr=0.3,0.1

Type RM Length L Ch R = 1 ,21558   ,482,482,482
BEGIN DESCRIPTION:
UNT 0417 IN LACR 30.0
END DESCRIPTION:
XS GIS Cut Line= 3
      3665549.62     10674360.17      3665199.61     10674760.19
      3664699.64     10675160.16
#Sta/Elev= 30
  4472.4  305.89  4522.3  305.53  4571.6  302.61  4680.5  299.21  4720.6     298
  4727.3  296.53  4755.7  296.62  4818.3  294.05  4933.2  290.15  4968.3  288.16
  4975.9  285.97  4982.6  286.37  4990.2  280.43  4993.8  279.93  4996.6  279.43
  4999.8  279.93  5011.1  280.45  5017.5   288.8  5025.5  290.73  5039.9  289.42
  5081.6  290.13  5089.6  285.85    5096  285.86  5118.4  290.18  5197.6  291.07
  5331.3  296.58  5337.7  297.84  5360.1  297.31  5529.8  305.23  5644.2  308.57
#Mann= 6 ,-1 , 0
  4472.4     .16       0  4680.5     .12       0  4818.3     .16       0
  4993.8     .07       0  4999.8     .16       0  5197.6     .05       0
Bank Sta=4933.2,5118.4
XS Rating Curve= 0 ,0
Exp/Cntr=0.3,0.1

Type RM Length L Ch R = 1 ,21076   ,716,716,716
BEGIN DESCRIPTION:
UNT 0417 IN LACR 29.0
END DESCRIPTION:
XS GIS Cut Line= 3
      3665387.14     10674006.92       3664866.3     10674540.78
      3664601.56     10675078.94
#Sta/Elev= 30
  4384.2  299.28  4618.1  293.65  4639.4  294.69  4646.4  293.18  4688.8   292.2
  4823.1  292.89  4830.3  291.38  4851.4  292.44  4886.9  288.74  4927.7  287.41
  4942.7  287.67  4978.7  287.87  4985.9  282.55    4997  279.49  4999.8  278.99
    5003  279.49    5007  282.55  5028.3  286.41  5042.5  286.52  5056.6  289.83
  5081.5  289.65  5136.4  288.64  5197.8  289.25  5269.2   286.6    5305  287.24
  5336.7  288.53  5575.2  297.88  5611.9  297.65  5651.3  301.06  5729.8  303.91
#Mann= 9 ,-1 , 0
  4384.2     .12       0  4927.7     .16       0  4942.7     .12       0
    4997     .07       0    5003     .12       0  5081.5     .16       0
  5136.4     .05       0  5197.8     .16       0    5305     .05       0
Bank Sta=4886.9,5336.7
XS Rating Curve= 0 ,0
Exp/Cntr=0.3,0.1

Type RM Length L Ch R = 1 ,20360   ,286,286,286
BEGIN DESCRIPTION:
UNT 0417 IN LACR 28.0
END DESCRIPTION:
XS GIS Cut Line= 2
      3664888.01     10673598.92      3664406.23      10674983.5
#Sta/Elev= 30
  4538.4  296.57    4666   292.2  4702.4  292.36  4759.3  289.05  4826.8  288.19
  4899.7  284.12  4909.5  281.38  4914.8  283.82  4931.5  286.32  4984.4  287.15
    4995  277.78    5005  277.08  5007.8  276.58    5011  277.08  5026.8  285.23
    5048   284.6  5070.2  286.36  5131.1  287.18  5158.2  285.96  5291.5  287.53
  5485.5  285.45    5588  286.24  5598.5  287.63  5645.2  287.17  5662.1  288.77
  5702.1  288.23  5820.9  290.67  5826.5  291.83  5857.6  291.29  6004.4  297.24
#Mann= 6 ,-1 , 0
  4538.4     .16       0    5005     .07       0    5011     .16       0
  5131.1     .12       0  5485.5     .07       0    5588     .05       0
Bank Sta=4899.7,5026.8
XS Rating Curve= 0 ,0
Exp/Cntr=0.3,0.1

Type RM Length L Ch R = 1 ,20074   ,516,516,516
BEGIN DESCRIPTION:
UNT 0417 IN LACR 27.0
END DESCRIPTION:
XS GIS Cut Line= 3
      3664499.61     10673810.19      3664449.61     10674060.19
      3664099.59     10674860.23
#Sta/Elev= 30
  4801.5  291.19  4821.9  292.23  4923.9  287.21  4974.9  286.08  4995.3  275.86
  5025.9  279.81  5036.1  279.54  5046.3  274.86  5067.9  274.46  5070.6  273.96
  5073.9  274.46  5078.3  279.37  5088.8  282.81  5094.3   278.3  5100.1  282.61
  5146.5  281.53  5193.3  286.64  5305.7  284.67  5373.4   283.9  5405.7  280.71
  5438.1  283.73  5460.3  284.17  5466.9     286  5558.5  287.23  5618.2  289.43
    5624  290.71  5693.8     292  5769.4  295.68  5839.6  301.27  5929.7  305.53
#Mann= 4 ,-1 , 0
  4801.5     .16       0  5067.9     .07       0  5073.9     .16       0
  5305.7     .05       0
Bank Sta=4974.9,5460.3
XS Rating Curve= 0 ,0
Exp/Cntr=0.3,0.1

Type RM Length L Ch R = 1 ,19558   ,538,538,538
BEGIN DESCRIPTION:
UNT 0417 IN LACR 26.0
END DESCRIPTION:
XS GIS Cut Line= 2
      3664254.33     10673598.92      3663798.61     10674545.09
#Sta/Elev= 30
  4477.4  294.73  4645.3  292.03  4690.6  289.13  4804.7  284.77    4834  283.35
    4889  281.27  4967.2  282.16  4983.8  280.92  4989.4  273.81  4997.5  273.69
  5000.2  273.19  5003.5  273.69  5006.4  277.82    5012  282.14  5022.7  282.11
    5029  274.93  5034.6  277.57  5044.9  275.01  5051.7  276.76  5057.2  281.29
  5067.1  282.97  5089.3   280.8  5108.5  282.57  5125.1  284.27  5238.2  289.59
  5366.8  301.18  5373.9  302.95  5464.4  305.62    5487   307.8  5527.6  305.46
#Mann= 7 ,-1 , 0
  4477.4     .05       0  4690.6     .16       0  4804.7     .12       0
    4889     .16       0  4997.5     .07       0  5003.5     .16       0
  5108.5     .05       0
Bank Sta=4834,5125.1
XS Rating Curve= 0 ,0
Exp/Cntr=0.3,0.1

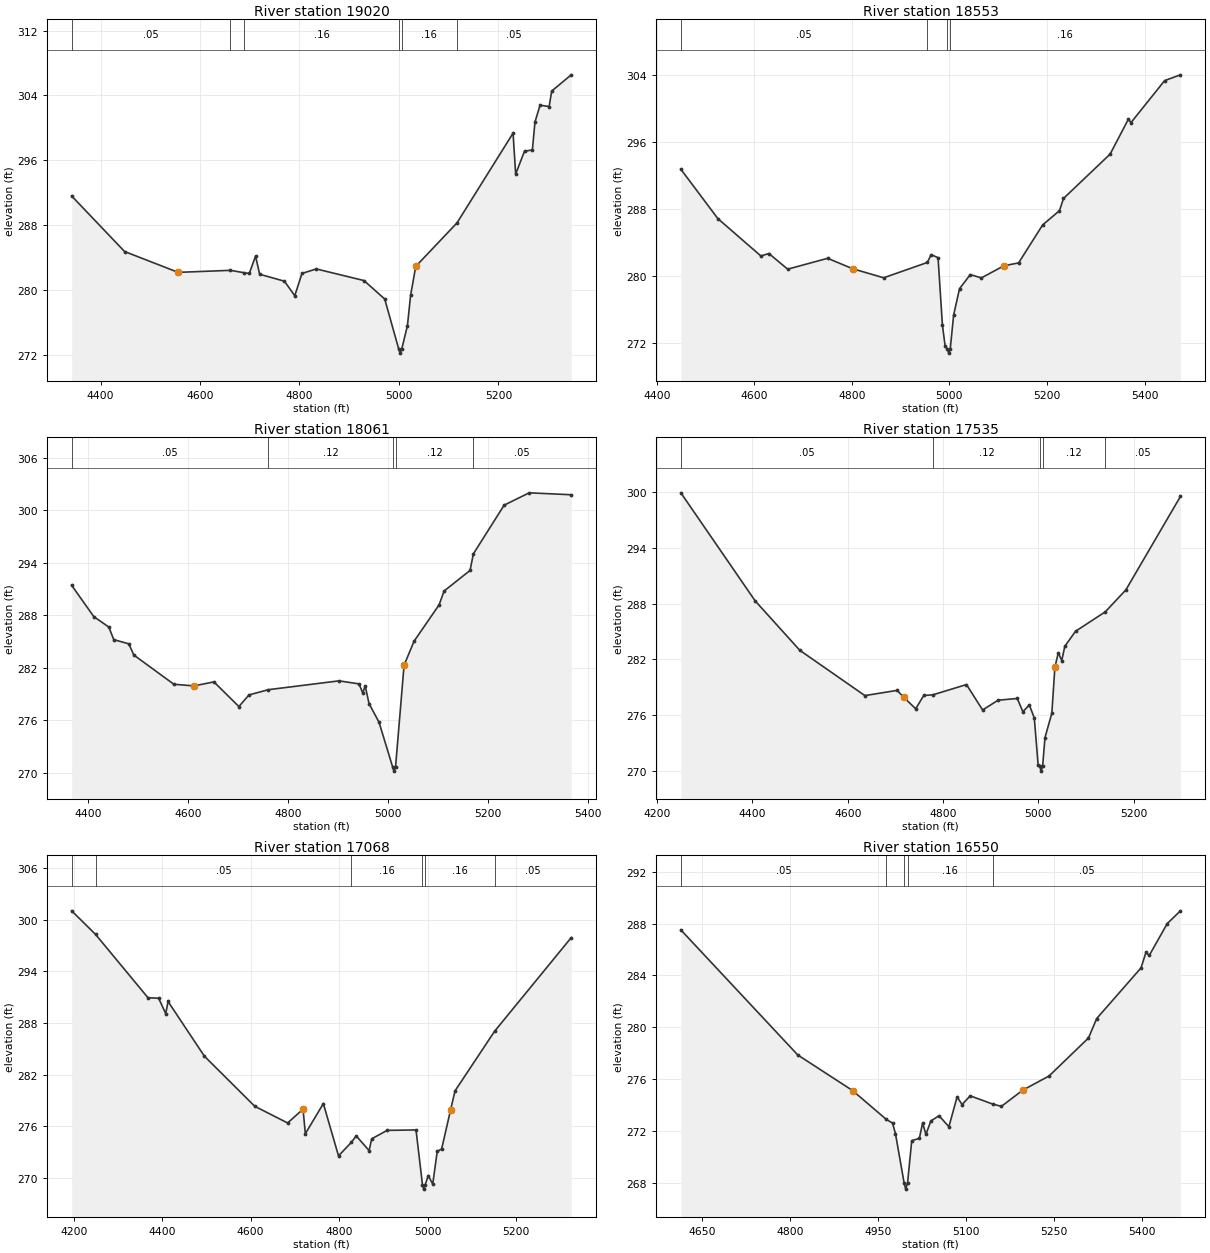
Type RM Length L Ch R = 1 ,19020   ,467,467,467
BEGIN DESCRIPTION:
UNT 0417 IN LACR 25.0
END DESCRIPTION:
XS GIS Cut Line= 3
      3664081.56     10673582.21      3663634.53     10673929.41
      3663513.01      10674350.4
#Sta/Elev= 30
    4342   291.6  4448.4  284.75  4556.1  282.18  4661.3  282.43    4689  282.13
    4699  282.04  4711.7  284.18  4719.9  281.95  4769.7  281.09  4790.5   279.3
    4805  282.05  4833.9   282.6  4929.6  281.17  4971.3  278.89  4999.5  272.72
  5002.3  272.22  5005.5  272.72    5017  275.62  5023.3  279.33  5033.7  282.92
  5116.6  288.28  5229.3  299.35  5234.5   294.3  5252.3  297.13  5268.1  297.27
  5273.3  300.71  5283.5  302.79  5301.8  302.63    5307  304.54  5346.2  306.54
#Mann= 6 ,-1 , 0
    4342     .05       0  4661.3     .12       0    4689     .16       0
  4999.5     .07       0  5005.5     .16       0  5116.6     .05       0
Bank Sta=4556.1,5033.7
XS Rating Curve= 0 ,0
Exp/Cntr=0.3,0.1

Type RM Length L Ch R = 1 ,18553   ,492,492,492
BEGIN DESCRIPTION:
UNT 0417 IN LACR 24.0
END DESCRIPTION:
XS GIS Cut Line= 3
      3664068.56     10673499.73      3663417.52     10673799.21
      3663118.08     10673868.64
#Sta/Elev= 30
  4449.5   292.8  4525.4   286.9  4613.5  282.44    4630  282.73  4668.5  280.86
  4750.4  282.16  4801.8  280.91  4865.2  279.83  4954.7  281.66  4962.6   282.6
  4976.7  282.23  4985.6   274.2  4991.1  271.73  4995.7  271.33  4998.5  270.83
  5001.7  271.33  5008.6  275.38  5020.7  278.53  5042.7  280.21  5065.5  279.82
  5111.5  281.26  5141.8  281.61  5191.1  286.15  5225.6  287.85  5233.8  289.31
  5329.4  294.61  5366.9  298.79    5372  298.36  5441.1  303.39  5473.5  304.08
#Mann= 4 ,-1 , 0
  4449.5     .05       0  4954.7     .16       0  4995.7     .07       0
  5001.7     .16       0
Bank Sta=4801.8,5111.5
XS Rating Curve= 0 ,0
Exp/Cntr=0.3,0.1

Type RM Length L Ch R = 1 ,18061   ,526,526,526
BEGIN DESCRIPTION:
UNT 0417 IN LACR 23.0
END DESCRIPTION:
XS GIS Cut Line= 2
      3664033.86     10673417.26       3663035.6       10673465.
#Sta/Elev= 30
  4367.2  291.42  4411.5  287.84  4441.5  286.65  4451.5  285.21  4481.6  284.73
  4491.6  283.45  4571.7  280.11  4611.7  279.92  4651.8  280.38  4701.8  277.56
  4721.9  278.89  4760.9  279.49  4902.1   280.5  4942.1  280.15  4949.5  279.12
  4954.5  279.91  4962.1   277.9  4982.1  275.77  5009.2  270.68  5011.9  270.18
  5015.2  270.68  5032.2  282.28  5052.2  285.03  5102.3  289.19  5112.3  290.77
  5164.2  293.12  5170.8  295.01  5232.4  300.58  5282.5  301.99  5366.6  301.77
#Mann= 5 ,-1 , 0
  4367.2     .05       0  4760.9     .12       0  5009.2     .07       0
  5015.2     .12       0  5170.8     .05       0
Bank Sta=4611.7,5032.2
XS Rating Curve= 0 ,0
Exp/Cntr=0.3,0.1

Type RM Length L Ch R = 1 ,17535   ,467,467,467
BEGIN DESCRIPTION:
UNT 0417 IN LACR 22.0
END DESCRIPTION:
XS GIS Cut Line= 3
      3664149.61     10673310.19      3663449.61     10673110.19
      3663199.58     10672910.17
#Sta/Elev= 30
  4249.9  299.93  4405.9  288.28  4499.5  282.96    4636  278.08  4703.6  278.64
  4717.9  277.88  4742.6  276.66  4759.5  278.09  4779.2  278.17  4849.2  279.27
    4883  276.53  4915.5  277.58  4955.8  277.77  4967.5  276.34  4981.1  277.07
  4991.5  275.66  4999.5  270.61  5002.9  270.44  5005.7  269.94  5008.9  270.44
  5013.9  273.55  5028.3  276.19  5034.7  281.15  5041.9  282.69  5049.1  281.86
  5055.5  283.39    5078  285.01  5140.5  287.11  5183.6  289.47  5298.1  299.54
#Mann= 5 ,-1 , 0
  4249.9     .05       0  4779.2     .12       0  5002.9     .07       0
  5008.9     .12       0  5140.5     .05       0
Bank Sta=4717.9,5034.7
XS Rating Curve= 0 ,0
Exp/Cntr=0.3,0.1

Type RM Length L Ch R = 1 ,17068   ,518,518,518
BEGIN DESCRIPTION:
UNT 0417 IN LACR 21.0
END DESCRIPTION:
XS GIS Cut Line= 3
      3664299.63     10672560.18      3663549.61     10672760.19
      3663199.59     10672810.19
#Sta/Elev= 30
  4195.2  301.02  4249.2  298.29  4367.9  290.93  4391.9  290.88    4408  289.08
  4413.2   290.5  4495.4  284.15  4609.2  278.34  4683.6   276.4  4718.5     278
  4723.7  275.15  4764.4  278.65  4798.7  272.58  4827.6  274.14  4838.8   274.9
  4867.9  273.19  4873.8  274.56  4908.7  275.54    4974  275.59  4988.6  269.22
  4991.4  268.72  4994.6  269.22  5001.7  270.28  5011.8  269.31  5021.9  273.09
    5032  273.39  5052.2  277.93  5062.3  280.13  5151.8  287.05    5325  297.91
#Mann= 6 ,-1 , 0
  4195.2      .1       0  4249.2     .05       0  4827.6     .16       0
  4988.6     .07       0  4994.6     .16       0  5151.8     .05       0
Bank Sta=4718.5,5052.2
XS Rating Curve= 0 ,0
Exp/Cntr=0.3,0.1

Type RM Length L Ch R = 1 ,16550   ,294,294,294
BEGIN DESCRIPTION:
UNT 0417 IN LACR 20.0
END DESCRIPTION:
XS GIS Cut Line= 3
      3664049.59     10672310.19      3663649.61     10672360.19
      3663249.62     10672560.18
#Sta/Elev= 30
  4614.5  287.51  4813.5  277.87  4906.7  275.13  4964.3   272.9  4974.8  272.62
  4979.8   271.8  4994.4  268.03  4997.2  267.53  5000.4  268.03  5007.5  271.27
  5020.4  271.44    5026  272.63  5031.6  271.75    5040  272.78  5053.9  273.19
  5070.7  272.34  5084.7  274.64  5093.1  274.05    5107  274.72    5145  274.09
  5160.1  273.91  5196.5  275.16  5241.2  276.25  5308.3  279.18  5322.3  280.68
  5397.7  284.58  5406.1  285.77  5411.7  285.54  5442.4     288  5464.8  288.98
#Mann= 5 ,-1 , 0
  4614.5     .05       0  4964.3     .16       0  4994.4     .07       0
  5000.4     .16       0    5145     .05       0
Bank Sta=4906.7,5196.5
XS Rating Curve= 0 ,0
Exp/Cntr=0.3,0.1

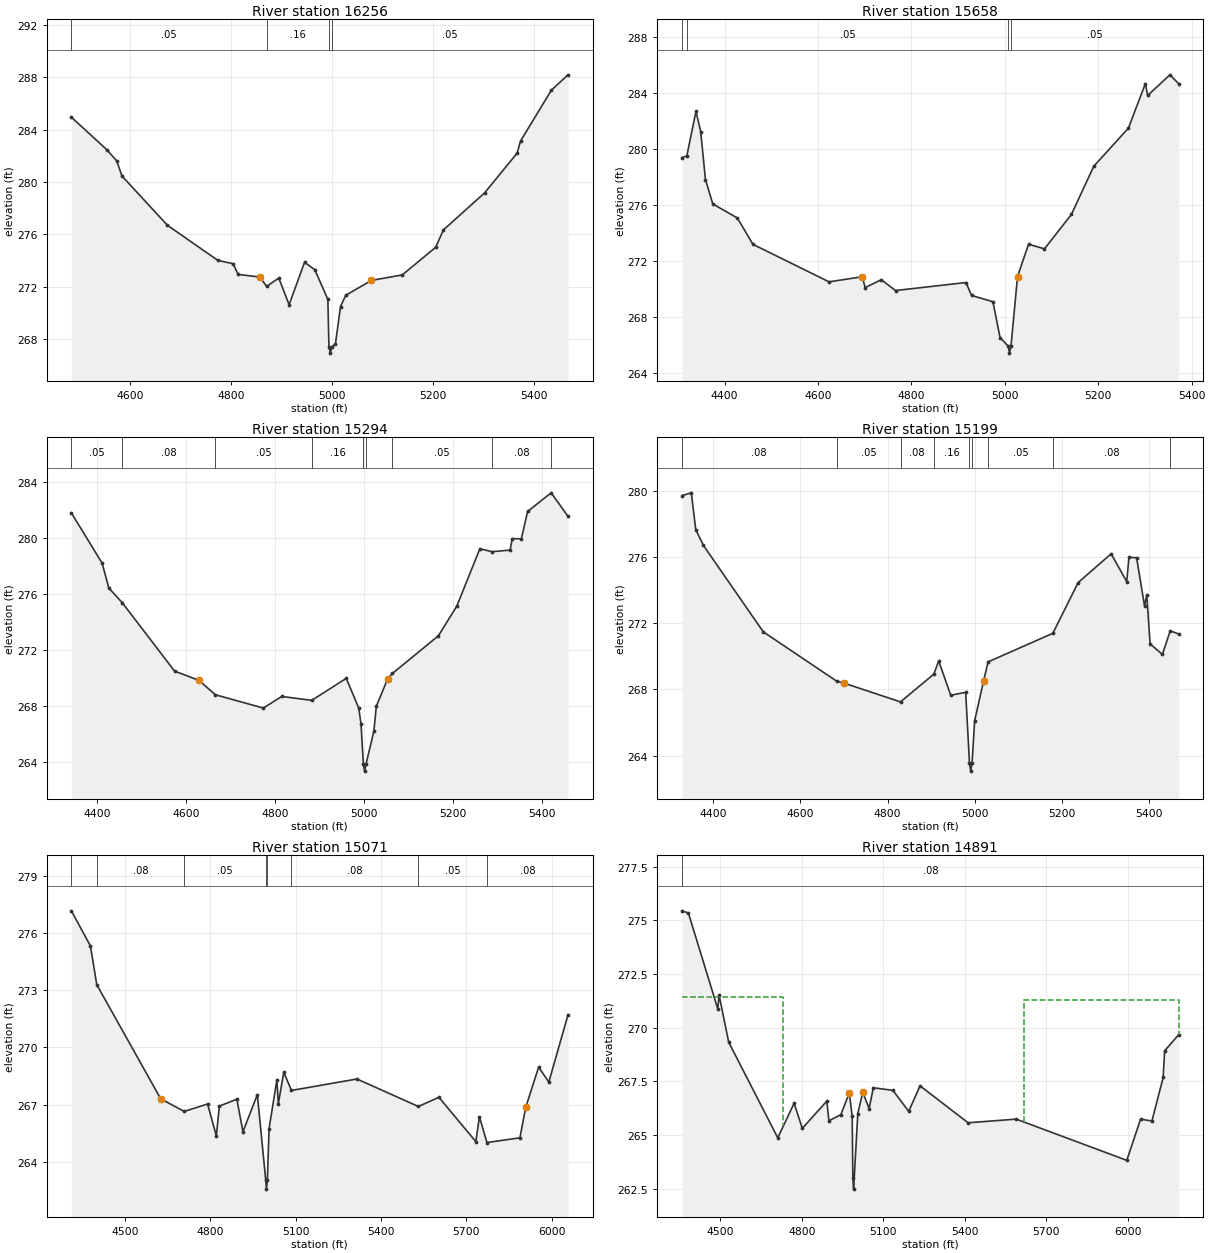
Type RM Length L Ch R = 1 ,16256   ,598,598,598
BEGIN DESCRIPTION:
UNT 0417 IN LACR 19.0
END DESCRIPTION:
XS GIS Cut Line= 3
      3664049.57     10672110.19      3663676.34     10672109.85
      3663077.33     10672224.44
#Sta/Elev= 30
  4483.5  284.95  4553.5  282.47  4573.5   281.6  4583.5  280.46  4673.5  276.69
  4773.5     274  4803.5  273.75  4813.5  272.93  4856.7  272.73    4870  272.01
  4894.1  272.65  4914.5  270.61    4945  273.85  4965.4  273.29  4991.2  271.02
  4993.3  267.41  4996.1  266.91  4999.3  267.41  5006.1  267.59  5016.3  270.47
  5026.5  271.33  5077.4  272.47  5138.5  272.89  5204.6     275  5219.9  276.33
  5301.4  279.16  5365.8   282.2  5372.6  283.13  5433.7  287.02  5466.6  288.19
#Mann= 4 ,-1 , 0
  4483.5     .05       0    4870     .16       0  4993.3     .03       0
  4999.3     .05       0
Bank Sta=4856.7,5077.4
XS Rating Curve= 0 ,0
Exp/Cntr=0.3,0.1

Type RM Length L Ch R = 1 ,15658   ,364,364,364
BEGIN DESCRIPTION:
UNT 0417 IN LACR 18.0
END DESCRIPTION:
XS GIS Cut Line= 2
      3664098.95     10671603.02      3663053.82     10671798.17
#Sta/Elev= 30
    4309  279.38  4319.3   279.5  4338.9  282.67    4349  281.24  4359.2  277.82
  4374.9  276.08  4427.5  275.08  4460.9   273.2  4623.7  270.53  4694.9  270.89
  4701.1  270.12  4735.6  270.68  4766.1  269.91  4916.9  270.48  4928.9  269.56
  4974.6  269.11  4989.9  266.56  5007.3  265.95    5010  265.45  5013.3  265.95
  5027.3  270.91  5050.9  273.21    5085  272.88  5142.8  275.34  5190.4  278.76
  5264.6  281.48  5300.8  284.64  5305.9  283.81  5353.5  285.28  5372.2  284.65
#Mann= 4 ,-1 , 0
    4309     .16       0  4319.3     .05       0  5007.3     .03       0
  5013.3     .05       0
Bank Sta=4694.9,5027.3
XS Rating Curve= 0 ,0
Exp/Cntr=0.3,0.1

Type RM Length L Ch R = 1 ,15294   ,95,95,95
BEGIN DESCRIPTION:
Mapping XS 185462a8
END DESCRIPTION:
XS GIS Cut Line= 2
      3664116.34     10671242.88      3663038.27     10671539.74
#Sta/Elev= 30
  4341.4  281.77  4410.6  278.18  4425.8   276.4  4455.7  275.37  4573.7  270.48
  4628.4  269.82  4665.6  268.79  4773.6  267.84  4815.1  268.67  4882.6  268.39
  4960.3  269.96  4988.4  267.84  4993.5  266.71  4998.8  263.84  5001.6  263.34
  5004.8  263.84  5022.6  266.21  5027.9  267.96  5053.7  269.94  5064.3  270.31
  5167.8     273  5209.3  275.12  5261.1  279.21  5288.6     279    5329  279.11
  5334.2  279.93  5354.5  279.92  5368.6  281.87  5421.6   283.2  5459.6  281.52
#Mann= 9 ,-1 , 0
  4341.4     .05       0  4455.7     .08       0  4665.6     .05       0
  4882.6     .16       0  4998.8     .07       0  5004.8     .16       0
  5064.3     .05       0  5288.6     .08       0  5421.6     .05       0
Bank Sta=4628.4,5053.7
XS Rating Curve= 0 ,0
Exp/Cntr=0.3,0.1

Type RM Length L Ch R = 1 ,15199   ,128,128,128
BEGIN DESCRIPTION:
Mapping XS 3bffd59c
END DESCRIPTION:
XS GIS Cut Line= 2
      3664090.28     10671172.57      3662986.13     10671453.82
#Sta/Elev= 30
  4328.5  279.73  4349.8   279.9  4360.1  277.67  4377.6  276.72  4514.9  271.49
    4683  268.51  4699.6  268.39  4829.8  267.25  4906.3  268.93  4917.4  269.73
    4945  267.65  4979.3  267.83    4988  263.56  4990.8  263.06    4994  263.56
  4999.9  266.11  5020.6  268.54  5030.7  269.67  5179.3   271.4  5237.3  274.47
    5313  276.21  5348.8  274.53  5353.9     276  5371.4  275.97  5389.7  273.05
  5394.8  273.72  5402.4  270.76  5430.6  270.12  5448.6  271.55  5467.9  271.36
#Mann= 9 ,-1 , 0
  4328.5     .08       0    4683     .05       0  4829.8     .08       0
  4906.3     .16       0    4988     .07       0    4994     .16       0
  5030.7     .05       0  5179.3     .08       0  5448.6     .05       0
Bank Sta=4699.6,5020.6
XS Rating Curve= 0 ,0
Exp/Cntr=0.3,0.1

Type RM Length L Ch R = 1 ,15071   ,180,180,180
BEGIN DESCRIPTION:
UNT 0417 IN LACR 17.0
END DESCRIPTION:
XS GIS Cut Line= 3
      3664094.63      10671051.8       3662844.6     10671359.97
      3662393.35     10671444.23
#Sta/Elev= 30
  4311.2  277.16  4378.2  275.32  4400.5  273.29  4625.4  267.31  4708.1  266.65
  4790.1  267.04    4821  265.37  4831.6  266.93  4893.1  267.29  4914.6  265.59
  4965.2  267.53  4994.5  263.08  4997.3  262.58  5000.5  263.08  5006.4  265.75
  5033.9   268.3    5039  267.05  5057.9   268.7  5085.2  267.75  5315.4  268.35
  5531.3  266.91  5603.7  267.39  5733.5  265.07  5746.2  266.37  5772.5  265.02
  5888.6  265.27  5908.9  266.86  5954.3  268.97  5990.3  268.19  6057.7  271.72
#Mann= 8 ,-1 , 0
  4311.2     .05       0  4400.5     .08       0  4708.1     .05       0
  4994.5     .03       0  5000.5     .05       0  5085.2     .08       0
  5531.3     .05       0  5772.5     .08       0
Bank Sta=4625.4,5908.9
XS Rating Curve= 0 ,0
Exp/Cntr=0.3,0.1

Type RM Length L Ch R = 1 ,14891   ,296,296,296
BEGIN DESCRIPTION:
Mapping XS fbd29b2f
END DESCRIPTION:
XS GIS Cut Line= 3
      3664131.03     10670993.43      3663589.36      10671040.3
        3662355.     10671399.67
#Sta/Elev= 30
  4358.3  275.44  4381.8  275.34  4489.9  270.88    4495  271.51  4530.4  269.32
    4711  264.87  4771.3  266.48  4801.4  265.31  4891.7  266.58  4899.4  265.66
  4943.4  265.95  4974.6  266.96  4985.1  265.87  4987.6  262.98  4990.4  262.48
  5005.9     266  5024.1  266.99  5047.5  266.23  5062.9   267.2  5135.1  267.08
  5193.4   266.1    5235  267.29  5412.1  265.57  5589.1  265.74  5996.6  263.82
  6047.4  265.74  6089.1  265.65  6130.6  267.68  6135.9  268.92  6187.6  269.67
#Mann= 1 ,-1 , 0
  4358.3     .08       0
#XS Ineff= 2 , 0
         4731.78  271.43 5618.88           271.3
Permanent Ineff=
       F       F
Bank Sta=4974.6,5024.1
XS Rating Curve= 0 ,0
Exp/Cntr=0.3,0.1

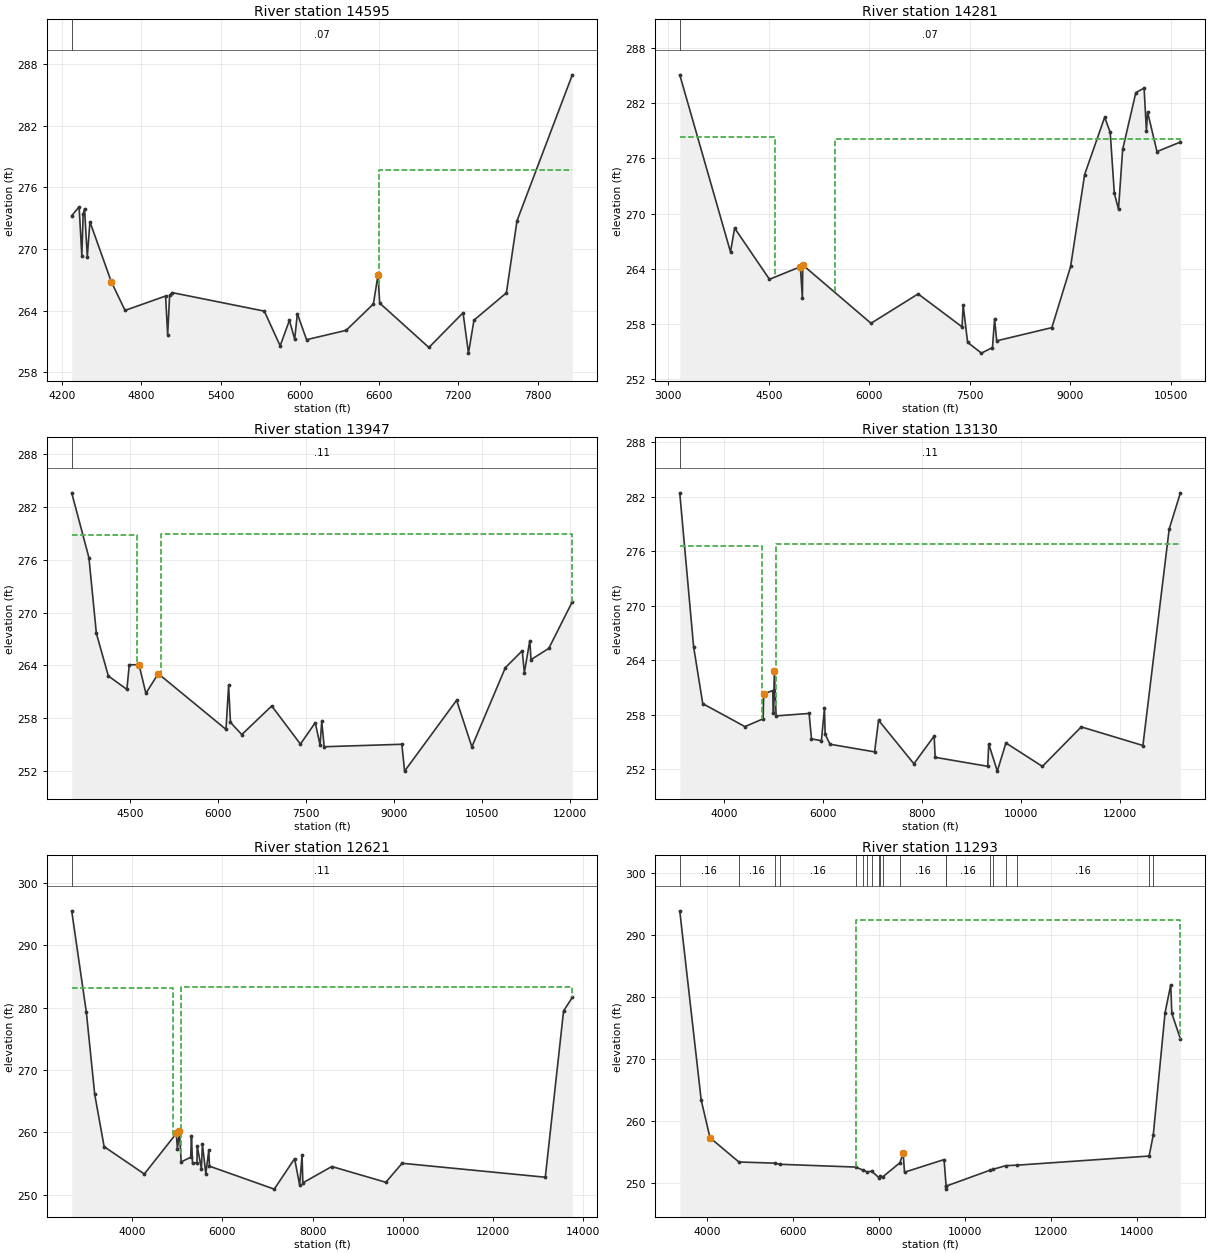
Type RM Length L Ch R = 1 ,14595   ,314,314,314
BEGIN DESCRIPTION:
UNT 0417 IN LACR 16.0
END DESCRIPTION:
XS GIS Cut Line= 4
      3664284.58     10670939.24      3663242.93     10670713.55
       3662097.1     10670706.61      3660569.69     10671112.93
#Sta/Elev= 30
  4271.5  273.24  4327.7   274.1  4348.2  269.36  4358.4  273.38  4368.7  273.92
  4389.7  269.26  4409.6  272.65  4571.1  266.82  4675.6  264.02  4982.6  265.42
  4998.5  261.64  5013.3   265.5  5033.8  265.75  5730.6  263.95  5850.6  260.57
  5920.7  263.05  5960.7  261.22  5980.7   263.7  6050.7  261.17  6350.7  262.08
  6556.8  264.65  6591.8  267.46  6604.7  264.73  6977.3  260.41    7236  263.79
  7277.1  259.86  7318.7  263.07  7564.4  265.73  7644.7  272.75  8063.7  286.96
#Mann= 1 ,-1 , 0
  4271.5     .07       0
#XS Ineff= 2 , 0
                         6596.59          277.65
Permanent Ineff=
       F       F
Bank Sta=4571.1,6591.8
XS Rating Curve= 0 ,0
Exp/Cntr=0.3,0.1

Type RM Length L Ch R = 1 ,14281   ,334,334,334
BEGIN DESCRIPTION:
UNT 0417 IN LACR 15.0
END DESCRIPTION:
XS GIS Cut Line= 4
      3665440.12     10670912.93      3663968.38      10670601.5
      3662025.92     10669855.28      3658265.55     10670821.87
#Sta/Elev= 30
  3172.5  285.11  3929.4  265.82  3990.7  268.42  4510.5  262.84  4971.7  264.21
  5001.7   260.8  5007.6   264.4  6025.3  258.05  6728.5  261.25  7383.7  257.66
  7399.6  260.03  7466.3  255.98  7672.6   254.8  7837.4  255.41    7869  258.55
    7900  256.14  8723.2  257.58  9003.2  264.24    9212  274.25  9510.7  280.49
  9593.3  278.85  9655.2   272.2  9717.2  270.47  9779.1  276.98  9975.6  283.17
 10099.2  283.67 10133.4     279 10150.8  281.07 10291.2  276.75 10640.3  277.79
#Mann= 1 ,-1 , 0
  3172.5     .07       0
#XS Ineff= 2 , 0
         4586.62  278.32 5485.07          278.15
Permanent Ineff=
       F       F
Bank Sta=4971.7,5007.6
XS Rating Curve= 0 ,0
Exp/Cntr=0.3,0.1

Type RM Length L Ch R = 1 ,13947   ,817,817,817
BEGIN DESCRIPTION:
UNT 0417 IN LACR 14.0
END DESCRIPTION:
XS GIS Cut Line= 4
      3665184.05     10670626.47      3664055.54     10670305.28
      3662022.88     10669338.79       3657066.6     10670582.87
#Sta/Elev= 30
  3505.3   283.6    3799  276.24  3925.8  267.65  4129.8  262.81  4445.7  261.28
  4487.2  264.08  4653.6  264.07  4770.1  260.83  4980.1  263.07  6135.7  256.74
    6180  261.73  6211.8  257.54  6404.6  256.15  6915.4   259.4  7404.7  255.07
  7656.8   257.5  7739.1  254.97  7767.9  257.68  7809.1  254.77  9133.3  255.05
  9180.1     252   10067  260.05 10326.9  254.76 10897.9  263.75   11186  265.67
 11221.8  263.18 11314.7  266.82 11335.2  264.66 11638.8  265.94 12039.4  271.24
#Mann= 1 ,-1 , 0
  3505.3     .11       0
#XS Ineff= 2 , 0
         4611.36  278.78 5027.27          278.95
Permanent Ineff=
       F       F
Bank Sta=4653.6,4980.1
XS Rating Curve= 0 ,0
Exp/Cntr=0.3,0.1

Type RM Length L Ch R = 1 ,13130   ,509,509,509
BEGIN DESCRIPTION:
UNT 0417 IN LACR 13.0
END DESCRIPTION:
XS GIS Cut Line= 4
      3665838.54     10670148.75       3662506.2     10668791.23
      3661577.38     10668773.87      3656108.28     10669896.24
#Sta/Elev= 30
  3102.9   282.4  3382.6  265.47  3567.2  259.21  4419.1  256.68  4786.9  257.54
    4797  260.28  4980.6  260.65  4995.5  258.19    5013  262.82    5049  257.86
  5715.1  258.13  5763.2  255.33  5963.2  255.13  6025.3  258.68  6038.8  255.85
  6137.7  254.74  7037.8   253.9  7117.8  257.38  7831.3  252.59  8240.4  255.64
  8260.8   253.3  9322.4  252.31  9342.9  254.76  9516.2  251.78  9689.9  254.88
 10426.2   252.3   11211  256.65 12456.4   254.6 12987.3  278.43 13213.2  282.41
#Mann= 1 ,-1 , 0
  3102.9     .11       0
#XS Ineff= 2 , 0
         4761.36  276.59 5040.91          276.76
Permanent Ineff=
       F       F
Bank Sta=4797,5013
XS Rating Curve= 0 ,0
Exp/Cntr=0.3,0.1

Type RM Length L Ch R = 1 ,12621   ,1328,1328,1328
BEGIN DESCRIPTION:
UNT 0417 IN LACR 12.0
END DESCRIPTION:
XS GIS Cut Line= 4
      3666551.37      10669702.7      3664488.78     10669082.53
      3662275.82     10668087.33      3655848.83     10669176.05
#Sta/Elev= 30
  2657.4  295.56  2982.9  279.26  3167.7  266.11  3376.3  257.72  4267.3  253.33
  4977.8  259.84    5001  257.36  5047.3  260.21  5084.4  255.27  5295.3  256.01
    5313  259.41  5336.1  255.03  5434.2  255.17  5439.7  257.82  5532.3  254.19
  5555.5  258.12  5630.4  253.37  5698.4  257.22  5710.9  254.59    7148   250.9
  7598.9  255.79  7710.5  251.58    7765  256.34  7781.5   251.9  8423.9  254.53
  9621.1     252  9983.3  255.05 13157.2  252.81 13562.7  279.51 13756.2  281.66
#Mann= 1 ,-1 , 0
  2657.4     .11       0
#XS Ineff= 2 , 0
         4897.73  283.17    5075          283.29
Permanent Ineff=
       F       F
Bank Sta=4977.8,5047.3
XS Rating Curve= 0 ,0
Exp/Cntr=0.3,0.1

Type RM Length L Ch R = 1 ,11293   ,951,951,951
BEGIN DESCRIPTION:
UNT 0417 IN LACR 11.0
END DESCRIPTION:
XS GIS Cut Line= 4
      3666865.58     10669096.13      3665509.27     10668694.66
       3663511.6     10667584.88      3655657.61     10668836.44
#Sta/Elev= 30
  3357.3   293.9  3856.4  263.36  4061.2  257.29  4733.7  253.37  5572.7  253.18
  5683.5     253  7455.4  252.55    7622  252.05  7722.8  251.76  7823.6  251.89
  7990.1  250.86  8025.3  251.06  8077.5  250.94  8481.9  253.25  8557.7  254.82
  8588.6  251.72  9509.6  253.76  9557.2  249.49  9559.9  248.99  9563.2  249.49
 10581.8  252.05 10646.6  252.19 10949.1  252.78   11214  252.86 14282.4  254.33
 14379.2  257.75 14653.7  277.47 14785.3  281.94 14811.1  277.37 15010.1  273.23
#Mann= 20 ,-1 , 0
  3357.3     .16       0  4733.7     .16       0  5572.7     .16       0
  5683.5     .16       0  7455.4     .16       0    7622     .16       0
  7722.8     .16       0  7823.6     .16       0  7990.1     .16       0
  8025.3     .16       0  8077.5     .16       0  8481.9     .16       0
  9557.2     .16       0  9563.2     .16       0 10581.8     .16       0
 10646.6     .16       0 10949.1     .16       0   11214     .16       0
 14282.4     .16       0 14379.2     .16       0
#XS Ineff= 2 , 0
                         7464.77          292.34
Permanent Ineff=
       F       F
Bank Sta=4061.2,8557.7
XS Rating Curve= 0 ,0
Exp/Cntr=0.3,0.1

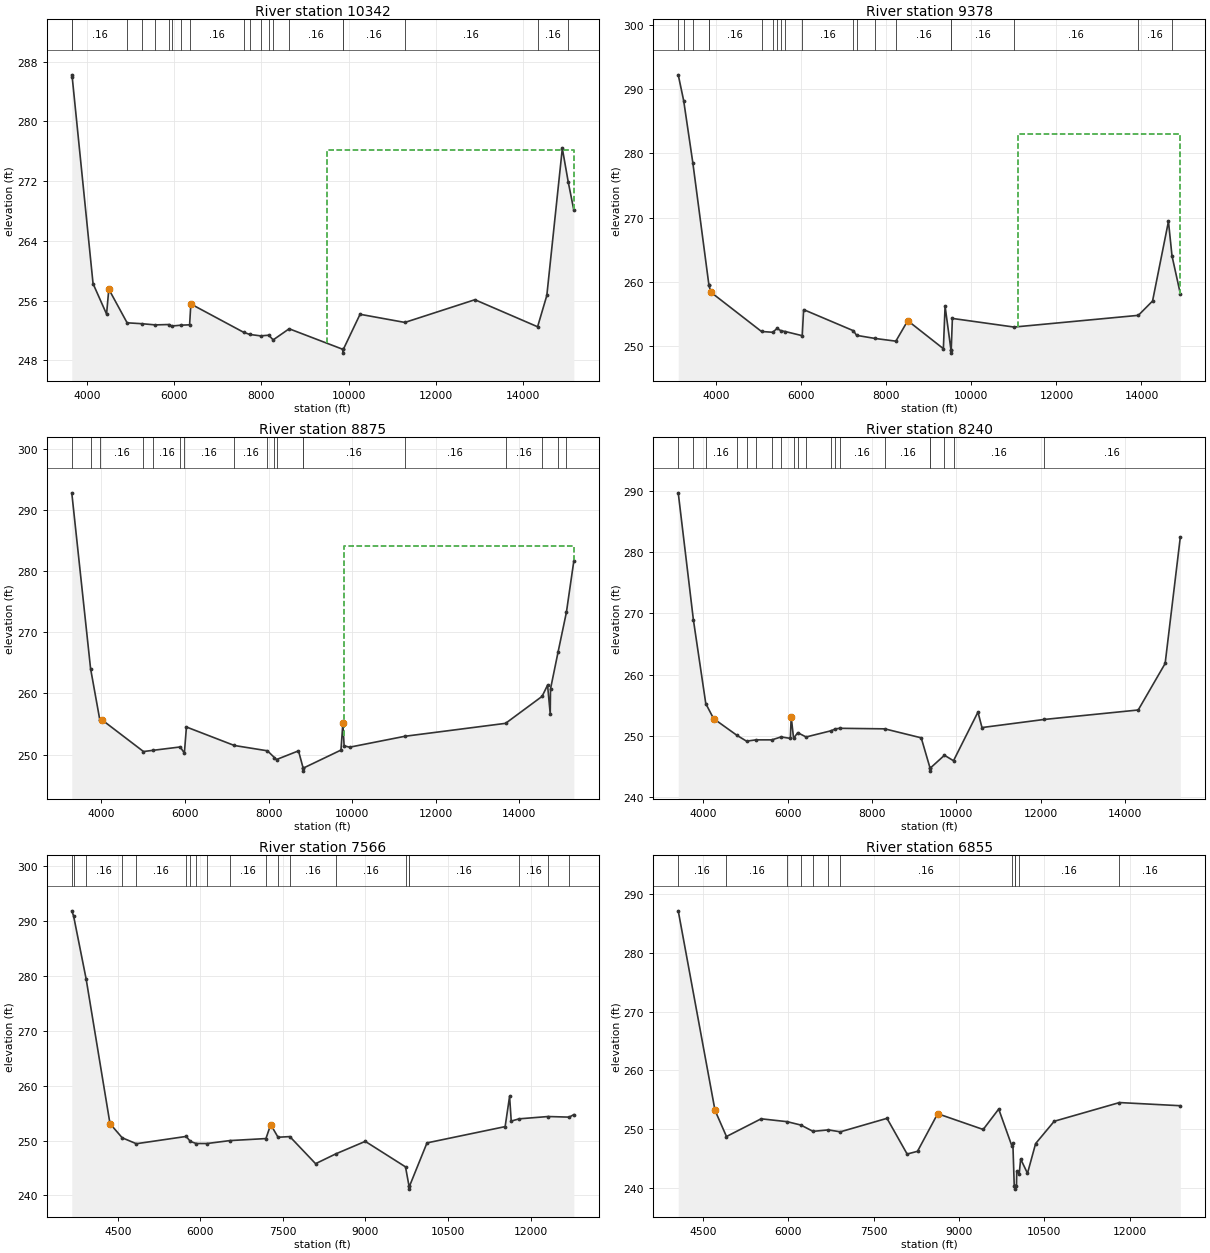
Type RM Length L Ch R = 1 ,10342   ,964,964,964
BEGIN DESCRIPTION:
Mapping XS 21433087
END DESCRIPTION:
XS GIS Cut Line= 4
       3666952.4     10668390.84      3665367.07     10667985.83
      3663590.24     10667516.22      3655633.83     10668642.34
#Sta/Elev= 30
  3652.8  286.23  3662.4  285.95  4140.8  258.27  4450.4   254.2    4502  257.53
  4921.4  253.03  5259.1  252.91    5567  252.75  5881.2   252.8  5948.9   252.6
  6151.5  252.71  6354.1  252.76  6382.5  255.55  7592.5  251.76  7733.7  251.47
  7982.7  251.28  8169.1  251.37  8269.6  250.74  8636.4  252.23  9871.6  249.47
  9874.4  248.97  9877.6  249.47 10261.4  254.17 11289.1  253.08 12894.4  256.12
 14331.6   252.5 14543.2  256.69 14898.4  276.38 15034.8  271.86 15162.6   268.1
#Mann= 20 ,-1 , 0
  3652.8     .16       0  3662.4     .16       0  4921.4     .16       0
  5259.1     .16       0    5567     .16       0  5881.2     .16       0
  5948.9     .16       0  6151.5     .16       0  6354.1     .16       0
  7592.5     .16       0  7733.7     .16       0  7982.7     .16       0
  8169.1     .16       0  8269.6     .16       0  8636.4     .16       0
  9871.6     .16       0  9877.6     .16       0 11289.1     .16       0
 14331.6     .16       0 15034.8     .16       0
#XS Ineff= 2 , 0
                         9501.14          276.15
Permanent Ineff=
       F       F
Bank Sta=4502,6382.5
XS Rating Curve= 0 ,0
Exp/Cntr=0.3,0.1

Type RM Length L Ch R = 1 ,9378    ,503,503,503
BEGIN DESCRIPTION:
Mapping XS 64b1803f
END DESCRIPTION:
XS GIS Cut Line= 3
      3667267.05     10667360.03      3663881.67     10667327.48
      3655539.24      10668452.6
#Sta/Elev= 30
  3109.1  292.19  3236.9  288.18  3452.3  278.52  3829.6  259.57  3831.5  259.49
  3876.6  258.42  5066.7  252.32  5331.7   252.2  5430.6  252.79  5529.5  252.42
  5628.4  252.31  6024.1  251.67  6056.7  255.72  7227.6  252.44    7302  251.72
    7736  251.24  8225.3  250.82  8504.7     254  9342.3  249.65  9382.6  256.24
  9520.9  249.46  9523.6  248.96  9526.9  249.46  9554.2  254.35 11002.9  253.01
 13925.8  254.83   14260  257.05 14633.7  269.42 14717.3  264.06 14912.6   258.2
#Mann= 20 ,-1 , 0
  3109.1     .16       0  3236.9     .16       0  3452.3     .16       0
  3829.6     .16       0  3831.5     .16       0  5066.7     .16       0
  5331.7     .16       0  5430.6     .16       0  5529.5     .16       0
  5628.4     .16       0  6024.1     .16       0  7227.6     .16       0
    7302     .16       0    7736     .16       0  8225.3     .16       0
  9520.9     .16       0  9526.9     .16       0 11002.9     .16       0
 13925.8     .16       0 14717.3     .16       0
#XS Ineff= 2 , 0
                           11100          282.95
Permanent Ineff=
       F       F
Bank Sta=3876.6,8504.7
XS Rating Curve= 0 ,0
Exp/Cntr=0.3,0.1

Type RM Length L Ch R = 1 ,8875    ,635,635,635
BEGIN DESCRIPTION:
UNT 0417 IN LACR 10.0
END DESCRIPTION:
XS GIS Cut Line= 3
      3667060.88     10666795.79      3663611.08     10666925.94
      3655140.57      10668155.2
#Sta/Elev= 30
  3293.1  292.88  3743.4  264.06  3966.4  255.59  4024.9  255.63    5009  250.49
  5226.9  250.68  5887.6  251.24  5986.8  250.23  6036.3  254.51  7182.8  251.48
  7974.5  250.61  8143.1  249.49  8191.2  249.18  8717.3   250.6  8828.2  247.78
    8831  247.28  8834.2  247.78  9733.5  250.73  9778.3   255.1  9808.7  251.43
    9939   251.2 11262.6  252.99 13671.2  255.11 14544.7  259.53 14675.9  261.37
 14739.7  256.65 14746.1  260.74 14925.3  266.73 15126.4   273.3 15304.6  281.73
#Mann= 18 ,-1 , 0
  3293.1     .16       0  3743.4     .16       0  3966.4     .16       0
    5009     .16       0  5226.9     .16       0  5887.6     .16       0
  5986.8     .16       0  7182.8     .16       0  7974.5     .16       0
  8143.1     .16       0  8191.2     .16       0  8828.2     .16       0
  8834.2     .16       0 11262.6     .16       0 13671.2     .16       0
 14544.7     .16       0 14925.3     .16       0 15126.4     .16       0
#XS Ineff= 2 , 0
                         9795.45          284.23
Permanent Ineff=
       F       F
Bank Sta=4024.9,9778.3
XS Rating Curve= 0 ,0
Exp/Cntr=0.3,0.1

Type RM Length L Ch R = 1 ,8240    ,674,674,674
BEGIN DESCRIPTION:
UNT 0417 IN LACR 9.0
END DESCRIPTION:
XS GIS Cut Line= 4
      3667028.39     10666264.11      3663361.08     10666321.77
      3657790.29     10667171.88     3655206.941    10667508.761
#Sta/Elev= 30
  3401.5  289.69  3760.7  268.95  4054.9  255.24  4240.4  252.79  4793.8  250.06
  5021.2  249.11    5246  249.32  5622.9  249.32  5840.1   249.8  6060.6  249.56
  6080.6  253.09  6137.1  249.58  6236.2  250.49  6434.2  249.79  7028.3  250.81
  7128.3  251.11    7229  251.21  8299.5  251.12  9164.7  249.65  9374.1  244.71
  9376.9  244.21  9380.1  244.71  9715.4   246.8  9930.5  245.91 10510.1  253.86
 10605.7  251.33 12076.1  252.6514311.11   254.214949.84   261.8 15309.7  282.45
#Mann= 20 ,-1 , 0
  3401.5     .16       0  3760.7     .16       0  4054.9     .16       0
  4793.8     .16       0  5021.2     .16       0    5246     .16       0
  5622.9     .16       0  5840.1     .16       0  6137.1     .16       0
  6236.2     .16       0  6434.2     .16       0  7028.3     .16       0
  7128.3     .16       0    7229     .16       0  8299.5     .16       0
  9374.1     .16       0  9380.1     .16       0  9715.4     .16       0
  9930.5     .16       0 12076.1     .16       0
Bank Sta=4240.4,6080.6
XS Rating Curve= 0 ,0
Exp/Cntr=0.3,0.1

Type RM Length L Ch R = 1 ,7566    ,711,711,711
BEGIN DESCRIPTION:
UNT 0417 IN LACR 8.0
END DESCRIPTION:
XS GIS Cut Line= 3
      3666974.12     10665678.17      3663326.35     10665724.55
        3657890.     10666375.89
#Sta/Elev= 30
    3663  291.89  3696.2  290.95  3924.3  279.45  4357.6  253.08  4579.7   250.5
  4836.1  249.42  5742.3  250.75  5818.4  249.83  5925.1  249.46  6123.1  249.46
  6535.1  249.99  7191.2  250.36  7277.8  252.91  7411.3   250.6  7625.3  250.72
  8093.4  245.78  8463.4  247.58  8996.2  249.85  9727.3   245.2  9792.4  241.64
  9795.2  241.14  9798.4  241.64 10117.7  249.57 11537.8  252.54 11618.4  258.04
 11648.6  253.55 11793.5  253.96 12319.8  254.38 12701.8  254.27 12786.3  254.73
#Mann= 20 ,-1 , 0
    3663     .16       0  3696.2     .16       0  3924.3     .16       0
  4579.7     .16       0  4836.1     .16       0  5742.3     .16       0
  5818.4     .16       0  5925.1     .16       0  6123.1     .16       0
  6535.1     .16       0  7191.2     .16       0  7411.3     .16       0
  7625.3     .16       0  8463.4     .16       0  9727.3     .16       0
  9792.4     .16       0  9798.4     .16       0 11793.5     .16       0
 12319.8     .16       0 12701.8     .16       0
Bank Sta=4357.6,7277.8
XS Rating Curve= 0 ,0
Exp/Cntr=0.3,0.1

Type RM Length L Ch R = 1 ,6855    ,643,643,643
BEGIN DESCRIPTION:
UNT 0417 IN LACR 7.0
END DESCRIPTION:
XS GIS Cut Line= 3
      3666865.65     10665211.59      3663291.63      10665155.1
      3658105.93     10665951.71
#Sta/Elev= 30
  4066.5   287.2  4712.6  253.18    4914  248.72  5522.7  251.74    5981  251.25
  6222.4  250.67  6434.3   249.6  6704.9  249.85  6914.2  249.52  7734.1  251.82
  8088.2  245.73  8270.3   246.2  8624.4  252.61  9424.2  249.92  9696.8   253.4
    9928  247.12  9945.7  247.56    9970  240.26  9977.1  240.25  9979.9  239.75
  9983.1  240.25   10009  240.28   10014  242.78 10057.1  242.38 10082.4  244.88
 10202.7  242.45 10345.6  247.52 10672.1  251.32 11818.4  254.51 12887.5  253.97
#Mann= 12 ,-1 , 0
  4066.5     .16       0    4914     .16       0    5981     .16       0
  6222.4     .16       0  6434.3     .16       0  6704.9     .16       0
  6914.2     .16       0    9928     .16       0  9977.1     .16       0
  9983.1     .16       0 10057.1     .16       0 11818.4     .16       0
Bank Sta=4712.6,8624.4
XS Rating Curve= 0 ,0
Exp/Cntr=0.3,0.1