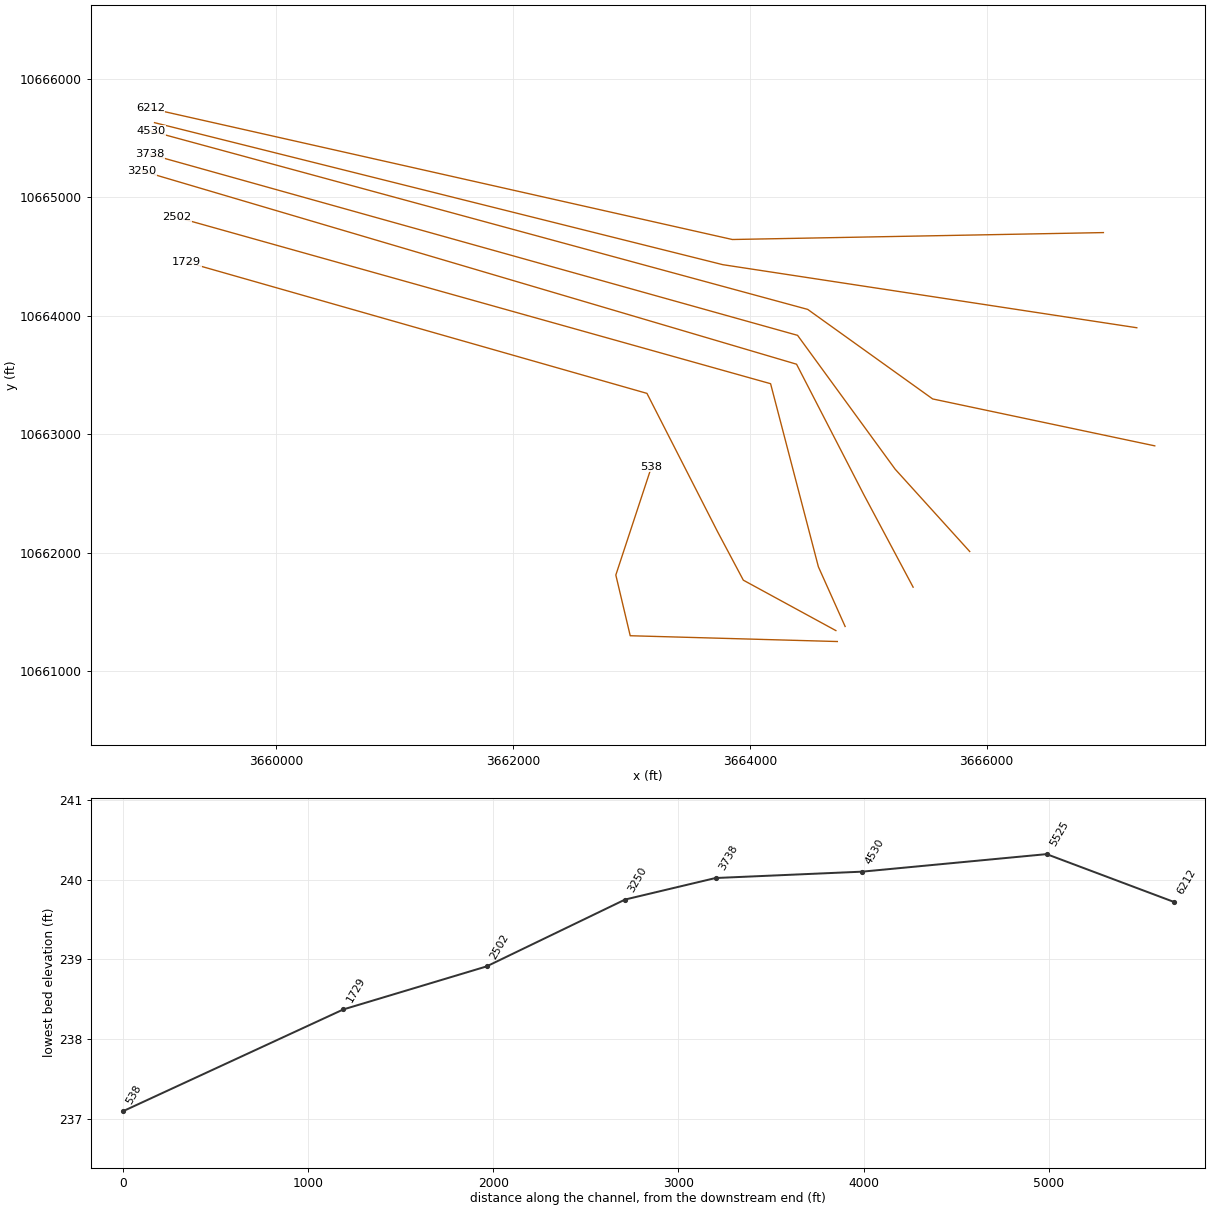
HEC-RAS study UNT 0417 IN LACR.prj: UNT 0417 IN LACR Base Level Engineering

--- UNT 0417 IN LACR.g01 (geometry) --- (continued)

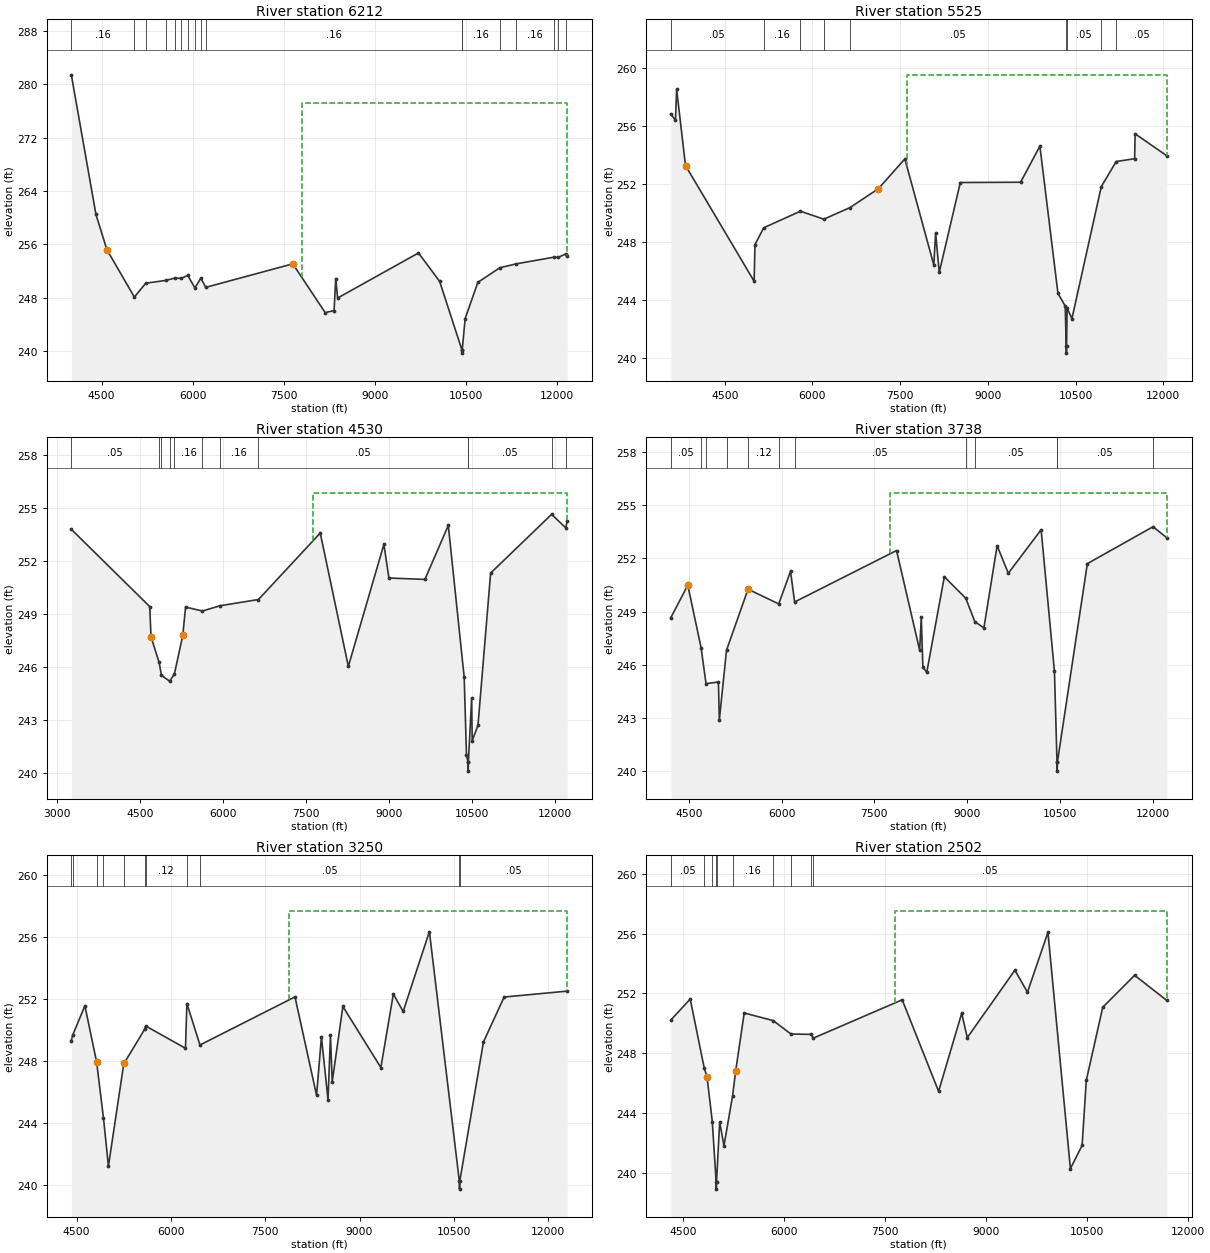
Type RM Length L Ch R = 1 ,6212    ,687,687,687
BEGIN DESCRIPTION:
UNT 0417 IN LACR 6.0
END DESCRIPTION:
XS GIS Cut Line= 3
      3666984.96     10664701.61      3663852.59     10664643.18
      3658939.37     10665748.84
#Sta/Elev= 30
    4001  281.39  4406.4  260.49  4586.5  255.21  5039.4  248.11  5227.6  250.19
  5559.1  250.61  5705.4  250.96  5814.2  250.92  5918.9  251.36  6035.7  249.49
  6134.6  250.94  6215.3  249.57  7649.5  253.09  8182.5  245.79  8329.2  246.08
  8356.7  250.88  8387.5  247.97    9720  254.72 10068.5  250.46 10434.5  240.22
 10437.2  239.72 10440.5  240.22 10488.7   244.9 10697.4  250.31 11061.2  252.51
   11332  253.09 11952.8  254.09 12020.7  254.05 12150.8   254.6   12170   254.2
#Mann= 17 ,-1 , 0
    4001     .16       0  5039.4     .16       0  5227.6     .16       0
  5559.1     .16       0  5705.4     .16       0  5814.2     .16       0
  5918.9     .16       0  6035.7     .16       0  6134.6     .16       0
  6215.3     .16       0 10434.5     .16       0 10440.5     .16       0
 11061.2     .16       0   11332     .16       0 11952.8     .16       0
 12020.7     .16       0 12150.8     .16       0
#XS Ineff= 2 , 0
                         7801.14          277.16
Permanent Ineff=
       F       F
Bank Sta=4586.5,7649.5
XS Rating Curve= 0 ,0
Exp/Cntr=0.3,0.1

Type RM Length L Ch R = 1 ,5525    ,995,995,995
BEGIN DESCRIPTION:
UNT 0417 IN LACR 5.0
END DESCRIPTION:
XS GIS Cut Line= 3
      3667267.09     10663898.65      3663772.32     10664430.79
      3658974.75     10665629.04
#Sta/Elev= 30
  3579.2  256.82  3657.6  256.38  3677.8  258.51  3829.5  253.26  5002.9  245.28
  5017.9  247.81  5167.2  248.97  5795.5  250.11  6195.1  249.56  6641.8  250.36
  7127.3  251.66  7580.9  253.72  8075.6   246.4  8106.5  248.61  8168.8  245.89
  8529.1  252.09  9559.9  252.11  9889.7   254.6 10198.9  244.44 10322.6  243.57
 10340.2  240.82 10342.9  240.32 10346.2  240.82   10355  243.43 10437.5   242.7
 10939.3   251.8 11194.4  253.54 11509.9  253.73 11518.2  255.45 12059.2  253.94
#Mann= 9 ,-1 , 0
  3579.2     .05       0  5167.2     .16       0  5795.5     .05       0
  6195.1     .16       0  6641.8     .05       0 10340.2     .03       0
 10346.2     .05       0 10939.3     .16       0 11194.4     .05       0
#XS Ineff= 2 , 0
                         7618.18          259.52
Permanent Ineff=
       F       F
Bank Sta=3829.5,7127.3
XS Rating Curve= 0 ,0
Exp/Cntr=0.3,0.1

Type RM Length L Ch R = 1 ,4530    ,792,792,792
BEGIN DESCRIPTION:
UNT 0417 IN LACR 4.0
END DESCRIPTION:
XS GIS Cut Line= 4
      3667418.66     10662902.18      3665543.67     10663298.02
      3664488.77     10664053.47      3658942.74     10665558.72
#Sta/Elev= 30
  3263.1  253.81  4679.6  249.43  4703.2  247.71  4848.7  246.27  4892.1  245.53
  5039.1   245.2  5124.1  245.59  5277.1   247.8  5327.5   249.4  5632.6  249.18
  5953.2  249.48  6644.2  249.83  7760.9   253.6  8268.6  246.04  8911.1  252.96
  9001.2  251.05  9652.1  250.97 10074.5  254.03 10361.7  245.43 10403.2  241.03
 10431.3   240.6   10434   240.1 10437.3   240.6 10496.9  244.24 10506.8  241.83
 10611.1   242.7 10839.6  251.33 11941.7  254.66 12195.7   253.9 12223.6  254.26
#Mann= 12 ,-1 , 0
  3263.1     .05       0  4848.7     .07       0  4892.1     .05       0
  5039.1     .12       0  5124.1     .16       0  5632.6     .05       0
  5953.2     .16       0  6644.2     .05       0 10431.3     .03       0
 10437.3     .05       0 11941.7     .16       0 12195.7     .05       0
#XS Ineff= 2 , 0
                            7625          255.88
Permanent Ineff=
       F       F
Bank Sta=4703.2,5277.1
XS Rating Curve= 0 ,0
Exp/Cntr=0.3,0.1

Type RM Length L Ch R = 1 ,3738    ,488,488,488
BEGIN DESCRIPTION:
UNT 0417 IN LACR 3.0
END DESCRIPTION:
XS GIS Cut Line= 4
      3665856.49     10662010.63      3665227.15     10662705.08
      3664403.16     10663834.58      3658933.55      10665362.8
#Sta/Elev= 30
  4211.8  248.67  4485.3   250.5  4699.7  246.98  4780.1  244.95  4980.6  245.04
  4994.8  242.89    5111  246.83  5458.9  250.27  5955.5  249.44  6145.6  251.28
  6211.7  249.55  7859.1  252.45  8232.8  246.83  8258.8  248.69  8284.8  245.89
  8347.1  245.58  8631.5  250.97  8977.9  249.76  9124.4  248.44  9271.1  248.09
  9484.6  252.72  9665.7  251.17 10195.8  253.62 10411.1  245.64 10452.7  240.52
 10455.4  240.02 10458.7  240.52 10942.8  251.71 12004.6  253.79 12226.2  253.17
#Mann= 12 ,-1 , 0
  4211.8     .05       0  4699.7     .16       0  4780.1     .12       0
    5111     .05       0  5458.9     .12       0  5955.5     .16       0
  6211.7     .05       0  8977.9     .07       0  9124.4     .05       0
 10452.7     .07       0 10458.7     .05       0 12004.6     .16       0
#XS Ineff= 2 , 0
                            7750           255.7
Permanent Ineff=
       F       F
Bank Sta=4485.3,5458.9
XS Rating Curve= 0 ,0
Exp/Cntr=0.3,0.1

Type RM Length L Ch R = 1 ,3250    ,748,748,748
BEGIN DESCRIPTION:
UNT 0417 IN LACR 2.0
END DESCRIPTION:
XS GIS Cut Line= 4
      3665378.69     10661709.85      3664960.92     10662493.22
      3664394.61     10663591.03      3658867.31     10665222.06
#Sta/Elev= 30
  4416.5  249.32  4439.7  249.68  4632.1  251.56  4818.8  247.93  4927.6  244.33
  5006.2  241.23  5251.9  247.86  5252.5  247.83  5582.4  250.04  5596.5  250.26
  6231.7  248.82  6254.2   251.7    6462  249.03  7973.2  252.13  8316.5  245.79
  8393.5  249.55  8498.7   245.5  8537.2  249.66  8565.3  246.66  8734.3  251.51
    9339  247.58  9537.1  252.31  9693.5  251.19 10110.6  256.33 10587.2  240.25
 10589.9  239.75 10593.2  240.25 10970.8  249.23 11299.2  252.12 12302.5   252.5
#Mann= 11 ,-1 , 0
  4416.5     .12       0  4439.7     .05       0  4818.8     .16       0
  4927.6     .12       0  5252.5     .05       0  5582.4     .07       0
  5596.5     .12       0  6254.2     .16       0    6462     .05       0
 10587.2     .07       0 10593.2     .05       0
#XS Ineff= 2 , 0
                            7875          257.67
Permanent Ineff=
       F       F
Bank Sta=4818.8,5251.9
XS Rating Curve= 0 ,0
Exp/Cntr=0.3,0.1

Type RM Length L Ch R = 1 ,2502    ,773,773,773
BEGIN DESCRIPTION:
Mapping XS 39b2415c
END DESCRIPTION:
XS GIS Cut Line= 4
      3664804.68     10661378.14      3664578.97     10661881.64
      3664175.45     10663426.56      3659160.32     10664831.42
#Sta/Elev= 30
  4323.8  250.22    4611  251.62  4819.4  246.99  4859.7  246.44  4938.4  243.42
  4995.1  239.41  4997.8  238.91  5001.1  239.41  5047.9   243.4  5111.8  241.81
  5239.3  245.15  5285.4  246.81    5412  250.69  5841.3  250.18    6106  249.28
  6403.3  249.26  6438.9  249.01  7755.7  251.57  8295.8  245.45  8638.5  250.67
  8721.5  249.04  9427.7  253.55  9613.9  252.08    9918  256.08   10251  240.28
 10424.7  241.83   10487  246.18 10730.8  251.07 11203.5  253.21 11680.5  251.53
#Mann= 10 ,-1 , 0
  4323.8     .05       0  4819.4     .16       0  4938.4     .12       0
  4995.1     .07       0  5001.1     .12       0  5239.3     .16       0
  5841.3     .12       0    6106     .05       0  6403.3     .07       0
  6438.9     .05       0
#XS Ineff= 2 , 0
                         7654.55          257.52
Permanent Ineff=
       F       F
Bank Sta=4859.7,5285.4
XS Rating Curve= 0 ,0
Exp/Cntr=0.3,0.1

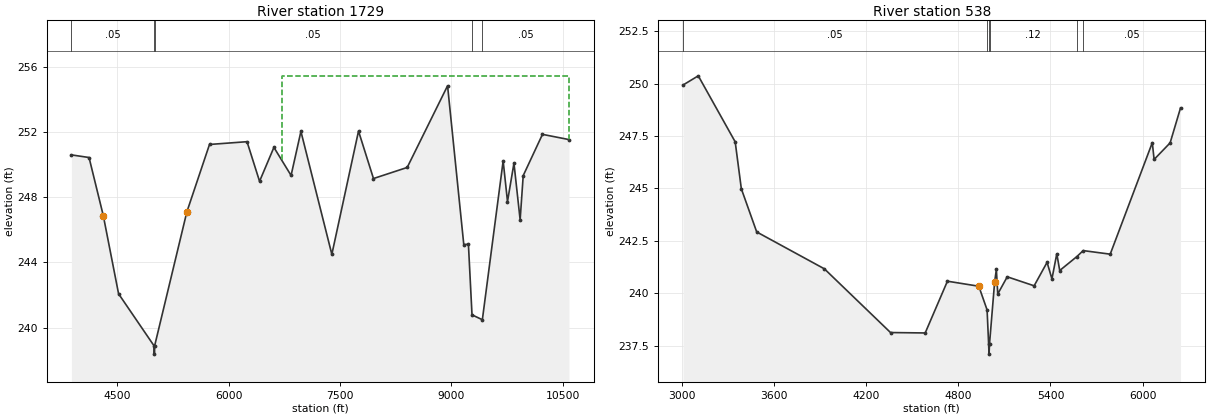
Type RM Length L Ch R = 1 ,1729    ,1191,1191,1191
BEGIN DESCRIPTION:
Mapping XS bd55e2f2
END DESCRIPTION:
XS GIS Cut Line= 5
      3664726.52     10661343.45      3663945.29     10661768.79
      3663728.28     10662176.78      3663131.68     10663344.87
      3659247.13     10664451.64
#Sta/Elev= 30
  3880.2  250.59  4117.7  250.43  4309.4  246.87  4515.6  242.07  4994.8  238.87
  4997.6  238.37  5000.8  238.87    5435  247.09  5740.4  251.23  6245.9   251.4
  6414.7  248.97    6608  251.05  6839.3  249.33  6971.9  252.03  7388.5  244.49
  7747.8  252.05  7949.3  249.14  8403.7  249.82  8947.5  254.83  9165.9  245.09
  9228.3  245.11  9276.7  240.78  9416.1  240.48  9696.2  250.22  9754.8  247.73
  9841.8  250.08    9925  246.61  9966.5  249.32 10225.9  251.85 10582.6  251.53
#Mann= 5 ,-1 , 0
  3880.2     .05       0  4994.8     .03       0  5000.8     .05       0
  9276.7     .12       0  9416.1     .05       0
#XS Ineff= 2 , 0
                         6713.64          255.44
Permanent Ineff=
       F       F
Bank Sta=4309.4,5435
XS Rating Curve= 0 ,0
Exp/Cntr=0.3,0.1

Type RM Length L Ch R = 1 ,538     ,0,0,0
BEGIN DESCRIPTION:
UNT 0417 IN LACR 1.0
END DESCRIPTION:
XS GIS Cut Line= 4
      3664738.86     10661251.09      3662990.43     10661300.04
       3662868.9     10661812.19       3663169.7     10662724.61
#Sta/Elev= 30
  3009.8  249.93  3109.1  250.37  3349.2  247.22  3389.2  244.98  3489.2  242.92
  3929.4  241.16  4359.6  238.12  4585.1   238.1  4729.7  240.57  4933.8  240.33
  4987.7   239.2  4997.6  237.59  5000.4  237.09  5003.6  237.59  5036.6  240.52
    5048  241.13  5057.1  239.96  5118.8  240.78  5293.7  240.35  5377.9  241.47
  5409.5  240.68  5441.1  241.88  5460.1  241.08  5570.9  241.74  5612.9  242.03
  5788.6  241.86  6062.3  247.18  6074.1  246.38  6178.2  247.17    6246  248.84
#Mann= 6 ,-1 , 0
  3009.8     .05       0  4987.7     .12       0  4997.6     .07       0
  5003.6     .12       0  5570.9     .16       0  5612.9     .05       0
Bank Sta=4933.8,5036.6
XS Rating Curve= 0 ,0
Exp/Cntr=0.3,0.1

Chan Stop Cuts=-1
Use User Specified Reach Order=0
Composite Channel Slope=5