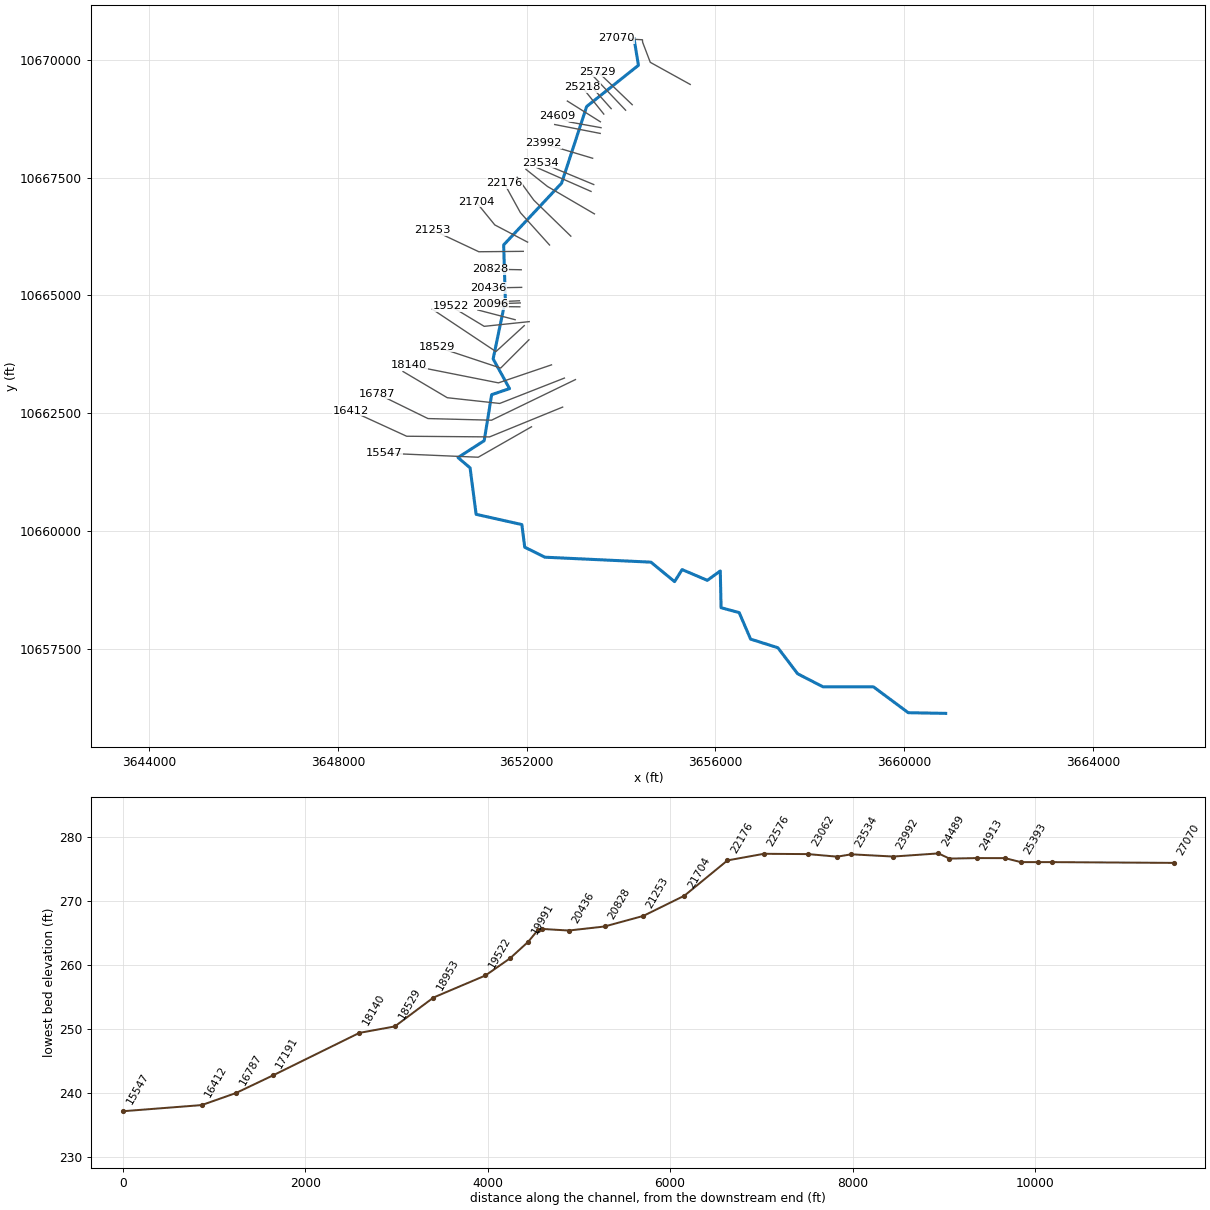
--- UNT 0419 IN LACR.prj (project) ---

Proj Title=UNT 0419 IN LACR Base Level Engineering
Current Plan=p01
Default Exp/Contr=0.3,0.1
English Units
Geom File=g01
Flow File=f01
Plan File=p01
Y Axis Title=Elevation
X Axis Title(PF)=Main Channel Distance
X Axis Title(XS)=Station
BEGIN DESCRIPTION:
UNT 0419 IN LACR
END DESCRIPTION:
DSS Export Rating Curves= 0
DSS Export Rating Curve Sorted= 0
DSS Export Volume Flow Curves= 0
DXF OffsetX= 0
DXF OffsetY= 0
DXF ScaleX= 1
DXF ScaleY= 10

--- UNT 0419 IN LACR.p01 (plan) ---

Plan Title=Multiple Run
Short Identifier=Multiple
Geom File=g01
Flow File=f01
Subcritical Flow
K Sum by GR= 0
Std Step Tol= 0.01
Critical Tol= 0.01
Num of Std Step Trials= 20
Max Error Tol= 0.3
Flow Tol Ratio= 0.001
Split Flow NTrial= 30
Split Flow Tol= 0.02
Split Flow Ratio= 0.02
Log Output Level= 0
Friction Slope Method= 1
Unsteady Friction Slope Method= 2
Unsteady Bridges Friction Slope Method= 1
Parabolic Critical Depth
Global Vel Dist=  1 , 1 , 1
Global Log Level= 0
CheckData=True
Encroach Param= -1, 0, 0, 0
BEGIN DESCRIPTION:
Multiple Run
END DESCRIPTION:

--- UNT 0419 IN LACR.f01 (steady flow) ---

Flow Title=Multiple
Program Version=4.10
Number of Profiles= 7
Profile Names=10-year,25-year,50-year,1pct_min,100-year,1pct_plu,500-year
River Rch & RM=UNT 0419 IN LACR,Reach-1         ,27070
     312     401     470     405     547     740     746
River Rch & RM=UNT 0419 IN LACR,Reach-1         ,25729
     312     401     470     405     547     740     746
Boundary for River Rch & Prof#=UNT 0419 IN LACR,Reach-1         , 1
Up Type= 0
Dn Type= 3
Dn Slope=0.001
Boundary for River Rch & Prof#=UNT 0419 IN LACR,Reach-1         , 2
Up Type= 0
Dn Type= 3
Dn Slope=0.001
Boundary for River Rch & Prof#=UNT 0419 IN LACR,Reach-1         , 3
Up Type= 0
Dn Type= 3
Dn Slope=0.001
Boundary for River Rch & Prof#=UNT 0419 IN LACR,Reach-1         , 4
Up Type= 0
Dn Type= 3
Dn Slope=0.001
Boundary for River Rch & Prof#=UNT 0419 IN LACR,Reach-1         , 5
Up Type= 0
Dn Type= 3
Dn Slope=0.001
Boundary for River Rch & Prof#=UNT 0419 IN LACR,Reach-1         , 6
Up Type= 0
Dn Type= 3
Dn Slope=0.001
Boundary for River Rch & Prof#=UNT 0419 IN LACR,Reach-1         , 7
Up Type= 0
Dn Type= 3
Dn Slope=0.001
DSS Import GetInterval= 0
DSS Import GetPeak= 0
DSS Import FillOption= 0

--- UNT 0419 IN LACR.g01 (geometry) ---

Geom Title=Existing Conditions
Program Version=4.10

River Reach=UNT 0419 IN LACR,Reach-1
Reach XY= 30
        3654277.       10670445.      3654369.01     10669880.75
      3653271.75       10669007.        3652741.       10667382.
        3651513.       10666072.      3651549.25       10664900.
       3651290.5       10663655.       3651637.5       10663025.
        3651259.       10662897.      3651100.75       10661921.
        3650546.       10661563.      3650801.75       10661344.
      3650929.75       10660359.        3651899.       10660142.
      3651959.75       10659662.       3652385.5       10659450.
      3654633.75       10659345.      3655135.25       10658932.
       3655294.5       10659187.       3655829.5       10658959.
      3656103.75       10659158.      3656120.75       10658379.
      3656504.75       10658275.      3656746.25       10657713.
      3657324.25       10657530.        3657743.       10656978.
      3658279.25       10656702.      3659350.75       10656700.
       3660087.5       10656152.       3660880.5       10656138.

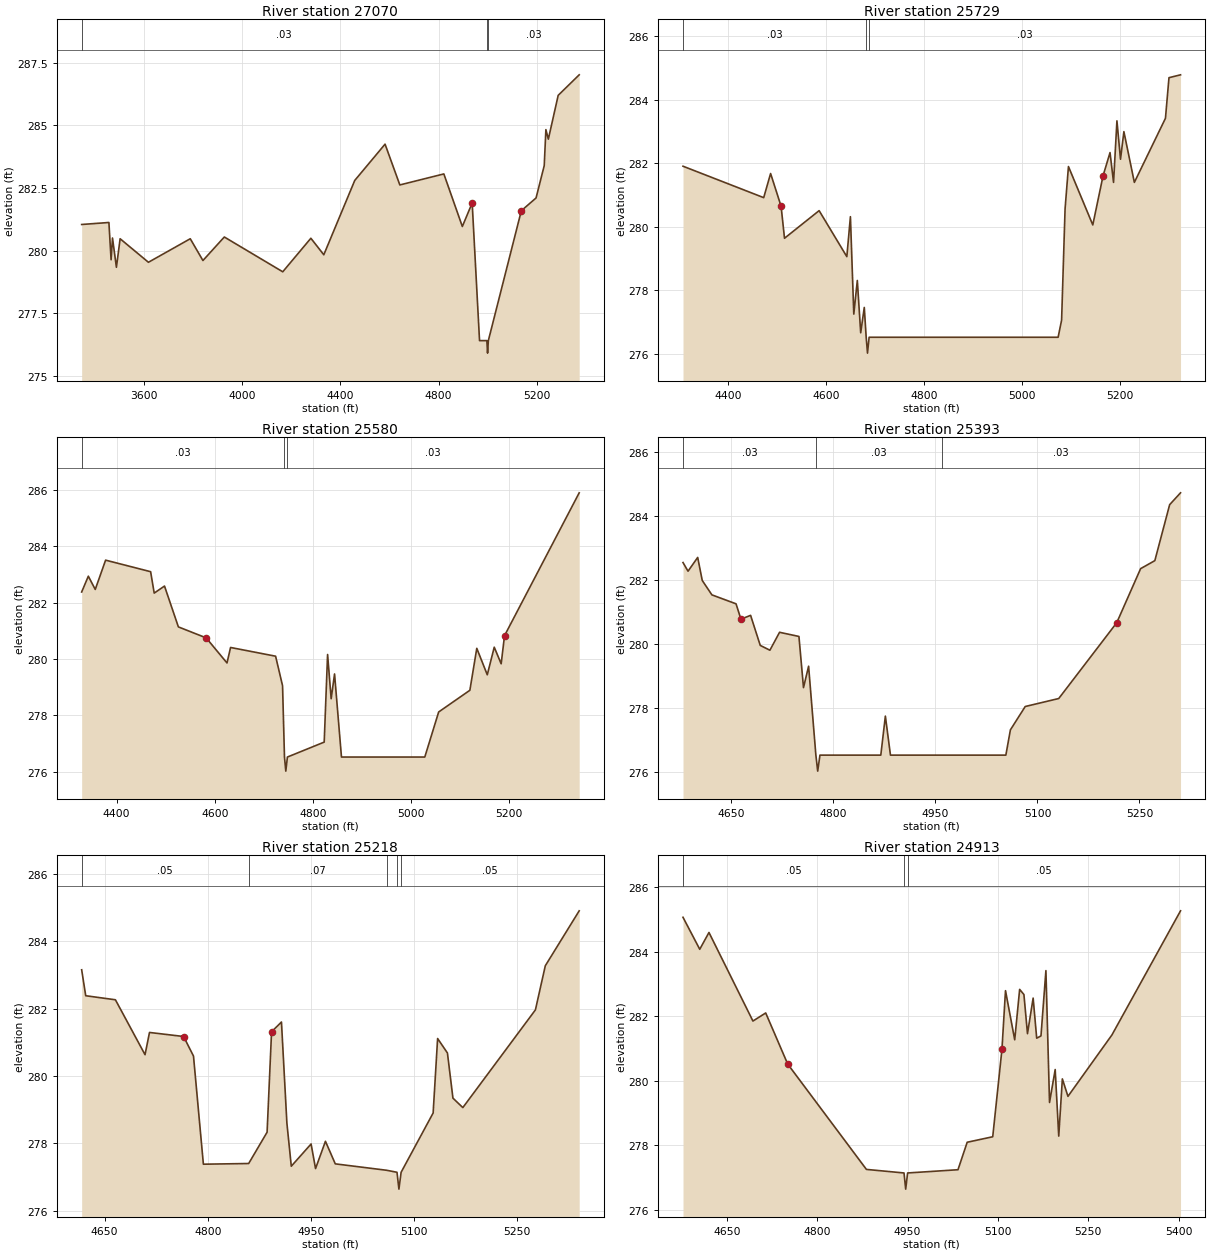
Type RM Length L Ch R = 1 ,27070   ,1341,1341,1341
BEGIN DESCRIPTION:
Mapping XS 5384eb4e
END DESCRIPTION:
XS GIS Cut Line= 5
       3655466.7     10669475.57      3654620.37     10669944.31
      3654458.19     10670370.52      3654454.83     10670422.78
      3653904.12     10670453.13
#Sta/Elev= 30
  3345.8  281.04  3456.8  281.12  3465.7  279.63  3471.4   280.5  3487.4  279.33
  3502.5  280.47  3617.9  279.53  3788.3  280.47    3840   279.6  3927.1  280.54
  4165.2  279.15  4279.8  280.49  4332.5  279.83  4458.6   282.8  4582.1  284.25
  4642.3  282.62  4821.7  283.06    4897  280.96  4937.1   281.9  4967.1   276.4
    4997   276.4  4999.8   275.9    5003   276.4  5137.4  281.59  5197.4   282.1
  5230.7  283.39  5237.5  284.83  5247.5  284.45  5287.6   286.2  5373.2  287.02
#Mann= 3 ,-1 , 0
  3345.8     .03       0    4997     .03       0    5003     .03       0
Bank Sta=4937.1,5137.4
XS Rating Curve= 0 ,0
Exp/Cntr=0.3,0.1

Type RM Length L Ch R = 1 ,25729   ,149,149,149
BEGIN DESCRIPTION:
UNT 0419 IN LACR 29.0
END DESCRIPTION:
XS GIS Cut Line= 2
       3654238.1     10669045.49      3653504.17      10669748.2
#Sta/Elev= 30
  4307.7  281.91  4472.5  280.92  4486.6  281.68    4508  280.65    4515  279.64
  4585.7  280.51  4642.3  279.06  4649.6  280.32  4656.5  277.25  4663.7  278.31
  4670.6  276.66  4677.9  277.46  4681.8  276.52  4684.5  276.02  4687.8  276.52
  5073.8  276.52  5080.9  277.06    5088  280.57  5094.9   281.9  5144.6  280.06
  5165.6  281.61  5179.8  282.34    5187   281.4  5193.9  283.34  5201.2  282.13
  5208.1     283  5229.5   281.4    5293  283.42  5300.2   284.7  5323.8  284.79
#Mann= 3 ,-1 , 0
  4307.7     .03       0  4681.8    .035       0  4687.8     .03       0
Bank Sta=4508,5165.6
XS Rating Curve= 0 ,0
Exp/Cntr=0.3,0.1

Type RM Length L Ch R = 1 ,25580   ,187,187,187
BEGIN DESCRIPTION:
Mapping XS 6254f000
END DESCRIPTION:
XS GIS Cut Line= 2
      3654097.52     10668929.13      3653399.59     10669665.26
#Sta/Elev= 30
  4328.7  282.38  4342.3  282.94  4356.4  282.47  4377.5  283.51  4469.3   283.1
  4476.6  282.34  4497.6  282.59  4525.9  281.14  4582.6  280.75    4625  279.86
  4632.3  280.41  4724.1   280.1  4738.3  279.05  4742.2  276.52  4744.9  276.02
  4748.2  276.52  4823.2  277.05  4830.1  280.16  4837.4  278.59  4844.3  279.47
  4858.4  276.52  5028.3  276.52  5056.6  278.12  5120.2  278.89  5134.3  280.38
  5155.7  279.44  5169.9  280.42    5184  279.83  5190.9  280.83  5343.1   285.9
#Mann= 3 ,-1 , 0
  4328.7     .03       0  4742.2     .03       0  4748.2     .03       0
Bank Sta=4582.6,5190.9
XS Rating Curve= 0 ,0
Exp/Cntr=0.3,0.1

Type RM Length L Ch R = 1 ,25393   ,175,175,175
BEGIN DESCRIPTION:
Mapping XS b0fbda40
END DESCRIPTION:
XS GIS Cut Line= 2
      3653791.53     10668961.92      3653305.42     10669508.79
#Sta/Elev= 30
  4578.7  282.54  4586.1  282.27  4600.3   282.7    4607  281.98  4621.2  281.53
  4656.7  281.25  4663.9  280.77  4678.1  280.89  4692.3  279.95  4706.5   279.8
  4720.7  280.36  4749.2  280.23  4755.9  278.63  4763.4   279.3  4774.1  276.52
  4776.8  276.02  4780.1  276.52  4869.6  276.52  4876.3  277.74  4883.8  276.52
  4959.2  276.52  5053.5  276.52  5060.2  277.31    5082  278.04  5131.3  278.29
  5216.6  280.66  5251.7  282.35  5272.6   282.6  5294.4  284.35  5310.4  284.72
#Mann= 3 ,-1 , 0
  4578.7     .03       0  4774.1     .03       0  4959.2     .03       0
Bank Sta=4663.9,5216.6
XS Rating Curve= 0 ,0
Exp/Cntr=0.3,0.1

Type RM Length L Ch R = 1 ,25218   ,305,305,305
BEGIN DESCRIPTION:
Mapping XS 3997fe6c
END DESCRIPTION:
XS GIS Cut Line= 2
      3653635.29     10668846.89      3653181.75      10669411.1
#Sta/Elev= 30
  4616.6  283.15  4622.5  282.38  4665.7  282.26  4708.8  280.63  4715.3  281.29
  4764.9  281.17  4779.3  280.59  4793.7  277.38  4859.6   277.4  4886.4  278.33
  4892.9  281.31  4907.3   281.6  4915.2   278.6  4921.6  277.32  4950.4  277.98
  4956.9  277.25  4971.3  278.06  4985.6  277.39  5060.2   277.2  5075.4  277.14
  5078.2  276.64  5081.4  277.14    5128   278.9  5134.5  281.11  5148.8  280.68
  5156.8  279.34  5171.2  279.06  5276.8  281.96  5291.2  283.27  5340.5   284.9
#Mann= 5 ,-1 , 0
  4616.6     .05       0  4859.6     .07       0  5060.2     .05       0
  5075.4     .07       0  5081.4     .05       0
Bank Sta=4764.9,4892.9
XS Rating Curve= 0 ,0
Exp/Cntr=0.3,0.1

Type RM Length L Ch R = 1 ,24913   ,304,304,304
BEGIN DESCRIPTION:
Mapping XS 12d1014f
END DESCRIPTION:
XS GIS Cut Line= 2
      3653562.87     10668683.42      3652863.45     10669122.83
#Sta/Elev= 30
  4577.3  285.06  4605.1  284.07  4620.4  284.59  4693.4  281.85  4714.6   282.1
  4751.1  280.52  4881.8  277.26  4944.2  277.15    4947  276.65  4950.2  277.15
  5033.8  277.25  5049.1   278.1  5091.5  278.27  5106.8  280.97  5112.7  282.79
    5128  281.27  5136.2  282.83  5143.3  282.67  5149.2  281.46  5158.6  282.56
  5164.5  281.32  5171.6  281.39  5179.8  283.41  5185.8  279.33  5195.2  280.35
  5201.1  278.29  5207.1  280.06  5216.4  279.52  5289.4  281.42  5403.3  285.26
#Mann= 3 ,-1 , 0
  4577.3     .05       0  4944.2     .03       0  4950.2     .05       0
Bank Sta=4751.1,5106.8
XS Rating Curve= 0 ,0
Exp/Cntr=0.3,0.1

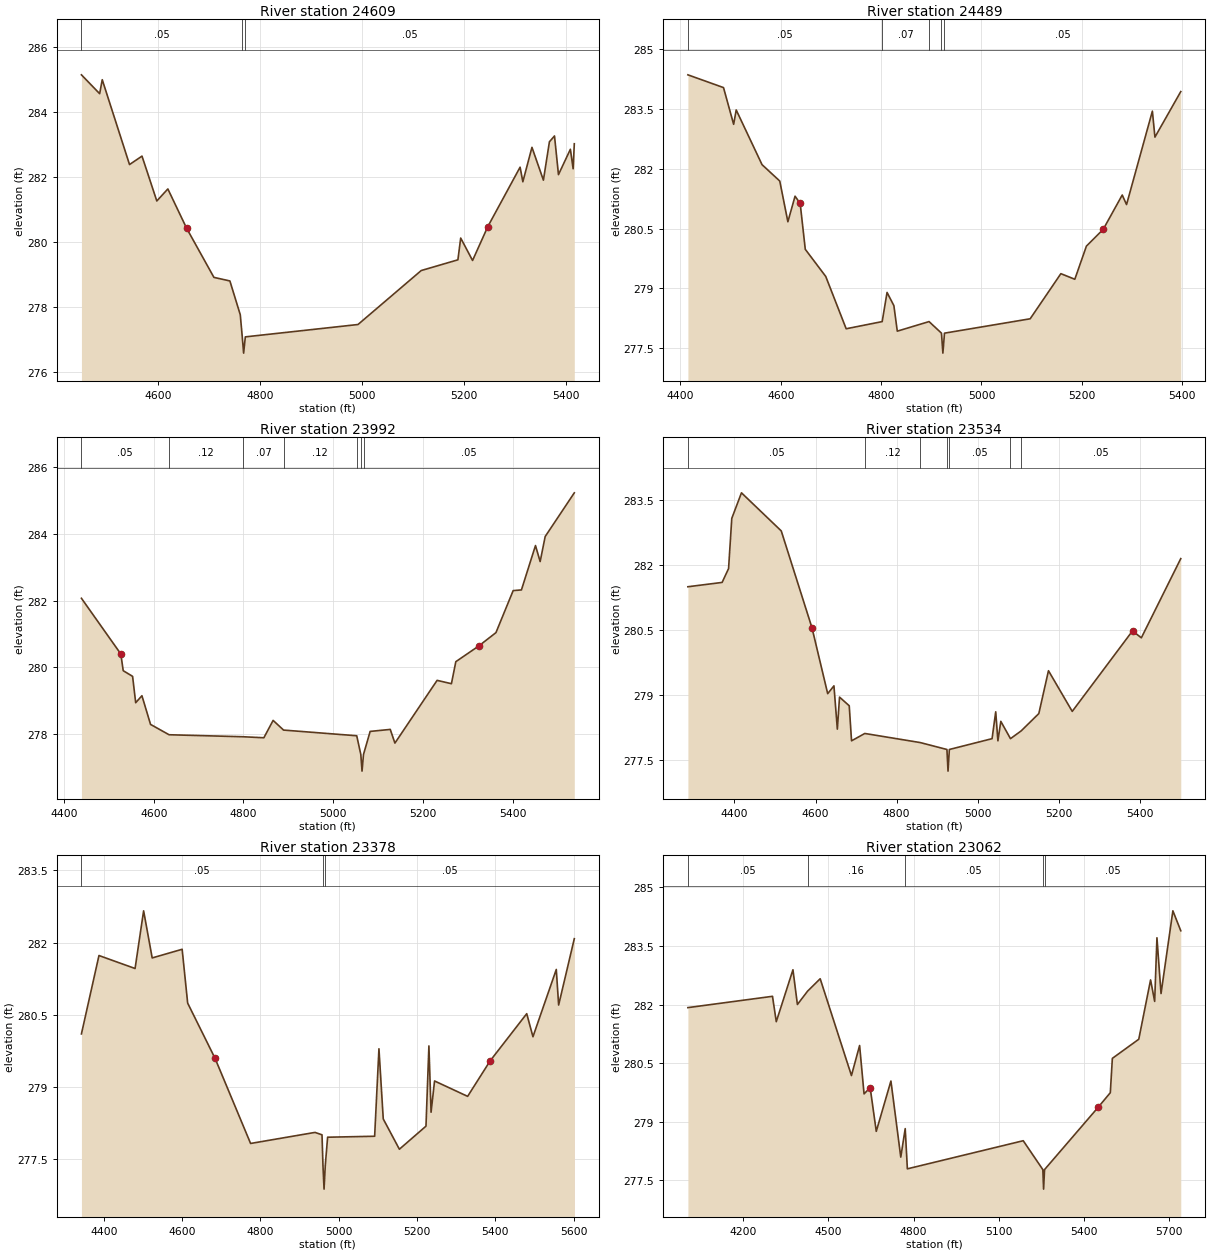
Type RM Length L Ch R = 1 ,24609   ,120,120,120
BEGIN DESCRIPTION:
Mapping XS 3f24fb4a
END DESCRIPTION:
XS GIS Cut Line= 3
      3653576.71     10668558.26       3652914.8     10668677.63
      3652644.04     10668796.76
#Sta/Elev= 30
  4448.8  285.13  4484.6  284.55  4489.7  284.98  4543.3  282.37  4567.8  282.63
  4596.9  281.25  4618.6  281.62  4655.5  280.41  4709.1   278.9  4740.5  278.79
  4760.9  277.75  4764.8  277.07  4767.5  276.57  4770.8  277.07  4992.2  277.45
  5116.4  279.11  5188.5  279.44    5194  280.11  5217.3  279.42  5247.2  280.46
  5310.7  282.29  5316.1  281.84    5334   282.9  5356.5  281.89  5368.3  283.07
  5378.3  283.25  5386.1  282.06  5409.5  282.84  5414.9  282.24  5417.2  283.01
#Mann= 3 ,-1 , 0
  4448.8     .05       0  4764.8     .03       0  4770.8     .05       0
Bank Sta=4655.5,5247.2
XS Rating Curve= 0 ,0
Exp/Cntr=0.3,0.1

Type RM Length L Ch R = 1 ,24489   ,497,497,497
BEGIN DESCRIPTION:
Mapping XS 271582ea
END DESCRIPTION:
XS GIS Cut Line= 2
      3653559.28     10668436.75      3652595.03     10668625.27
#Sta/Elev= 30
  4414.8  284.35  4485.8  284.03    4506  283.11  4511.1  283.47  4562.6   282.1
  4597.9  281.69  4614.1  280.67  4628.4  281.31  4638.6  281.13  4648.8  279.98
  4689.6   279.3  4730.3  277.99  4802.1  278.17  4811.8   278.9  4825.4  278.57
  4832.2  277.93  4895.5  278.17  4920.3  277.88  4923.1  277.38  4926.3  277.88
  5097.1  278.24  5158.3  279.37  5186.1  279.23  5209.2  280.06  5242.7  280.48
  5280.6  281.34  5289.2   281.1  5340.7  283.44  5345.8  282.79  5397.3  283.93
#Mann= 5 ,-1 , 0
  4414.8     .05       0  4802.1     .07       0  4895.5     .05       0
  4920.3     .03       0  4926.3     .05       0
Bank Sta=4638.6,5242.7
XS Rating Curve= 0 ,0
Exp/Cntr=0.3,0.1

Type RM Length L Ch R = 1 ,23992   ,458,458,458
BEGIN DESCRIPTION:
UNT 0419 IN LACR 26.0
END DESCRIPTION:
XS GIS Cut Line= 2
      3653398.77     10667909.99      3652346.74     10668225.07
#Sta/Elev= 30
    4439  282.07  4526.8   280.4  4532.1   279.9    4553  279.73  4559.9  278.94
  4573.8  279.15    4593  278.29  4634.3  277.98  4799.4  277.92  4845.5  277.89
  4866.1  278.41  4889.4  278.12  5052.4  277.95  5061.5  277.39  5064.2  276.89
  5067.5  277.39  5082.3  278.08  5127.1  278.14  5137.5  277.73  5231.5  279.61
  5263.4  279.51  5273.2  280.17  5324.3  280.64  5362.6  281.04    5401   282.3
  5419.4  282.32  5450.7  283.65  5461.1  283.17  5472.3  283.92  5537.2  285.23
#Mann= 7 ,-1 , 0
    4439     .05       0  4634.3     .12       0  4799.4     .07       0
  4889.4     .12       0  5052.4     .05       0  5061.5     .07       0
  5067.5     .05       0
Bank Sta=4526.8,5324.3
XS Rating Curve= 0 ,0
Exp/Cntr=0.3,0.1

Type RM Length L Ch R = 1 ,23534   ,156,156,156
BEGIN DESCRIPTION:
Mapping XS def2efd9
END DESCRIPTION:
XS GIS Cut Line= 2
       3653422.2      10667352.7      3652299.85     10667818.83
#Sta/Elev= 30
  4285.3   281.5  4369.7   281.6  4385.6  281.92  4393.5  283.08  4417.4  283.67
  4515.5  282.79  4591.3  280.55    4630  279.03  4645.4  279.21  4653.8  278.21
  4659.2  278.95  4683.1  278.75  4688.8  277.94  4721.5  278.11  4858.1   277.9
    4924  277.74  4926.7  277.24    4930  277.74  5035.3  277.99  5044.3  278.61
  5049.7  277.94  5056.9  278.39  5080.7  277.99  5107.1  278.17  5150.6  278.57
  5174.4  279.56    5233  278.62  5381.6  280.48  5403.4  280.32  5500.6  282.15
#Mann= 7 ,-1 , 0
  4285.3     .05       0  4721.5     .12       0  4858.1     .05       0
    4924     .03       0    4930     .05       0  5080.7     .12       0
  5107.1     .05       0
Bank Sta=4591.3,5381.6
XS Rating Curve= 0 ,0
Exp/Cntr=0.3,0.1

Type RM Length L Ch R = 1 ,23378   ,316,316,316
BEGIN DESCRIPTION:
Mapping XS 9582eb2f
END DESCRIPTION:
XS GIS Cut Line= 2
      3653364.99     10667206.84      3652212.96     10667713.94
#Sta/Elev= 30
  4342.9   280.1  4387.7  281.73  4479.9  281.46  4501.7  282.66  4523.6  281.68
  4600.1  281.86  4614.2  280.74  4684.2  279.59  4774.9  277.82  4939.4  278.05
  4957.3     278  4959.7  277.37  4962.5  276.87  4965.7  277.37  4971.6  277.95
  5091.7  277.97  5102.7  279.79  5113.7  278.33  5154.9   277.7  5222.8  278.18
  5230.3  279.85  5235.8  278.47  5244.7  279.12  5329.2   278.8  5386.8  279.54
  5480.1  280.52    5496  280.04  5555.6  281.44  5561.6   280.7  5601.6  282.08
#Mann= 3 ,-1 , 0
  4342.9     .05       0  4959.7     .03       0  4965.7     .05       0
Bank Sta=4684.2,5386.8
XS Rating Curve= 0 ,0
Exp/Cntr=0.3,0.1

Type RM Length L Ch R = 1 ,23062   ,486,486,486
BEGIN DESCRIPTION:
UNT 0419 IN LACR 24.0
END DESCRIPTION:
XS GIS Cut Line= 3
      3653436.79      10666730.2      3652441.52     10667311.92
      3651985.46     10667674.61
#Sta/Elev= 30
  4005.5  281.92  4303.4  282.21  4316.7  281.56  4375.4  282.89  4391.1     282
  4426.7  282.34  4471.3  282.66  4581.4  280.18  4610.1  280.95  4625.8  279.71
  4647.3  279.87  4668.8  278.75  4720.4  280.04  4755.1  278.09  4770.7  278.82
  4778.3  277.79  5186.3  278.51  5255.3  277.77    5258  277.27  5261.3  277.77
  5450.5  279.37  5492.9  279.74  5500.1  280.62  5593.1  281.11  5634.7  282.63
  5649.1  282.08  5657.1  283.71  5671.5  282.28  5713.2   284.4    5741  283.89
#Mann= 5 ,-1 , 0
  4005.5     .05       0  4426.7     .16       0  4770.7     .05       0
  5255.3     .03       0  5261.3     .05       0
Bank Sta=4647.3,5450.5
XS Rating Curve= 0 ,0
Exp/Cntr=0.3,0.1

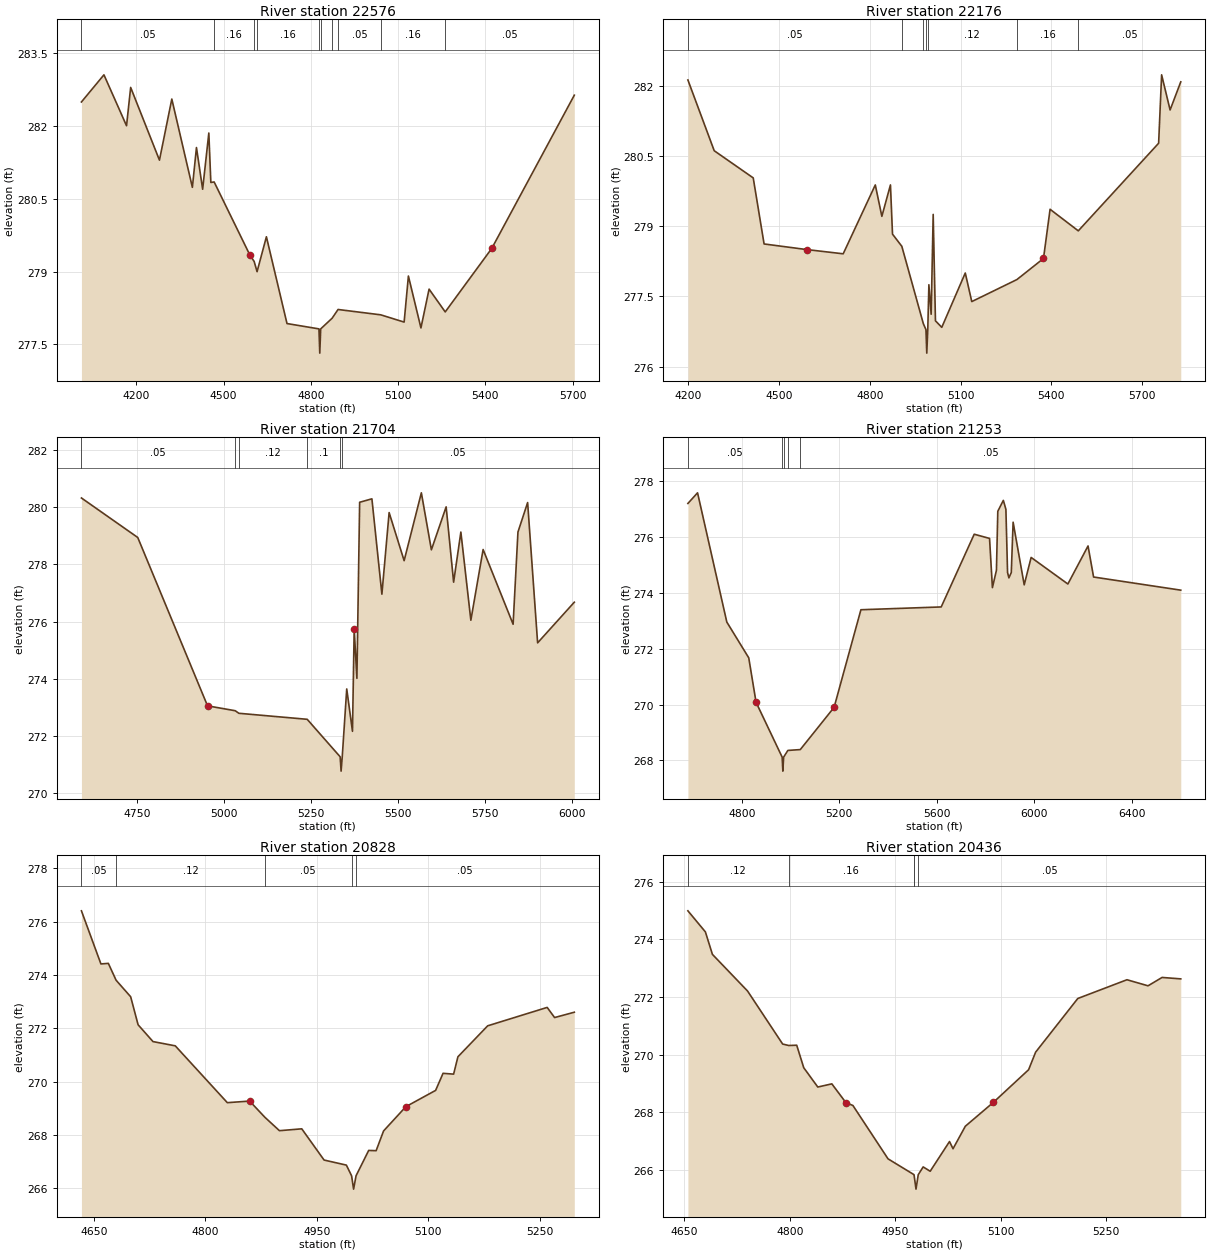
Type RM Length L Ch R = 1 ,22576   ,400,400,400
BEGIN DESCRIPTION:
UNT 0419 IN LACR 23.0
END DESCRIPTION:
XS GIS Cut Line= 3
      3652936.81     10666257.97      3652153.01     10667020.28
      3651798.95     10667506.57
#Sta/Elev= 30
  4010.9   282.5  4088.3  283.06    4166  282.01  4180.2   282.8  4279.2   281.3
  4321.7  282.56  4392.4  280.74  4406.5  281.56  4427.7   280.7    4449  281.86
  4455.9  280.84  4467.3  280.85  4590.4  279.34  4604.9  279.21  4614.9     279
    4647  279.72  4717.8  277.93  4827.7  277.82  4830.5  277.32  4833.7  277.82
    4873  278.04  4893.4  278.22  5040.1  278.11  5120.6  277.96  5135.3  278.91
  5178.4  277.84  5206.4  278.64  5261.9  278.17    5422  279.48  5705.8  282.64
#Mann= 10 ,-1 , 0
  4010.9     .05       0  4467.3     .16       0  4604.9     .05       0
  4614.9     .16       0  4827.7     .03       0  4833.7     .16       0
    4873     .12       0  4893.4     .05       0  5040.1     .16       0
  5261.9     .05       0
Bank Sta=4590.4,5422
XS Rating Curve= 0 ,0
Exp/Cntr=0.3,0.1

Type RM Length L Ch R = 1 ,22176   ,472,472,472
BEGIN DESCRIPTION:
UNT 0419 IN LACR 22.0
END DESCRIPTION:
XS GIS Cut Line= 3
      3652485.41     10666070.48      3651867.91     10666756.66
      3651527.32     10667375.62
#Sta/Elev= 30
  4198.5  282.12  4285.5  280.61  4414.5  280.03  4450.4  278.62  4591.7   278.5
    4712  278.41  4818.1  279.88  4839.8  279.21  4868.2  279.88    4875  278.83
  4905.8  278.57  4976.9  276.92  4985.6  276.79  4988.3  276.29  4991.6  276.79
  4995.3  277.75  5002.8  277.12  5009.5  279.25    5017  276.98  5037.9  276.84
  5115.6     278  5137.1  277.39  5286.3  277.86  5374.2  278.31    5396  279.36
  5489.3   278.9  5754.9  280.77  5764.8  282.23  5792.8  281.48  5828.1  282.08
#Mann= 7 ,-1 , 0
  4198.5     .05       0  4905.8     .16       0  4976.9     .12       0
  4985.6     .07       0  4991.6     .12       0  5286.3     .16       0
  5489.3     .05       0
Bank Sta=4591.7,5374.2
XS Rating Curve= 0 ,0
Exp/Cntr=0.3,0.1

Type RM Length L Ch R = 1 ,21704   ,451,451,451
BEGIN DESCRIPTION:
UNT 0419 IN LACR 21.0
END DESCRIPTION:
XS GIS Cut Line= 3
      3652020.36     10666131.32      3651325.89     10666495.91
      3650927.09     10666985.75
#Sta/Elev= 30
  4590.6  280.32  4752.4  278.94  4952.9  273.06  5032.3  272.89  5042.9   272.8
  5239.2  272.59  5333.9  271.28  5336.6  270.78  5339.9  271.28  5352.8  273.65
  5369.3  272.17  5374.2  275.74    5382  274.02  5389.9  280.17  5425.1  280.29
  5453.8  276.96  5474.6  279.81  5517.7  278.13  5567.2   280.5    5596  278.51
  5638.4  280.01  5659.9  277.38  5680.7  279.13  5709.4  276.05  5744.6  278.52
  5830.8  275.91  5844.7  279.13  5872.5  280.16  5901.2  275.26  6006.6  276.68
#Mann= 6 ,-1 , 0
  4590.6     .05       0  5032.3     .16       0  5042.9     .12       0
  5239.2      .1       0  5333.9     .03       0  5339.9     .05       0
Bank Sta=4952.9,5374.2
XS Rating Curve= 0 ,0
Exp/Cntr=0.3,0.1

Type RM Length L Ch R = 1 ,21253   ,425,425,425
BEGIN DESCRIPTION:
UNT 0419 IN LACR 20.0
END DESCRIPTION:
XS GIS Cut Line= 3
       3651929.2     10665936.02      3650987.35     10665927.34
      3650010.79     10666387.41
#Sta/Elev= 30
  4579.1  277.19  4618.7  277.57  4738.7  272.95  4828.7  271.67  4858.7  270.08
  4965.7  268.12  4968.5  267.62  4971.7  268.12  4989.1  268.36    5040  268.39
  5178.7   269.9  5288.7  273.39    5618  273.49  5753.4  276.09  5816.2  275.94
    5828  274.18  5844.5   274.8  5850.1  276.91  5872.8   277.3  5883.3  276.98
  5890.1  274.72  5895.6  274.53  5905.4  274.72  5912.9  276.52  5958.4  274.28
  5986.8  275.26  6137.5  274.31  6220.2  275.67  6242.9  274.56  6600.5  274.09
#Mann= 5 ,-1 , 0
  4579.1     .05       0  4965.7     .07       0  4971.7     .05       0
  4989.1     .16       0    5040     .05       0
Bank Sta=4858.7,5178.7
XS Rating Curve= 0 ,0
Exp/Cntr=0.3,0.1

Type RM Length L Ch R = 1 ,20828   ,392,392,392
BEGIN DESCRIPTION:
UNT 0419 IN LACR 19.0
END DESCRIPTION:
XS GIS Cut Line= 2
      3651885.81     10665545.39      3651223.14     10665558.39
#Sta/Elev= 30
  4633.5   276.4  4659.7  274.41  4669.7  274.43  4680.1   273.8  4699.7  273.18
  4709.7  272.13  4729.7   271.5  4759.7  271.34  4829.7  269.21  4859.7  269.27
  4880.3  268.66  4899.8  268.16  4929.8  268.23  4959.8  267.06  4989.8  266.87
  4996.8  266.47  4999.5  265.97  5002.8  266.47  5019.8  267.42  5029.8  267.41
  5039.8  268.15  5069.8  269.06  5109.8  269.67  5119.8  270.31    5134  270.28
  5139.8  270.93  5179.8  272.09  5259.8  272.78  5269.8   272.4  5296.3   272.6
#Mann= 5 ,-1 , 0
  4633.5     .05       0  4680.1     .12       0  4880.3     .05       0
  4996.8     .03       0  5002.8     .05       0
Bank Sta=4859.7,5069.8
XS Rating Curve= 0 ,0
Exp/Cntr=0.3,0.1

Type RM Length L Ch R = 1 ,20436   ,294,294,294
BEGIN DESCRIPTION:
UNT 0419 IN LACR 18.0
END DESCRIPTION:
XS GIS Cut Line= 2
      3651894.48     10665172.13        3651193.     10665159.14
#Sta/Elev= 30
    4655  274.99  4679.9  274.26  4689.9  273.48  4739.9  272.21  4789.9  270.37
  4798.6  270.32  4809.9  270.33  4819.9  269.55  4839.9  268.88  4859.9  268.99
  4879.9  268.34  4889.9  268.24  4939.9  266.39  4976.3  265.85  4976.9  265.84
  4979.7  265.34  4982.9  265.84  4989.9  266.11  4999.9  265.96  5027.4  266.99
  5032.4  266.74  5049.9  267.52  5089.9  268.35    5140  269.48    5150  270.09
    5210  271.95    5280   272.6    5310  272.39    5330  272.68  5356.6  272.63
#Mann= 5 ,-1 , 0
    4655     .12       0  4798.6     .16       0  4976.3     .05       0
  4976.9     .03       0  4982.9     .05       0
Bank Sta=4879.9,5089.9
XS Rating Curve= 0 ,0
Exp/Cntr=0.3,0.1

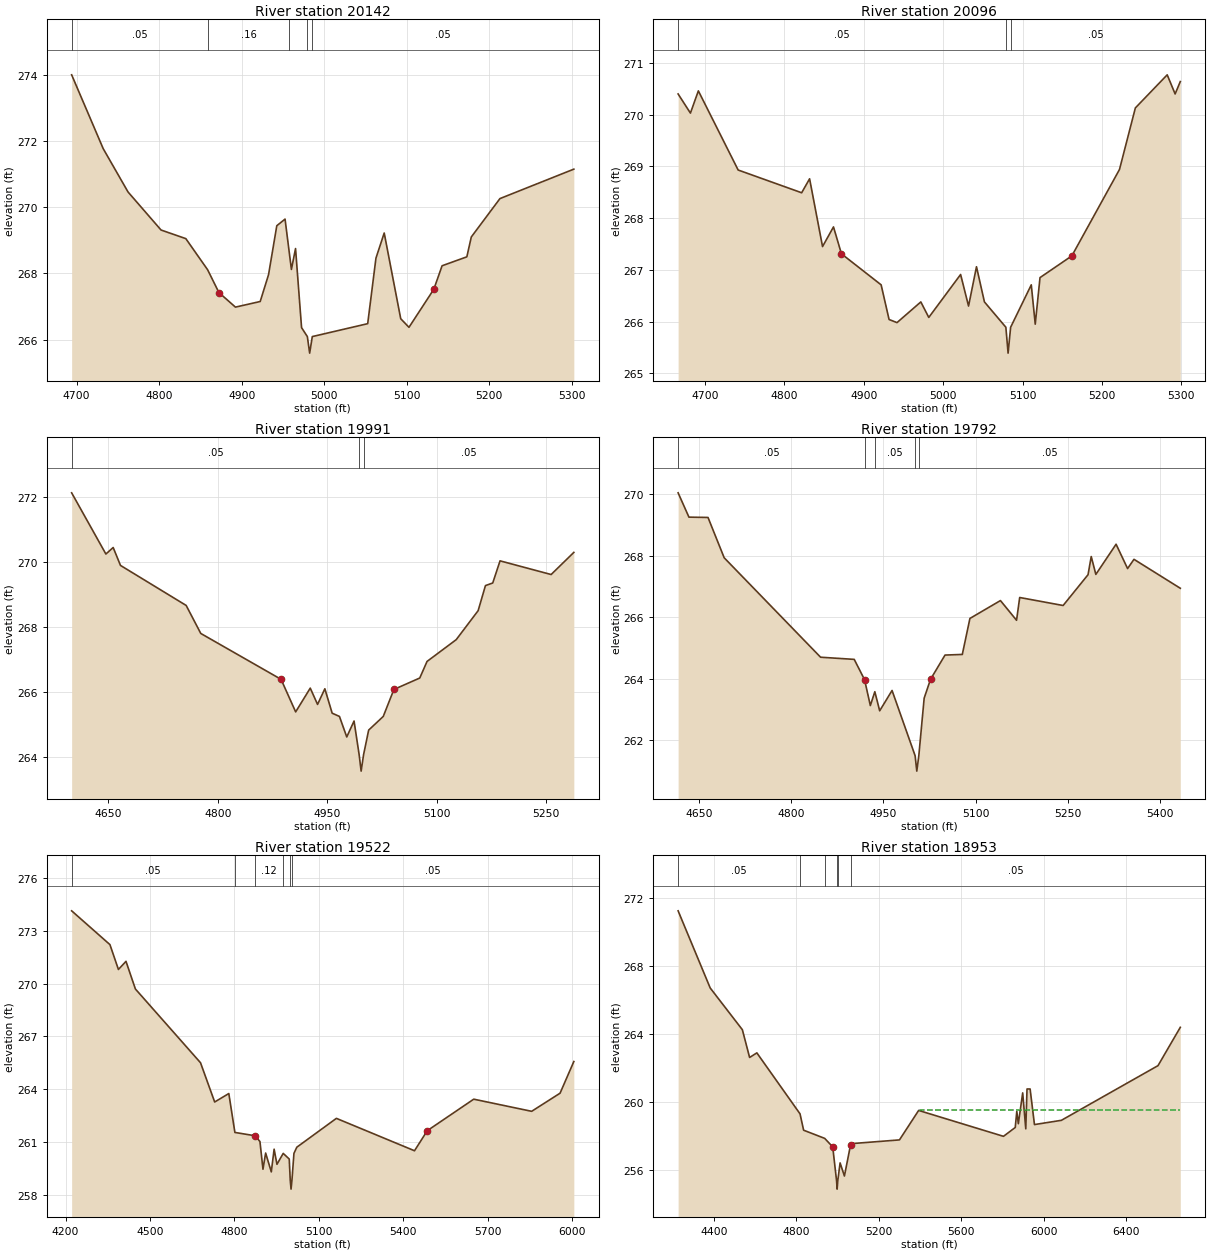
Type RM Length L Ch R = 1 ,20142   ,46,46,46
BEGIN DESCRIPTION:
Mapping XS be11d1ce
END DESCRIPTION:
XS GIS Cut Line= 2
      3651847.81     10664887.66      3651240.16     10664859.45
#Sta/Elev= 30
  4694.1     274  4732.3  271.77  4762.4  270.46  4802.4  269.31  4832.4  269.05
  4858.8  268.11  4872.5  267.42  4892.5  266.98  4922.5  267.15  4932.6  267.96
  4942.6  269.44  4952.6  269.64  4957.7  268.63  4960.3  268.12  4965.3  268.75
  4972.6  266.36  4979.6  266.09  4982.4  265.59  4985.6  266.09  5052.7  266.48
  5062.7  268.46  5072.7  269.22  5092.7  266.63  5102.7  266.37  5132.8  267.52
  5142.8  268.23  5172.8   268.5  5178.2   269.1  5212.9  270.26  5302.4  271.15
#Mann= 5 ,-1 , 0
  4694.1     .05       0  4858.8     .16       0  4957.7     .05       0
  4979.6     .03       0  4985.6     .05       0
Bank Sta=4872.5,5132.8
XS Rating Curve= 0 ,0
Exp/Cntr=0.3,0.1

Type RM Length L Ch R = 1 ,20096   ,105,105,105
BEGIN DESCRIPTION:
Mapping XS 9f4327c1
END DESCRIPTION:
XS GIS Cut Line= 2
      3651865.12     10664842.09      3651233.07     10664818.27
#Sta/Elev= 30
  4666.1   270.4  4681.6  270.03  4691.6  270.46  4741.7  268.93  4821.7  268.49
  4831.7  268.76    4848  267.45  4861.8  267.83  4871.8  267.31  4921.8  266.71
  4931.8  266.04  4941.8  265.98  4971.8  266.38  4981.8  266.08  5021.9  266.91
  5031.9   266.3  5041.9  267.06  5051.9  266.38  5078.9  265.89  5081.7  265.39
  5084.9  265.89  5110.9  266.71  5115.9  265.95  5121.9  266.85    5162  267.27
    5222  268.94    5242  270.13  5282.1  270.77  5292.1   270.4  5298.6  270.64
#Mann= 3 ,-1 , 0
  4666.1     .05       0  5078.9     .04       0  5084.9     .05       0
Bank Sta=4871.8,5162
XS Rating Curve= 0 ,0
Exp/Cntr=0.3,0.1

Type RM Length L Ch R = 1 ,19991   ,199,199,199
BEGIN DESCRIPTION:
Mapping XS e41bb2d3
END DESCRIPTION:
XS GIS Cut Line= 2
      3651856.48     10664759.62      3651168.53      10664768.3
#Sta/Elev= 30
  4599.9  272.13  4646.8  270.25  4656.8  270.45  4666.8   269.9  4756.8  268.67
  4776.8  267.81  4886.8   266.4  4906.8   265.4  4926.8  266.13  4936.8  265.63
  4946.8  266.11  4956.8  265.36  4966.8  265.26  4976.8  264.63  4986.8  265.12
  4993.8  264.08  4996.5  263.58  4999.8  264.08  5006.8  264.84  5026.8  265.26
  5041.4  266.09  5076.8  266.44  5086.8  266.95  5126.8  267.62  5156.8  268.51
  5166.8  269.28  5176.8  269.36  5186.8  270.04  5256.8  269.62  5287.9   270.3
#Mann= 3 ,-1 , 0
  4599.9     .05       0  4993.8     .03       0  4999.8     .05       0
Bank Sta=4886.8,5041.4
XS Rating Curve= 0 ,0
Exp/Cntr=0.3,0.1

Type RM Length L Ch R = 1 ,19792   ,270,270,270
BEGIN DESCRIPTION:
UNT 0419 IN LACR 17.0
END DESCRIPTION:
XS GIS Cut Line= 2
      3651756.66     10664486.19      3650966.72     10664692.35
#Sta/Elev= 30
  4616.5  270.04  4634.1  269.25  4665.1  269.24  4691.4  267.93  4848.1   264.7
  4902.8  264.63  4919.6  263.97    4929  263.13  4936.3  263.58  4944.2  262.96
  4964.3  263.62  5001.8   261.5  5004.5     261  5007.8   261.5  5016.5  263.37
  5026.8  263.98  5050.4  264.77  5078.5  264.79  5090.9  265.96  5140.5  266.54
  5166.7   265.9  5171.8  266.64  5242.4  266.38  5282.9  267.38  5288.1  267.97
  5295.6  267.39  5328.5  268.37  5347.2  267.58  5357.6  267.88  5432.9  266.94
#Mann= 5 ,-1 , 0
  4616.5     .05       0  4919.6     .16       0  4936.3     .05       0
  5001.8     .03       0  5007.8     .05       0
Bank Sta=4919.6,5026.8
XS Rating Curve= 0 ,0
Exp/Cntr=0.3,0.1

Type RM Length L Ch R = 1 ,19522   ,569,569,569
BEGIN DESCRIPTION:
UNT 0419 IN LACR 16.0
END DESCRIPTION:
XS GIS Cut Line= 3
      3652054.82     10664445.46      3651101.15     10664345.65
      3650395.11     10664771.88
#Sta/Elev= 30
  4221.7  274.13  4357.7  272.21  4387.8   270.8  4414.7  271.26  4448.1  269.69
  4679.4   265.5  4729.7  263.27  4779.9  263.75  4801.5  261.54    4874  261.35
  4890.5  261.02  4901.2  259.45  4910.7  260.37  4930.8   259.3  4940.8  260.59
  4950.9  259.73  4973.1  260.35  4994.5  260.03  4998.1  258.82  5000.9  258.32
  5004.1  258.82  5011.2  260.35  5021.3   260.7    5162  262.34  5439.4   260.5
  5484.8  261.64  5649.8  263.43  5855.5  262.74  5956.4  263.77  6005.3  265.57
#Mann= 6 ,-1 , 0
  4221.7     .05       0  4801.5     .16       0    4874     .12       0
  4973.1     .05       0  4998.1     .03       0  5004.1     .05       0
Bank Sta=4874,5484.8
XS Rating Curve= 0 ,0
Exp/Cntr=0.3,0.1

Type RM Length L Ch R = 1 ,18953   ,424,424,424
BEGIN DESCRIPTION:
UNT 0419 IN LACR 15.0
END DESCRIPTION:
XS GIS Cut Line= 3
      3651949.62      10664360.2      3651349.61     10663810.19
      3649999.58     10664710.21
#Sta/Elev= 30
  4226.9  271.22  4382.6  266.69  4538.6  264.24  4573.8  262.61  4608.9  262.88
  4818.4   259.3  4835.8  258.34    4938  257.86    4977  257.36  4995.6  255.38
  4998.4  254.88  5001.6  255.38  5012.8  256.42  5033.8  255.65  5063.4  257.47
  5066.1  257.55  5300.8  257.77  5393.9   259.5  5805.5  257.98  5862.6   258.5
  5870.1  259.45  5877.6  258.72  5898.7  260.53  5913.7  258.42  5919.7  260.76
  5934.7  260.76  5955.8  258.67  6086.5  258.92  6555.2  262.13  6663.4  264.38
#Mann= 6 ,-1 , 0
  4226.9     .05       0  4818.4     .16       0    4938     .12       0
  4995.6     .07       0  5001.6     .12       0  5066.1     .05       0
#XS Ineff= 2 , 0
                         5399.43          259.54
Permanent Ineff=
       F       F
Bank Sta=4977,5063.4
XS Rating Curve= 0 ,0
Exp/Cntr=0.3,0.1

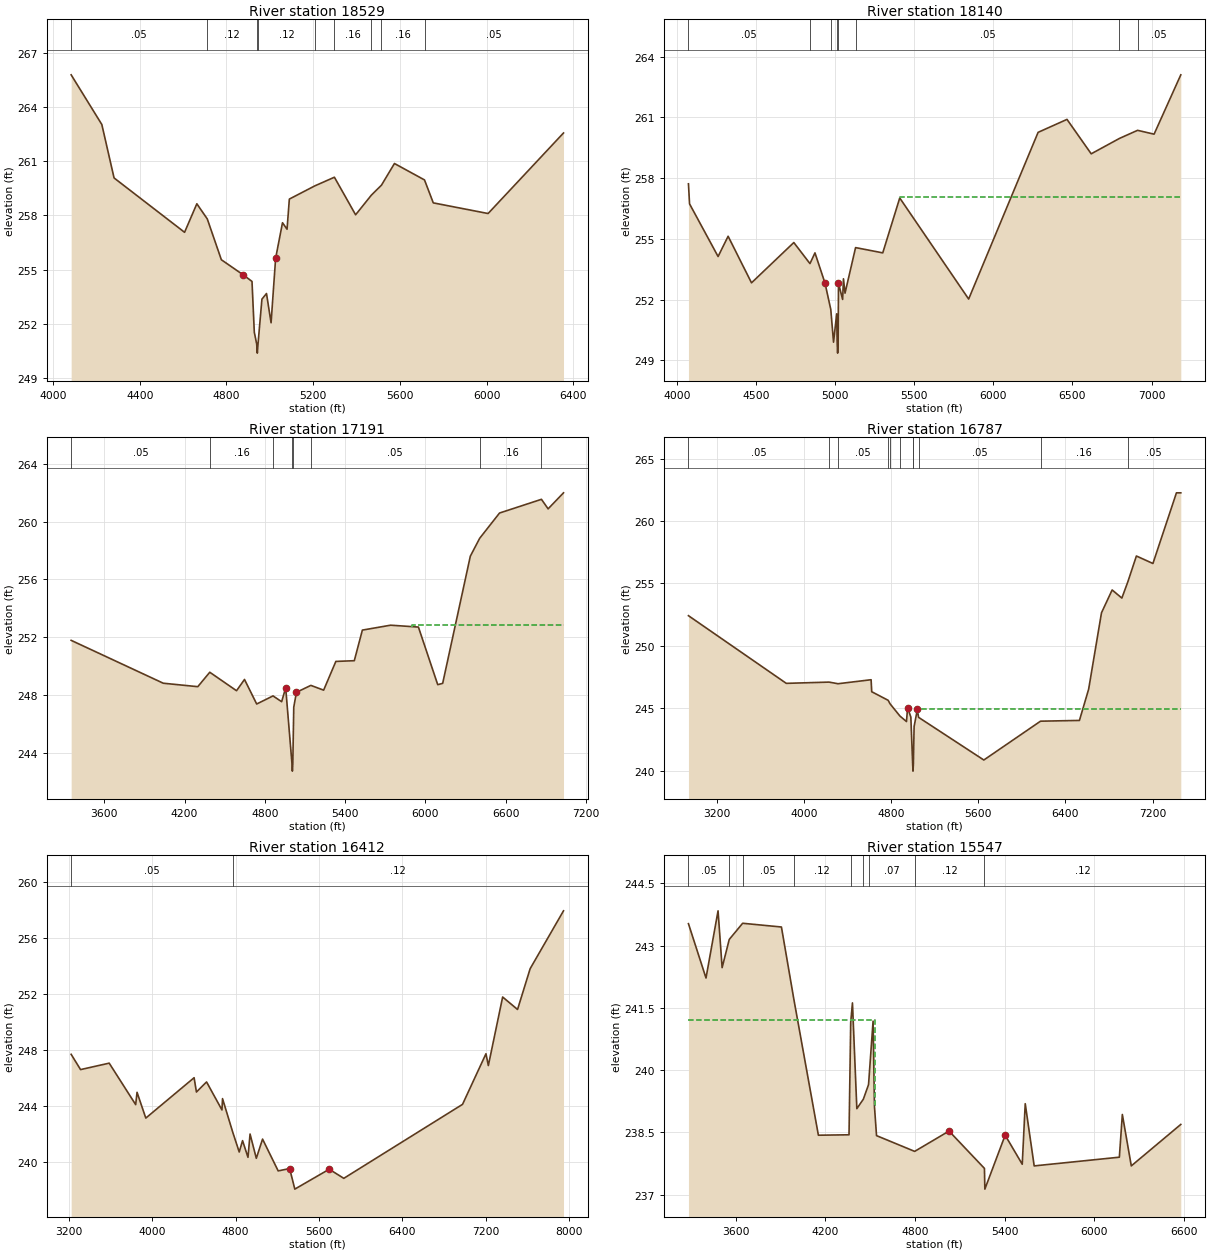
Type RM Length L Ch R = 1 ,18529   ,389,389,389
BEGIN DESCRIPTION:
UNT 0419 IN LACR 14.0
END DESCRIPTION:
XS GIS Cut Line= 3
      3652049.64     10664060.22      3651449.61     10663460.19
       3650099.6     10663910.19
#Sta/Elev= 30
  4083.3  265.78  4224.8  263.03  4281.3  260.07  4606.6  257.06  4663.2  258.64
  4711.4   257.8  4776.3  255.54  4875.3  254.72  4917.7  254.34  4928.3  251.53
  4939.4  250.87  4942.2  250.37  4945.4  250.87  4963.5  253.36  4984.6  253.67
  5005.7  252.05  5026.7  255.62  5058.4  257.59  5079.4  257.23    5090   258.9
  5207.4  259.63  5297.9  260.11  5395.7  258.03  5468.6  259.12    5515  259.67
  5574.9  260.87  5713.6  259.96  5754.1  258.69    6007   258.1  6354.9  262.56
#Mann= 9 ,-1 , 0
  4083.3     .05       0  4711.4     .12       0  4939.4     .07       0
  4945.4     .12       0  5207.4     .05       0  5297.9     .16       0
  5468.6     .05       0    5515     .16       0  5713.6     .05       0
Bank Sta=4875.3,5026.7
XS Rating Curve= 0 ,0
Exp/Cntr=0.3,0.1

Type RM Length L Ch R = 1 ,18140   ,949,949,949
BEGIN DESCRIPTION:
Mapping XS d3ce3444
END DESCRIPTION:
XS GIS Cut Line= 3
       3652527.1      10663528.8      3651402.09     10663146.85
      3649513.92     10663521.71
#Sta/Elev= 30
    4072  257.72  4078.9  256.73  4259.4  254.13  4322.8  255.13  4470.7  252.83
  4738.2  254.82  4840.3  253.78    4872  254.31  4935.3  252.82  4971.9  251.52
  4989.4   249.9  5009.2   251.3  5012.5  249.86  5015.2  249.36  5018.5  249.86
  5020.7  252.81  5046.9  252.01  5052.1  253.03    5062  252.32  5128.7  254.57
  5300.6  254.31    5408  257.02  5843.7  252.03  6282.9  260.26  6465.6   260.9
  6618.6   259.2  6797.2  259.96  6911.8  260.36  7016.2  260.17  7185.1   263.1
#Mann= 8 ,-1 , 0
    4072     .05       0  4840.3     .16       0  4971.9     .12       0
  5012.5     .07       0  5018.5     .12       0  5128.7     .05       0
  6797.2     .16       0  6911.8     .05       0
#XS Ineff= 2 , 0
                         5409.94          257.05
Permanent Ineff=
       F       F
Bank Sta=4935.3,5020.7
XS Rating Curve= 0 ,0
Exp/Cntr=0.3,0.1

Type RM Length L Ch R = 1 ,17191   ,404,404,404
BEGIN DESCRIPTION:
UNT 0419 IN LACR 13.0
END DESCRIPTION:
XS GIS Cut Line= 4
      3652800.86     10663248.68      3651429.29     10662710.47
      3650318.18       10662832.      3649380.66     10663387.57
#Sta/Elev= 30
  3352.1  251.77  4040.8   248.8  4298.8  248.56  4388.5  249.56  4588.5  248.28
  4648.1  249.06  4739.2  247.36  4861.3  247.92  4925.8  247.52  4955.9  248.49
  5003.2  243.21    5006  242.71  5009.2  243.21  5016.3  247.14  5036.4  248.17
  5144.2  248.65  5239.7  248.32    5331  250.31    5469  250.36  5529.3  252.48
  5740.6  252.82  5948.4  252.69  6092.7   248.7  6129.7  248.79  6336.4   257.6
  6406.3  258.84  6554.7  260.59  6868.1  261.54    6918  260.88    7033  261.99
#Mann= 8 ,-1 , 0
  3352.1     .05       0  4388.5     .16       0  4861.3     .12       0
  5003.2     .07       0  5009.2     .12       0  5144.2     .05       0
  6406.3     .16       0  6868.1     .05       0
#XS Ineff= 2 , 0
                         5903.23          252.84
Permanent Ineff=
       F       F
Bank Sta=4955.9,5036.4
XS Rating Curve= 0 ,0
Exp/Cntr=0.3,0.1

Type RM Length L Ch R = 1 ,16787   ,375,375,375
BEGIN DESCRIPTION:
Mapping XS 58067ad4
END DESCRIPTION:
XS GIS Cut Line= 4
      3653034.02     10663216.29      3651256.26     10662355.19
      3649909.04     10662389.91      3648833.66     10662917.19
#Sta/Elev= 30
    2939  252.42  3837.3     247    4230   247.1  4312.4  246.97  4616.1  247.29
  4621.7  246.33  4773.1  245.64  4789.4  245.37    4881  244.38    4941  243.94
    4951  245.05    4981   244.3    4998  240.47  5000.8  239.97    5004  240.47
    5011  243.55    5041  244.91  5051.6  244.28  5651.2  240.86  6171.7  243.97
    6529  244.03  6613.5  246.53  6731.5  252.65  6829.4  254.48  6918.5  253.83
  6972.2   255.1  7052.1   257.2  7203.9   256.6  7419.7  262.26  7459.7  262.26
#Mann= 11 ,-1 , 0
    2939     .05       0    4230     .16       0  4312.4     .05       0
  4773.1     .12       0  4789.4     .05       0    4881     .07       0
    4998     .07       0    5004     .07       0  5051.6     .05       0
  6171.7     .16       0  6972.2     .05       0
#XS Ineff= 2 , 0
                         5047.73          244.95
Permanent Ineff=
       F       F
Bank Sta=4951,5041
XS Rating Curve= 0 ,0
Exp/Cntr=0.3,0.1

Type RM Length L Ch R = 1 ,16412   ,865,865,865
BEGIN DESCRIPTION:
Mapping XS 8cfd6a77
END DESCRIPTION:
XS GIS Cut Line= 4
      3652763.21     10662632.97      3651214.59     10662001.02
      3649457.65     10662014.91      3648278.62     10662555.88
#Sta/Elev= 30
  3221.4  247.71  3311.7  246.62  3586.6  247.08  3840.9  244.12  3853.9     245
  3938.1  243.16  4401.8  246.04  4424.1  245.02  4521.4  245.74  4669.2  243.74
  4674.6  244.55  4772.4  242.16    4835  240.74    4867  241.55    4919  240.36
    4939  242.02    4999  240.29    5059  241.66    5209  239.39    5319  239.56
  5368.7  238.09    5699  239.51    5839  238.86  6978.9  244.14  7203.8  247.75
  7226.8  246.91    7364   251.8    7507  250.91    7628  253.82  7948.2  257.95
#Mann= 2 ,-1 , 0
  3221.4     .05       0  4772.4     .12       0
Bank Sta=5319,5699
XS Rating Curve= 0 ,0
Exp/Cntr=0.3,0.1

Type RM Length L Ch R = 1 ,15547   ,0,0,0
BEGIN DESCRIPTION:
UNT 0419 IN LACR 12.0
END DESCRIPTION:
XS GIS Cut Line= 3
       3652103.4      10662215.5      3650974.42     10661569.96
      3648978.36     10661655.61
#Sta/Elev= 30
  3282.6  243.53  3400.2  242.22  3480.9  243.84  3508.2  242.47  3555.9  243.15
  3645.7  243.54  3905.5  243.45  3989.1   241.7  4153.1  238.43  4358.3  238.44
  4369.6  241.15  4381.3  241.62  4410.7  239.07  4454.4   239.3  4489.1  239.65
  4519.5  241.18  4528.8  239.12  4542.6  238.42  4798.1  238.04  5028.3  238.53
  5265.5  237.63  5268.3  237.13  5404.3  238.43  5518.8  237.73  5538.8  239.19
  5598.8  237.69  6169.4   237.9  6189.4  238.93  6249.4  237.69    6581  238.69
#Mann= 9 ,-1 , 0
  3282.6     .05       0  3555.9     .16       0  3645.7     .05       0
  3989.1     .12       0  4369.6     .07       0  4454.4     .12       0
  4489.1     .07       0  4798.1     .12       0  5265.5     .12       0
#XS Ineff= 2 , 0
         4529.27   241.2
Permanent Ineff=
       F       F
Bank Sta=5028.3,5404.3
XS Rating Curve= 0 ,0
Exp/Cntr=0.3,0.1

Chan Stop Cuts=-1
Use User Specified Reach Order=0
Composite Channel Slope=5