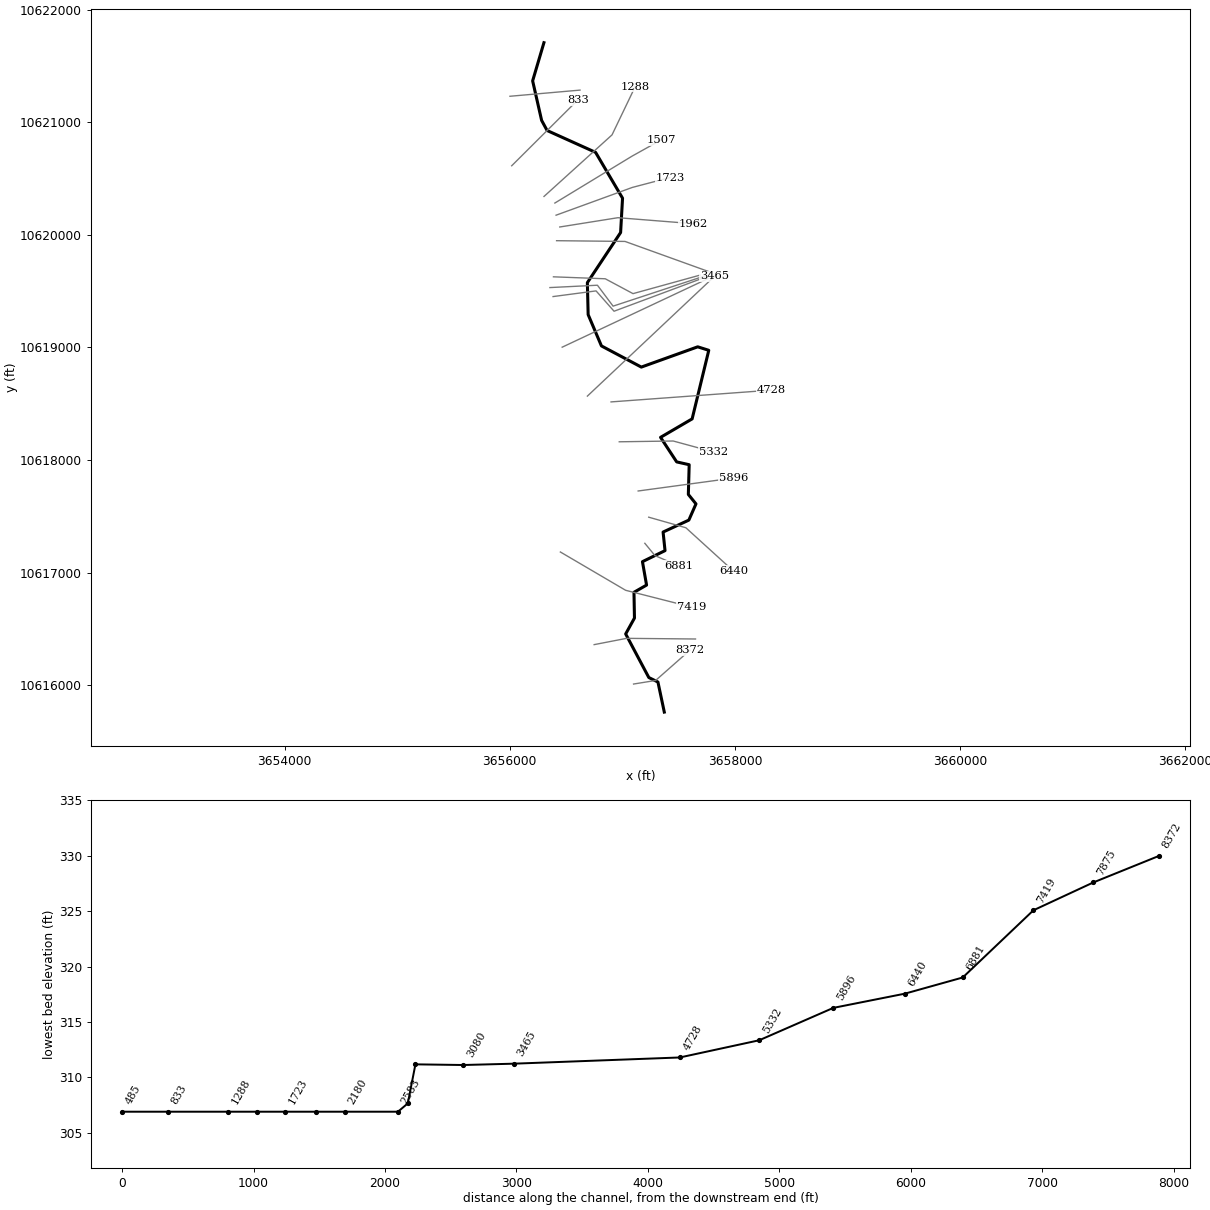
--- UNT 0423 IN LACR.prj (project) ---

Proj Title=UNT 0423 IN LACR Base Level Engineering
Current Plan=p01
Default Exp/Contr=0.3,0.1
English Units
Geom File=g01
Flow File=f01
Plan File=p01
BEGIN DESCRIPTION:
UNT 0423 IN LACR
END DESCRIPTION:

--- UNT 0423 IN LACR.p01 (plan) ---

Plan Title=Multiple Run
Short Identifier=Multiple
Geom File=g01
Flow File=f01
Subcritical Flow
K Sum by GR= 0
Std Step Tol= 0.01
Critical Tol= 0.01
Num of Std Step Trials= 20
Max Error Tol= 0.3
Flow Tol Ratio= 0.001
Split Flow NTrial= 30
Split Flow Tol= 0.02
Split Flow Ratio= 0.02
Log Output Level= 0
Friction Slope Method= 1
Unsteady Friction Slope Method= 2
Unsteady Bridges Friction Slope Method= 1
Parabolic Critical Depth
Global Vel Dist=  1 , 1 , 1
Global Log Level= 0
CheckData=True
Encroach Param= -1, 0, 0, 0
BEGIN DESCRIPTION:
Multiple Run
END DESCRIPTION:

--- UNT 0423 IN LACR.f01 (steady flow) ---

Flow Title=Multiple
Number of Profiles=7
Profile Names=10-year,25-year,50-year,1pct_min,100-year,1pct_plu,500-year
River Rch & RM= UNT 0423 IN LACR,Reach-1,8372
     469     627     755     669     904    1223    1302
Boundary for River Rch & Prof#=UNT 0423 IN LACR,Reach-1,1
Up Type=0
Dn Type=3
Dn Slope=0.005
Boundary for River Rch & Prof#=UNT 0423 IN LACR,Reach-1,2
Up Type=0
Dn Type=3
Dn Slope=0.005
Boundary for River Rch & Prof#=UNT 0423 IN LACR,Reach-1,3
Up Type=0
Dn Type=3
Dn Slope=0.005
Boundary for River Rch & Prof#=UNT 0423 IN LACR,Reach-1,4
Up Type=0
Dn Type=3
Dn Slope=0.005
Boundary for River Rch & Prof#=UNT 0423 IN LACR,Reach-1,5
Up Type=0
Dn Type=3
Dn Slope=0.005
Boundary for River Rch & Prof#=UNT 0423 IN LACR,Reach-1,6
Up Type=0
Dn Type=3
Dn Slope=0.005
Boundary for River Rch & Prof#=UNT 0423 IN LACR,Reach-1,7
Up Type=0
Dn Type=3
Dn Slope=0.005

--- UNT 0423 IN LACR.g01 (geometry) ---

Geom Title=Existing Conditions

River Reach=UNT 0423 IN LACR,Reach-1
Reach XY= 30
      3657372.50     10615761.00      3657316.00     10616028.00
      3657235.00     10616068.00      3657029.50     10616455.00
      3657107.50     10616596.00      3657103.25     10616825.00
      3657215.00     10616889.00      3657178.50     10617097.00
      3657379.00     10617195.00      3657361.75     10617360.00
      3657590.50     10617466.00      3657653.75     10617610.00
      3657586.00     10617694.00      3657593.50     10617958.00
      3657482.50     10617983.00      3657339.25     10618201.00
      3657619.75     10618365.00      3657767.50     10618974.00
      3657669.25     10619005.00      3657168.50     10618825.00
      3656814.25     10619013.00      3656696.25     10619291.00
      3656689.25     10619575.00      3656984.50     10620020.00
      3657001.75     10620325.00      3656762.25     10620732.00
      3656331.75     10620926.00      3656283.00     10621016.00
      3656203.25     10621367.00      3656303.50     10621706.00

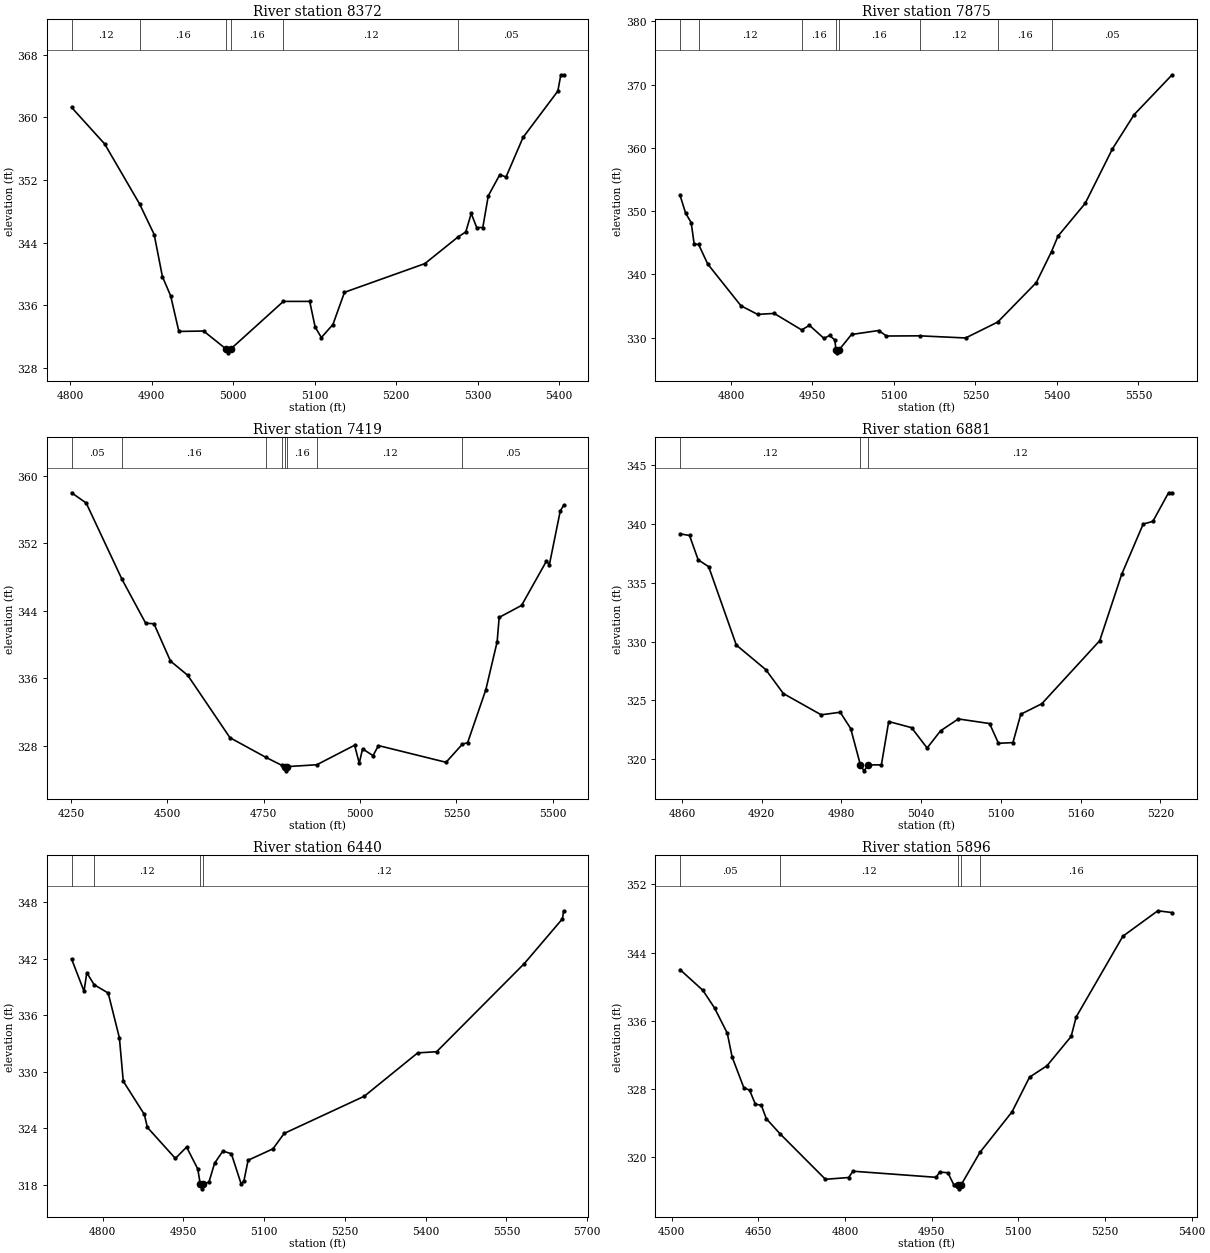
Type RM Length L Ch R = 1,8372,497,497,497
BEGIN DESCRIPTION:
UNT 0423 IN LACR 17.0
END DESCRIPTION:
XS GIS Cut Line= 3
      3657099.57     10616010.18      3657295.50     10616042.00
      3657599.63     10616310.21
#Sta/Elev= 30
  4801.5  361.26  4842.1  356.60  4884.9  348.96  4902.9  345.05  4913.0  339.68
  4923.1  337.23  4933.2  332.69  4963.6  332.74  4991.0  330.46  4993.8  329.96
  4997.0  330.46  5061.5  336.52  5093.8  336.52  5100.5  333.25  5108.1  331.91
  5122.3  333.57  5136.5  337.68  5235.2  341.34  5275.7  344.72  5285.4  345.38
  5292.1  347.74  5298.8  345.94  5306.3  345.94  5313.0  349.98  5327.2  352.69
  5334.8  352.38  5355.7  357.43  5398.4  363.34  5402.1  365.42  5405.5  365.42
#Mann=6,-1,0
  4801.5    0.12       0  4884.9    0.16       0  4991.0    0.07       0
  4997.0    0.16       0  5061.5    0.12       0  5275.7    0.05       0
Bank Sta=4991,4997
Exp/Cntr=0.3,0.1

Type RM Length L Ch R = 1,7875,456,456,456
BEGIN DESCRIPTION:
UNT 0423 IN LACR 16.0
END DESCRIPTION:
XS GIS Cut Line= 3
      3656749.61     10616360.19      3657037.75     10616416.00
      3657649.62     10616410.19
#Sta/Elev= 30
  4706.5  352.46  4716.7  349.65  4726.9  348.17  4732.4  344.77  4740.6  344.71
  4757.4  341.61  4818.5  335.02  4849.1  333.66  4879.7  333.81  4930.2  331.20
  4944.5  331.93  4971.3  329.86  4981.5  330.33  4991.2  329.61  4993.3  328.08
  4996.0  327.58  4999.3  328.08  5021.9  330.48  5071.9  331.11  5086.2  330.24
  5147.2  330.27  5231.9  329.93  5291.0  332.45  5361.9  338.68  5390.0  343.60
  5401.9  346.03  5451.9  351.21  5501.9  359.80  5541.9  365.23  5611.9  371.54
#Mann=8,-1,0
  4706.5    0.16       0  4740.6    0.12       0  4930.2    0.16       0
  4993.3    0.07       0  4999.3    0.16       0  5147.2    0.12       0
  5291.0    0.16       0  5390.0    0.05       0
Bank Sta=4993.3,4999.3
Exp/Cntr=0.3,0.1

Type RM Length L Ch R = 1,7419,538,538,538
BEGIN DESCRIPTION:
UNT 0423 IN LACR 15.0
END DESCRIPTION:
XS GIS Cut Line= 3
      3656449.47     10617182.94      3657029.29     10616842.69
      3657615.33     10616693.57
#Sta/Elev= 30
  4251.4  357.98  4289.3  356.77  4382.2  347.74  4443.7  342.54  4465.2  342.48
  4508.1  338.06  4553.0  336.37  4662.5  328.99  4756.0  326.66  4797.2  325.72
  4805.1  325.57  4807.9  325.07  4811.1  325.57  4887.9  325.79  4985.9  328.10
  4998.0  325.98  5006.6  327.67  5033.8  326.87  5047.8  328.06  5223.3  326.08
  5265.5  328.22  5279.3  328.41  5326.4  334.65  5355.9  340.35  5361.1  343.23
  5419.3  344.65  5483.8  349.89  5491.5  349.48  5519.6  355.81  5528.4  356.50
#Mann=8,-1,0
  4251.4    0.05       0  4382.2    0.16       0  4756.0    0.12       0
  4797.2    0.16       0  4805.1    0.07       0  4811.1    0.16       0
  4887.9    0.12       0  5265.5    0.05       0
Bank Sta=4805.1,4811.1
Exp/Cntr=0.3,0.1

Type RM Length L Ch R = 1,6881,441,441,441
BEGIN DESCRIPTION:
UNT 0423 IN LACR 14.0
END DESCRIPTION:
XS GIS Cut Line= 3
      3657199.63     10617260.17      3657289.50     10617151.00
      3657499.61     10617060.19
#Sta/Elev= 30
  4858.6  339.15  4865.7  339.01  4872.2  336.94  4880.1  336.36  4900.9  329.70
  4923.1  327.61  4936.3  325.58  4964.8  323.77  4979.1  323.99  4987.0  322.60
  4994.3  319.51  4997.0  319.01  5000.3  319.51  5010.1  319.52  5015.6  323.20
  5032.8  322.68  5044.5  320.95  5054.6  322.41  5068.0  323.42  5091.5  323.03
  5098.2  321.35  5109.1  321.41  5115.0  323.82  5130.8  324.71  5174.4  330.07
  5190.9  335.70  5207.1  339.98  5214.4  340.21  5226.2  342.64  5228.9  342.64
#Mann=3,-1,0
  4858.6    0.12       0  4994.3    0.07       0  5000.3    0.12       0
Bank Sta=4994.3,5000.3
Exp/Cntr=0.3,0.1

Type RM Length L Ch R = 1,6440,544,544,544
BEGIN DESCRIPTION:
UNT 0423 IN LACR 13.0
END DESCRIPTION:
XS GIS Cut Line= 3
      3657234.16     10617491.99      3657564.01     10617398.24
      3657986.35     10617013.98
#Sta/Elev= 30
  4742.2  341.98  4765.3  338.55  4770.5  340.52  4784.1  339.24  4810.2  338.36
  4831.0  333.60  4838.2  328.99  4877.3  325.46  4883.0  324.08  4935.0  320.78
  4955.8  321.99  4976.6  319.66  4981.2  318.05  4983.9  317.55  4987.2  318.05
  4997.4  318.28  5007.8  320.27  5023.2  321.56  5039.0  321.28  5057.1  318.08
  5062.3  318.40  5070.1  320.59  5116.2  321.80  5137.1  323.44  5285.8  327.39
  5385.1  332.00  5420.2  332.12  5583.1  341.49  5654.0  346.25  5656.1  347.10
#Mann=4,-1,0
  4742.2    0.05       0  4784.1    0.12       0  4981.2    0.07       0
  4987.2    0.12       0
Bank Sta=4981.2,4987.2
Exp/Cntr=0.3,0.1

Type RM Length L Ch R = 1,5896,564,564,564
BEGIN DESCRIPTION:
UNT 0423 IN LACR 12.0
END DESCRIPTION:
XS GIS Cut Line= 2
      3657140.42     10617724.63      3657984.18     10617839.22
#Sta/Elev= 30
  4514.6  341.99  4554.1  339.56  4574.3  337.48  4596.3  334.53  4604.6  331.75
  4624.8  328.15  4634.9  327.84  4645.0  326.18  4655.1  326.10  4663.7  324.51
  4687.4  322.74  4766.1  317.39  4806.4  317.60  4813.7  318.34  4957.8  317.62
  4963.7  318.24  4978.0  318.16  4988.1  316.77  4995.2  316.77  4997.9  316.27
  5001.2  316.77  5033.6  320.56  5089.0  325.30  5119.3  329.37  5149.6  330.72
  5191.3  334.15  5200.0  336.43  5280.8  345.91  5341.3  348.90  5366.1  348.69
#Mann=5,-1,0
  4514.6    0.05       0  4687.4    0.12       0  4995.2    0.07       0
  5001.2    0.12       0  5033.6    0.16       0
Bank Sta=4995.2,5001.2
Exp/Cntr=0.3,0.1

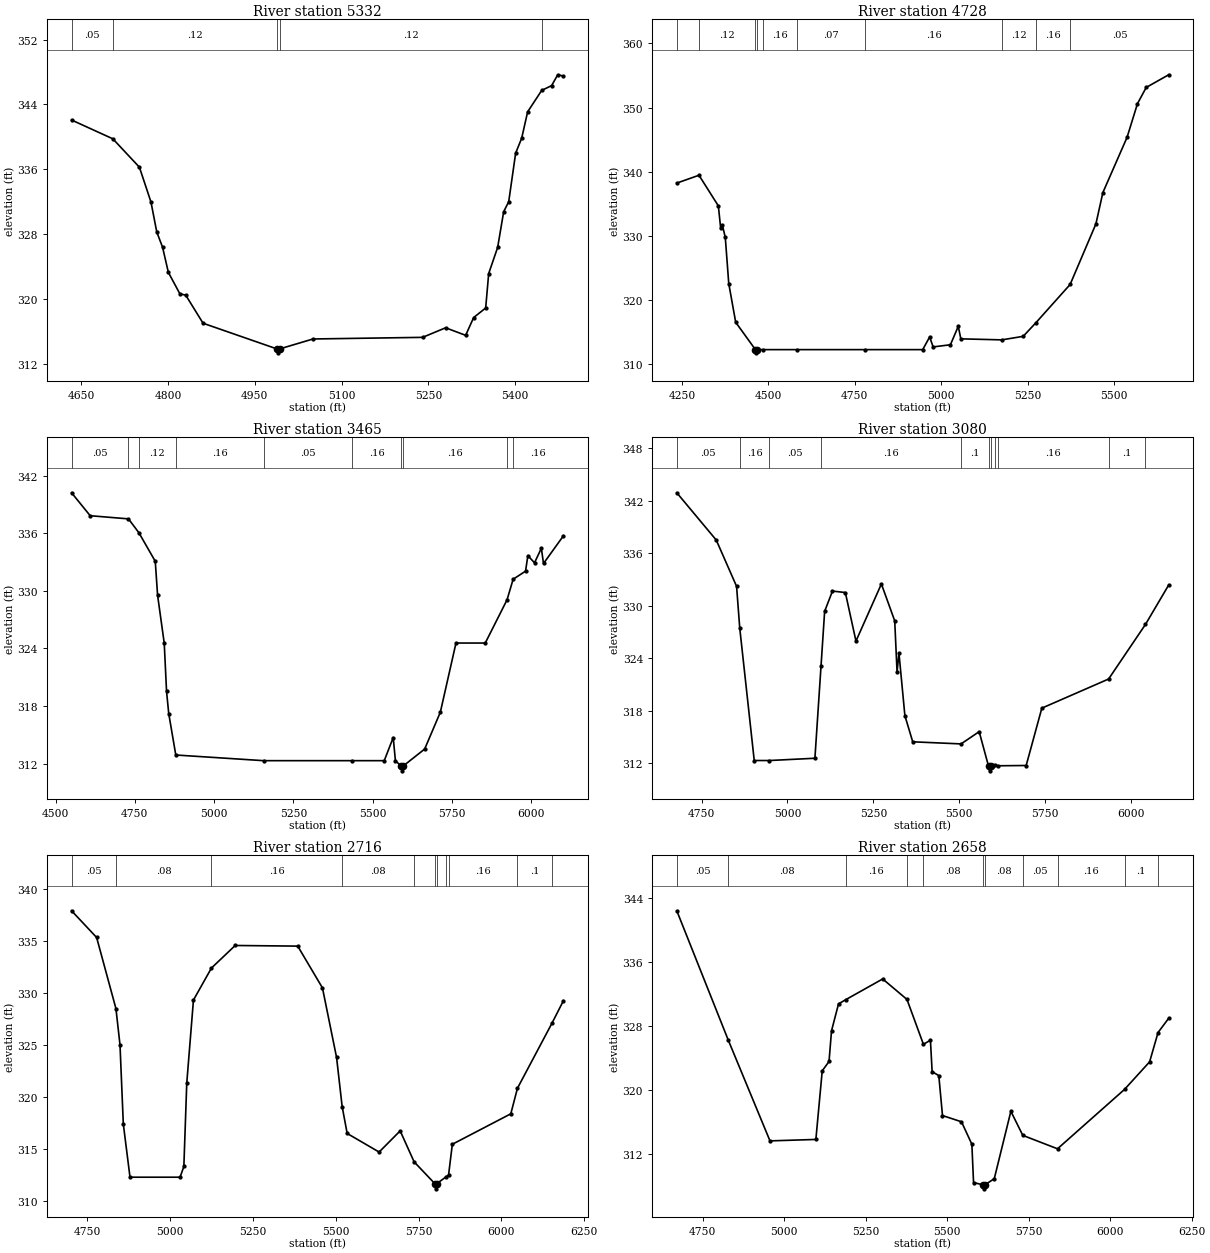
Type RM Length L Ch R = 1,5332,604,604,604
BEGIN DESCRIPTION:
UNT 0423 IN LACR 11.0
END DESCRIPTION:
XS GIS Cut Line= 3
      3656972.46     10618161.59      3657451.65     10618168.54
      3657809.33     10618071.30
#Sta/Elev= 30
  4633.6  342.07  4704.9  339.75  4750.8  336.25  4770.8  331.95  4780.8  328.26
  4790.8  326.38  4800.8  323.28  4820.8  320.62  4830.8  320.47  4860.8  317.00
  4987.8  313.85  4990.5  313.35  4993.8  313.85  5050.8  315.06  5240.1  315.26
  5279.9  316.44  5314.5  315.51  5328.3  317.70  5349.1  318.88  5354.3  323.13
  5369.8  326.36  5380.2  330.76  5388.9  331.99  5400.9  337.99  5411.3  339.82
  5421.6  343.08  5445.9  345.72  5463.1  346.32  5473.6  347.65  5483.5  347.49
#Mann=5,-1,0
  4633.6    0.05       0  4704.9    0.12       0  4987.8    0.07       0
  4993.8    0.12       0  5445.9    0.16       0
Bank Sta=4987.8,4993.8
Exp/Cntr=0.3,0.1

Type RM Length L Ch R = 1,4728,1263,1263,1263
BEGIN DESCRIPTION:
Mapping XS e8d01900
END DESCRIPTION:
XS GIS Cut Line= 2
      3656899.60     10618515.76      3658319.69     10618619.92
#Sta/Elev= 30
  4234.6  338.24  4298.8  339.46  4354.9  334.69  4361.7  331.17  4366.7  331.66
  4375.0  329.77  4385.0  322.59  4405.1  316.56  4462.2  312.30  4465.0  311.80
  4468.2  312.30  4483.0  312.30  4581.9  312.30  4779.7  312.30  4946.5  312.30
  4966.6  314.28  4976.6  312.72  5026.7  313.06  5049.4  315.93  5056.8  313.98
  5175.4  313.82  5237.3  314.37  5274.3  316.50  5373.2  322.45  5447.9  331.89
  5467.9  336.75  5538.1  345.38  5568.2  350.62  5593.5  353.14  5658.5  355.11
#Mann=10,-1,0
  4234.6    0.05       0  4298.8    0.12       0  4462.2    0.07       0
  4468.2    0.12       0  4483.0    0.16       0  4581.9    0.07       0
  4779.7    0.16       0  5175.4    0.12       0  5274.3    0.16       0
  5373.2    0.05       0
Bank Sta=4462.2,4468.2
Exp/Cntr=0.3,0.1

Type RM Length L Ch R = 1,3465,385,385,385
BEGIN DESCRIPTION:
UNT 0423 IN LACR 8.0
END DESCRIPTION:
XS GIS Cut Line= 2
      3656689.42     10618567.31      3657817.86     10619630.64
#Sta/Elev= 30
  4550.6  340.22  4609.3  337.83  4729.9  337.50  4762.5  336.07  4814.4  333.08
  4821.7  329.55  4842.7  324.54  4850.0  319.51  4856.9  317.20  4879.1  312.89
  5155.8  312.30  5435.7  312.30  5536.2  312.30  5564.5  314.71  5571.4  312.29
  5589.8  311.74  5592.6  311.24  5595.8  311.74  5663.6  313.51  5713.0  317.35
  5762.3  324.56  5854.6  324.56  5923.2  329.06  5942.5  331.21  5981.6  332.05
  5988.9  333.67  6009.9  332.92  6031.4  334.44  6038.2  332.85  6101.1  335.74
#Mann=10,-1,0
  4550.6    0.05       0  4729.9    0.16       0  4762.5    0.12       0
  4879.1    0.16       0  5155.8    0.05       0  5435.7    0.16       0
  5589.8    0.07       0  5595.8    0.16       0  5923.2     0.1       0
  5942.5    0.16       0
Bank Sta=5589.8,5595.8
Exp/Cntr=0.3,0.1

Type RM Length L Ch R = 1,3080,364,364,364
BEGIN DESCRIPTION:
UNT 0423 IN LACR 7.0
END DESCRIPTION:
XS GIS Cut Line= 2
      3656465.64     10619001.81      3657761.19     10619611.17
#Sta/Elev= 30
  4678.0  342.92  4792.9  337.51  4852.0  332.22  4861.3  327.41  4903.4  312.30
  4947.4  312.30  5080.0  312.56  5097.9  323.16  5108.3  329.36  5131.1  331.68
  5168.6  331.51  5199.5  325.96  5273.5  332.49  5312.3  328.27  5319.1  322.42
  5324.6  324.59  5341.9  317.43  5364.7  314.44  5505.4  314.20  5558.1  315.60
  5585.6  311.62  5588.3  311.12  5591.6  311.62  5603.1  311.83  5612.8  311.70
  5694.9  311.73  5740.5  318.29  5934.8  321.62  6042.2  327.87  6109.7  332.37
#Mann=11,-1,0
  4678.0    0.05       0  4861.3    0.16       0  4947.4    0.05       0
  5097.9    0.16       0  5505.4     0.1       0  5585.6   0.033       0
  5591.6     0.1       0  5603.1    0.08       0  5612.8    0.16       0
  5934.8     0.1       0  6042.2    0.16       0
Bank Sta=5585.6,5591.6
Exp/Cntr=0.3,0.1

Type RM Length L Ch R = 1,2716,58,58,58
BEGIN DESCRIPTION:
Mapping XS 645e96d5
END DESCRIPTION:
XS GIS Cut Line= 4
      3656384.61     10619451.34      3656766.56     10619501.68
      3656926.28     10619321.13      3657731.79     10619621.46
#Sta/Elev= 30
  4701.9  337.94  4777.6  335.37  4835.9  328.53  4848.2  325.04  4858.2  317.42
  4878.4  312.30  5029.7  312.30  5041.1  313.33  5049.9  321.36  5070.1  329.35
  5124.5  332.43  5196.2  334.60  5385.1  334.54  5459.8  330.52  5502.5  323.82
  5519.3  319.10  5534.5  316.51  5631.0  314.72  5694.6  316.76  5736.7  313.78
  5799.3  311.68  5802.0  311.18  5805.3  311.68  5832.7  312.32  5840.8  312.51
  5852.2  315.47  6028.8  318.40  6048.9  320.86  6153.0  327.11  6187.9  329.29
#Mann=11,-1,0
  4701.9    0.05       0  4835.9    0.08       0  5124.5    0.16       0
  5519.3    0.08       0  5736.7    0.16       0  5799.3    0.07       0
  5805.3    0.16       0  5832.7    0.05       0  5840.8    0.16       0
  6048.9     0.1       0  6153.0    0.16       0
Bank Sta=5799.3,5805.3
Exp/Cntr=0.3,0.1

Type RM Length L Ch R = 1,2658,75,75,75
BEGIN DESCRIPTION:
UNT 0423 IN LACR 6.0
END DESCRIPTION:
XS GIS Cut Line= 4
      3656356.79     10619531.20      3656778.71     10619552.03
      3656917.60     10619366.27      3657729.50     10619633.74
#Sta/Elev= 30
  4670.1  342.45  4828.2  326.25  4956.0  313.66  5096.8  313.84  5116.3  322.42
  5137.2  323.60  5144.8  327.43  5166.3  330.80  5188.1  331.32  5301.8  333.92
  5376.3  331.36  5426.8  325.74  5448.3  326.26  5453.5  322.32  5474.0  321.83
  5485.3  316.83  5543.6  316.05  5575.4  313.24  5580.6  308.45  5609.4  308.16
  5612.1  307.66  5615.4  308.16  5644.2  308.93  5695.1  317.36  5731.7  314.35
  5838.2  312.67  6043.8  320.10  6120.8  323.55  6146.7  327.22  6179.3  329.00
#Mann=11,-1,0
  4670.1    0.05       0  4828.2    0.08       0  5188.1    0.16       0
  5376.3    0.05       0  5426.8    0.08       0  5609.4    0.07       0
  5615.4    0.08       0  5731.7    0.05       0  5838.2    0.16       0
  6043.8     0.1       0  6146.7    0.16       0
Bank Sta=5609.4,5615.4
Exp/Cntr=0.3,0.1

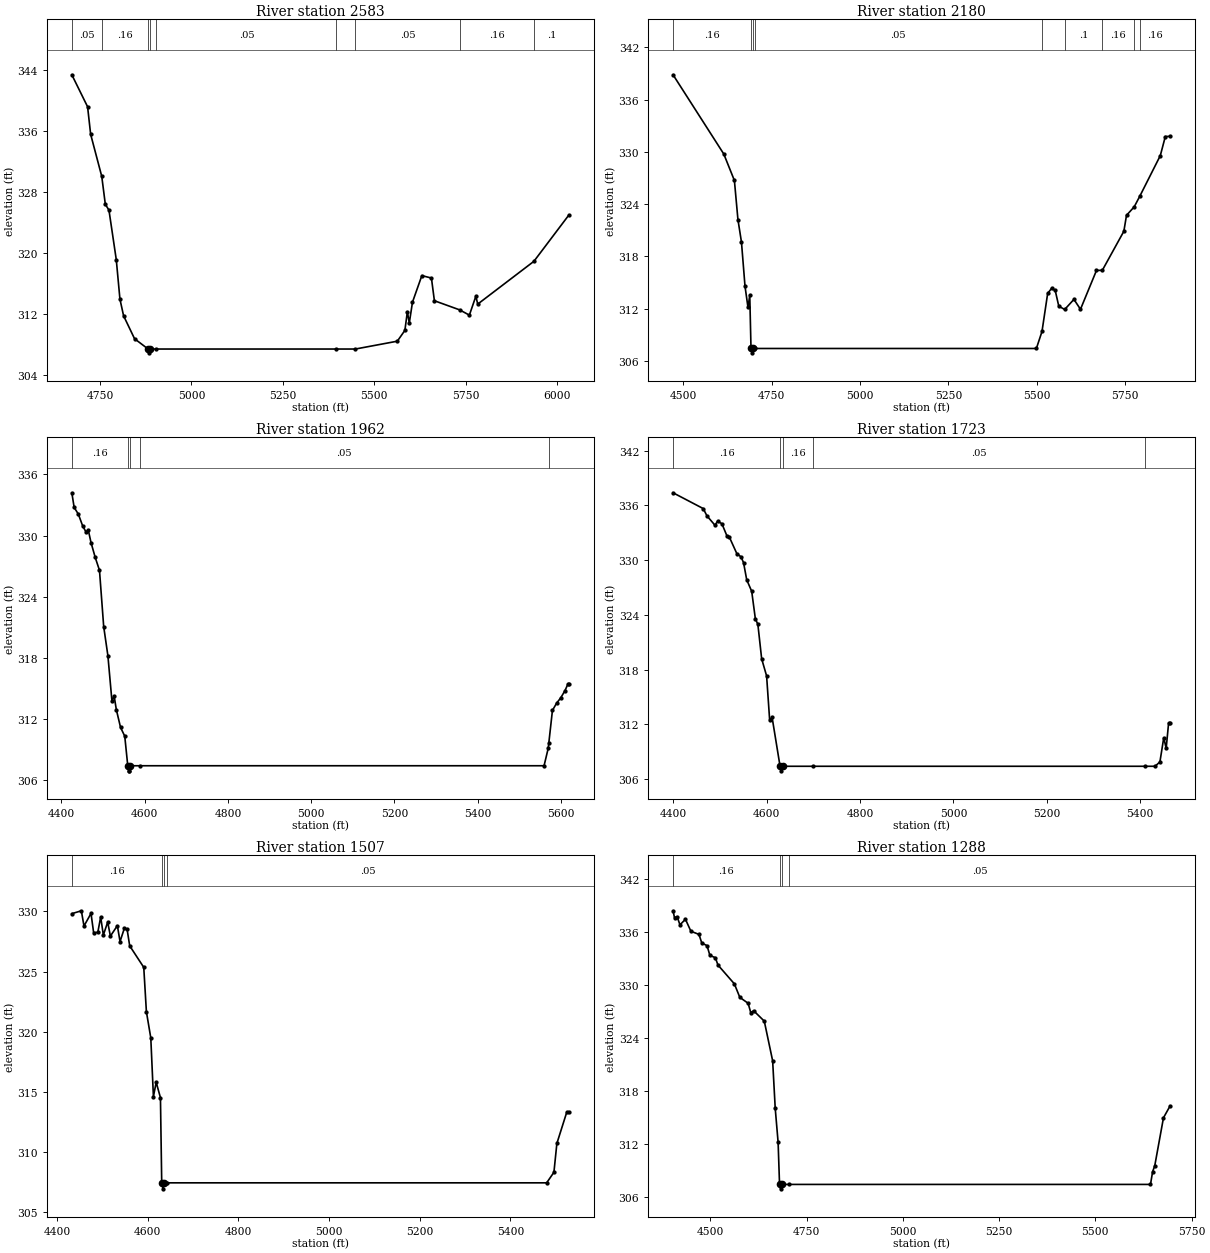
Type RM Length L Ch R = 1,2583,403,403,403
BEGIN DESCRIPTION:
Mapping XS e06fd841
END DESCRIPTION:
XS GIS Cut Line= 4
      3656388.10     10619626.68      3656848.15     10619609.32
      3657094.68     10619477.38      3657691.92     10619642.32
#Sta/Elev= 30
  4672.9  343.42  4716.0  339.22  4724.4  335.60  4754.8  330.07  4764.5  326.42
  4774.5  325.64  4794.5  319.14  4804.5  313.96  4814.5  311.77  4844.5  308.76
  4881.6  307.41  4884.3  306.91  4887.6  307.41  4904.3  307.41  5396.8  307.41
  5448.6  307.41  5563.3  308.44  5584.0  309.86  5590.8  312.32  5596.0  310.81
  5604.8  313.57  5630.4  317.05  5656.6  316.73  5664.7  313.75  5733.9  312.55
  5760.4  311.86  5778.1  314.34  5783.3  313.31  5937.0  318.93  6032.5  325.00
#Mann=9,-1,0
  4672.9    0.05       0  4754.8    0.16       0  4881.6   0.033       0
  4887.6    0.16       0  4904.3    0.05       0  5396.8    0.08       0
  5448.6    0.05       0  5733.9    0.16       0  5937.0     0.1       0
Bank Sta=4881.6,4887.6
Exp/Cntr=0.3,0.1

Type RM Length L Ch R = 1,2180,218,218,218
BEGIN DESCRIPTION:
UNT 0423 IN LACR 5.0
END DESCRIPTION:
XS GIS Cut Line= 3
      3656415.93     10619947.50      3657023.60     10619940.99
      3657775.60     10619670.10
#Sta/Elev= 30
  4470.5  338.84  4614.2  329.74  4644.2  326.70  4654.2  322.22  4664.2  319.63
  4674.2  314.57  4682.7  312.12  4687.7  313.52  4691.2  307.41  4693.9  306.91
  4697.2  307.41  4701.4  307.41  5499.1  307.41  5515.0  309.37  5531.0  313.73
  5542.4  314.33  5552.3  314.09  5562.5  312.27  5579.2  311.89  5605.4  313.05
  5623.9  311.91  5669.2  316.37  5685.8  316.39  5746.7  320.87  5754.2  322.70
  5776.1  323.68  5792.4  324.94  5849.9  329.56  5864.1  331.75  5877.5  331.77
#Mann=9,-1,0
  4470.5    0.16       0  4691.2   0.033       0  4697.2    0.16       0
  4701.4    0.05       0  5515.0    0.08       0  5579.2     0.1       0
  5685.8    0.16       0  5776.1     0.1       0  5792.4    0.16       0
Bank Sta=4691.2,4697.2
Exp/Cntr=0.3,0.1

Type RM Length L Ch R = 1,1962,239,239,239
BEGIN DESCRIPTION:
Mapping XS c551a1ec
END DESCRIPTION:
XS GIS Cut Line= 3
      3656444.07     10620069.24      3656960.55     10620151.71
      3657628.93     10620098.66
#Sta/Elev= 30
  4425.2  334.20  4430.8  332.76  4440.9  332.10  4451.1  330.96  4459.5  330.33
  4464.6  330.56  4471.3  329.31  4481.4  327.85  4491.6  326.59  4501.7  321.07
  4511.8  318.21  4521.6  313.72  4526.7  314.28  4532.1  312.91  4542.2  311.17
  4552.3  310.31  4559.5  307.41  4562.2  306.91  4562.7  306.91  4565.5  307.41
  4588.7  307.41  5559.2  307.41  5569.2  309.13  5570.6  309.64  5579.3  312.84
  5589.3  313.55  5599.3  314.08  5609.4  314.78  5616.5  315.43  5618.7  315.43
#Mann=5,-1,0
  4425.2    0.16       0  4559.5   0.033       0  4565.5    0.16       0
  4588.7    0.05       0  5570.6    0.08       0
Bank Sta=4559.5,4565.5
Exp/Cntr=0.3,0.1

Type RM Length L Ch R = 1,1723,216,216,216
BEGIN DESCRIPTION:
UNT 0423 IN LACR 4.0
END DESCRIPTION:
XS GIS Cut Line= 3
      3656411.39     10620174.02      3657088.46     10620420.54
      3657420.62     10620507.84
#Sta/Elev= 30
  4399.8  337.38  4464.4  335.65  4472.4  334.85  4489.6  333.82  4495.0  334.26
  4504.3  334.00  4514.9  332.69  4520.2  332.54  4536.3  330.72  4545.5  330.35
  4550.8  329.71  4557.5  327.85  4568.2  326.58  4576.0  323.58  4581.4  322.96
  4589.5  319.19  4600.1  317.31  4606.6  312.49  4611.9  312.76  4628.9  307.41
  4631.6  306.91  4634.9  307.41  4698.7  307.41  5409.3  307.41  5431.7  307.41
  5442.1  307.89  5450.3  310.54  5455.5  309.38  5460.7  312.15  5463.8  312.15
#Mann=5,-1,0
  4399.8    0.16       0  4628.9   0.033       0  4634.9    0.16       0
  4698.7    0.05       0  5409.3    0.08       0
Bank Sta=4628.9,4634.9
Exp/Cntr=0.3,0.1

Type RM Length L Ch R = 1,1507,219,219,219
BEGIN DESCRIPTION:
Mapping XS 3bd88cdf
END DESCRIPTION:
XS GIS Cut Line= 3
      3656400.64     10620281.91      3657086.42     10620698.58
      3657342.69     10620841.56
#Sta/Elev= 30
  4433.0  329.82  4454.0  330.06  4459.8  328.79  4475.3  329.84  4481.1  328.23
  4490.3  328.27  4496.6  329.54  4502.5  328.04  4512.1  329.12  4518.0  327.95
  4533.4  328.82  4539.3  327.50  4548.8  328.60  4554.8  328.54  4560.6  327.14
  4591.6  325.35  4597.4  321.66  4607.1  319.48  4612.9  314.59  4619.0  315.78
  4628.4  314.50  4631.2  307.41  4634.0  306.91  4637.2  307.41  4643.4  307.41
  5480.0  307.41  5496.0  308.29  5502.5  310.69  5524.2  313.28  5528.9  313.28
#Mann=4,-1,0
  4433.0    0.16       0  4631.2   0.033       0  4637.2    0.16       0
  4643.4    0.05       0
Bank Sta=4631.2,4637.2
Exp/Cntr=0.3,0.1

Type RM Length L Ch R = 1,1288,455,455,455
BEGIN DESCRIPTION:
UNT 0423 IN LACR 3.0
END DESCRIPTION:
XS GIS Cut Line= 3
      3656304.21     10620340.49      3656908.34     10620887.34
      3657114.19     10621316.00
#Sta/Elev= 30
  4403.5  338.38  4407.3  337.60  4414.0  337.71  4421.5  336.79  4435.7  337.42
  4449.9  336.06  4470.8  335.71  4478.2  334.72  4491.7  334.44  4499.2  333.33
  4513.4  333.07  4520.1  332.24  4562.7  330.11  4576.9  328.58  4598.5  327.91
  4605.3  326.85  4612.7  327.07  4640.4  325.89  4662.1  321.40  4668.8  316.02
  4676.3  312.17  4680.0  307.41  4682.8  306.91  4686.0  307.41  4704.1  307.41
  5643.1  307.41  5648.6  308.85  5654.2  309.53  5676.8  314.95  5693.9  316.29
#Mann=4,-1,0
  4403.5    0.16       0  4680.0   0.033       0  4686.0    0.16       0
  4704.1    0.05       0
Bank Sta=4680,4686
Exp/Cntr=0.3,0.1

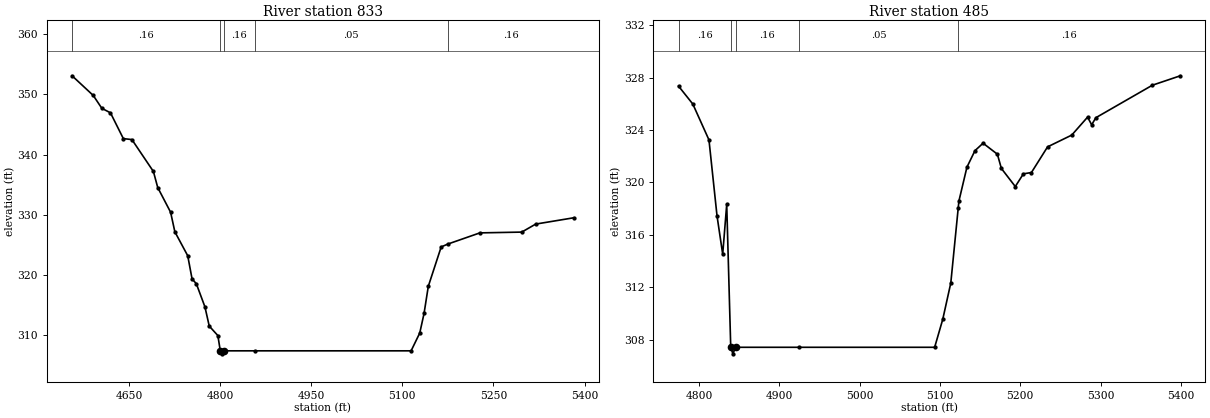
Type RM Length L Ch R = 1,833,348,348,348
BEGIN DESCRIPTION:
UNT 0423 IN LACR 2.0
END DESCRIPTION:
XS GIS Cut Line= 2
      3656017.48     10620612.99      3656602.85     10621195.76
#Sta/Elev= 30
  4556.4  353.07  4591.3  349.80  4605.4  347.67  4619.6  346.92  4640.8  342.64
  4654.9  342.48  4690.3  337.18  4697.4  334.52  4718.6  330.42  4725.6  327.17
  4746.8  323.19  4753.9  319.36  4761.0  318.54  4775.1  314.71  4782.2  311.52
  4796.4  309.94  4800.4  307.41  4803.2  306.91  4806.4  307.41  4856.7  307.41
  5114.5  307.41  5128.7  310.36  5135.8  313.61  5142.8  318.12  5164.0  324.66
  5175.1  325.14  5227.7  326.99  5296.6  327.12  5319.6  328.45  5382.4  329.50
#Mann=5,-1,0
  4556.4    0.16       0  4800.4   0.033       0  4806.4    0.16       0
  4856.7    0.05       0  5175.1    0.16       0
Bank Sta=4800.4,4806.4
Exp/Cntr=0.3,0.1

Type RM Length L Ch R = 1,485,0,0,0
BEGIN DESCRIPTION:
UNT 0423 IN LACR 1.0
END DESCRIPTION:
XS GIS Cut Line= 2
      3656001.88     10621230.20      3656624.29     10621284.88
#Sta/Elev= 30
  4774.5  327.36  4792.3  325.99  4812.4  323.25  4822.4  317.46  4829.5  314.52
  4834.5  318.33  4839.5  307.41  4842.2  306.91  4845.5  307.41  4924.8  307.41
  5093.4  307.41  5103.5  309.55  5113.5  312.32  5122.8  318.08  5123.6  318.58
  5133.6  321.17  5143.6  322.43  5153.7  323.00  5171.5  322.16  5176.5  321.07
  5193.8  319.69  5203.9  320.66  5213.9  320.76  5234.0  322.72  5264.1  323.62
  5283.8  324.99  5288.9  324.41  5294.2  324.95  5364.5  327.43  5399.3  328.15
#Mann=5,-1,0
  4774.5    0.16       0  4839.5   0.033       0  4845.5    0.16       0
  4924.8    0.05       0  5122.8    0.16       0
Bank Sta=4839.5,4845.5
Exp/Cntr=0.3,0.1

Chan Stop Cuts=-1