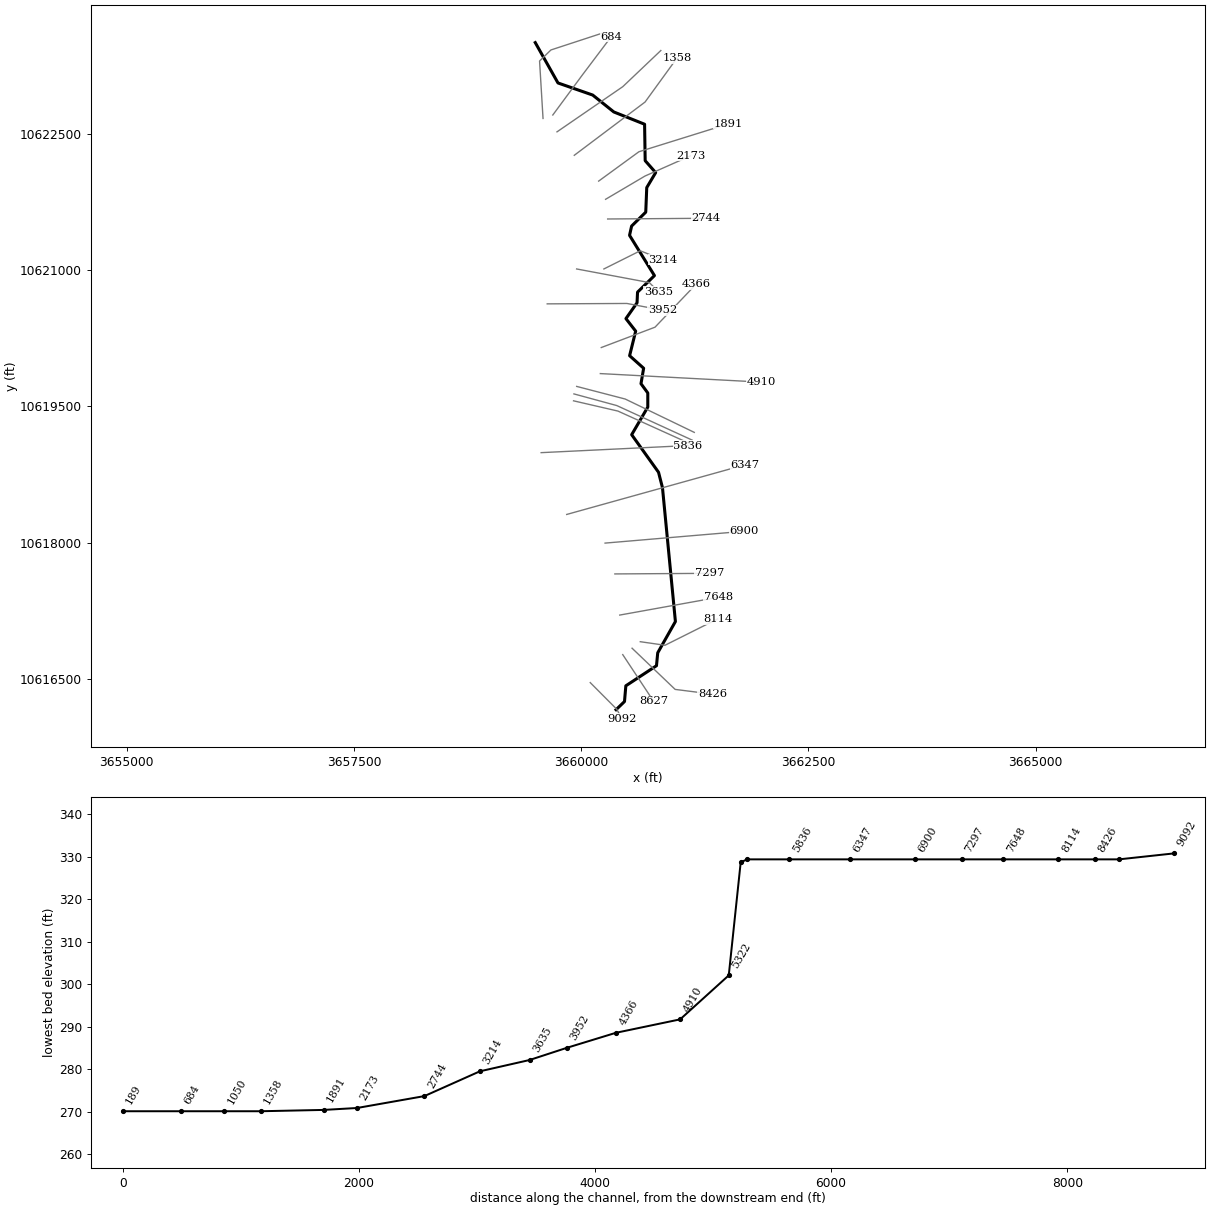
--- UNT 0424 IN LACR.prj (project) ---

Proj Title=UNT 0424 IN LACR Base Level Engineering
Current Plan=p01
Default Exp/Contr=0.3,0.1
English Units
Geom File=g01
Flow File=f01
Plan File=p01
Y Axis Title=Elevation
X Axis Title(PF)=Main Channel Distance
X Axis Title(XS)=Station
BEGIN DESCRIPTION:
UNT 0424 IN LACR
END DESCRIPTION:
DSS Export Rating Curves= 0
DSS Export Rating Curve Sorted= 0
DSS Export Volume Flow Curves= 0
DXF OffsetX= 0
DXF OffsetY= 0
DXF ScaleX= 1
DXF ScaleY= 10

--- UNT 0424 IN LACR.p01 (plan) ---

Plan Title=Multiple Run
Short Identifier=Multiple
Geom File=g01
Flow File=f01
Subcritical Flow
K Sum by GR= 0
Std Step Tol= 0.01
Critical Tol= 0.01
Num of Std Step Trials= 20
Max Error Tol= 0.3
Flow Tol Ratio= 0.001
Split Flow NTrial= 30
Split Flow Tol= 0.02
Split Flow Ratio= 0.02
Log Output Level= 0
Friction Slope Method= 1
Unsteady Friction Slope Method= 2
Unsteady Bridges Friction Slope Method= 1
Parabolic Critical Depth
Global Vel Dist=  1 , 1 , 1
Global Log Level= 0
CheckData=True
Encroach Param= -1, 0, 0, 0
BEGIN DESCRIPTION:
Multiple Run
END DESCRIPTION:

--- UNT 0424 IN LACR.f01 (steady flow) ---

Flow Title=Multiple
Program Version=4.10
Number of Profiles= 7
Profile Names=10-year,25-year,50-year,1pct_min,100-year,1pct_plu,500-year
River Rch & RM=UNT 0424 IN LACR,Reach-1         ,9092
     620     846    1033     928    1255    1697    1859
Boundary for River Rch & Prof#=UNT 0424 IN LACR,Reach-1         , 1
Up Type= 0
Dn Type= 3
Dn Slope=0.001
Boundary for River Rch & Prof#=UNT 0424 IN LACR,Reach-1         , 2
Up Type= 0
Dn Type= 3
Dn Slope=0.001
Boundary for River Rch & Prof#=UNT 0424 IN LACR,Reach-1         , 3
Up Type= 0
Dn Type= 3
Dn Slope=0.001
Boundary for River Rch & Prof#=UNT 0424 IN LACR,Reach-1         , 4
Up Type= 0
Dn Type= 3
Dn Slope=0.001
Boundary for River Rch & Prof#=UNT 0424 IN LACR,Reach-1         , 5
Up Type= 0
Dn Type= 3
Dn Slope=0.001
Boundary for River Rch & Prof#=UNT 0424 IN LACR,Reach-1         , 6
Up Type= 0
Dn Type= 3
Dn Slope=0.001
Boundary for River Rch & Prof#=UNT 0424 IN LACR,Reach-1         , 7
Up Type= 0
Dn Type= 3
Dn Slope=0.001
DSS Import GetInterval= 0
DSS Import GetPeak= 0
DSS Import FillOption= 0

--- UNT 0424 IN LACR.g01 (geometry) ---

Geom Title=Existing Conditions
Program Version=4.10

River Reach=UNT 0424 IN LACR,Reach-1
Reach XY= 30
      3660383.25       10616162.      3660476.25       10616252.
        3660491.       10616425.        3660828.       10616646.
      3660841.75       10616788.      3661036.25       10617132.
        3660894.       10618604.       3660850.5       10618774.
      3660555.25       10619187.       3660732.5       10619491.
       3660732.5       10619646.      3660657.75       10619748.
      3660686.75       10619918.       3660532.5       10620056.
      3660599.25       10620326.        3660492.       10620464.
      3660614.25       10620638.      3660619.75       10620755.
      3660805.75       10620937.      3660531.75       10621380.
      3660554.48     10621481.78        3660710.       10621635.
        3660721.       10621905.        3660819.       10622070.
      3660703.75       10622201.      3660697.25       10622602.
      3660358.75       10622737.       3660126.5       10622923.
       3659744.5       10623056.      3659494.75       10623500.

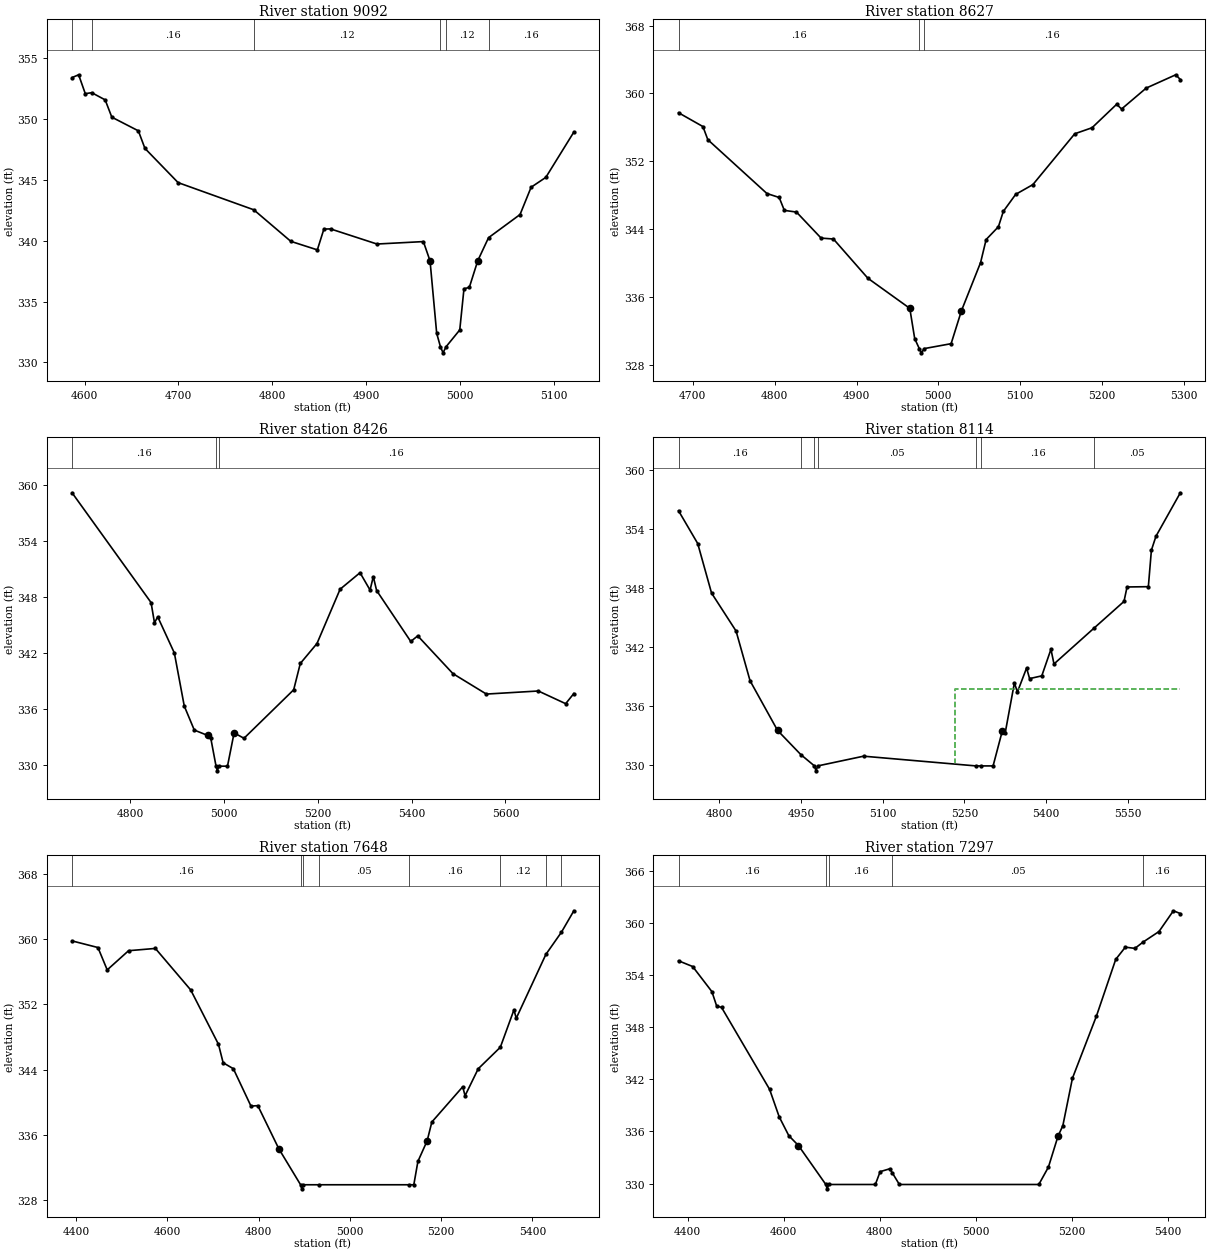
Type RM Length L Ch R = 1 ,9092    ,465,465,465
BEGIN DESCRIPTION:
UNT 0424 IN LACR 20.0
END DESCRIPTION:
XS GIS Cut Line= 3
      3660099.64     10616460.16      3660391.25       10616167.
       3660449.6      10616060.2
#Sta/Elev= 30
  4586.5  353.38  4593.5  353.61  4600.6  352.06  4607.5  352.14  4621.8  351.55
  4628.9  350.13  4657.2  349.01  4664.2  347.57  4699.6  344.76  4780.3  342.53
  4819.8  339.94  4848.1  339.24  4855.1  340.95  4862.2  340.96  4911.7  339.72
  4961.2  339.92  4968.3  338.34  4975.4  332.39  4979.4  331.29  4982.2  330.79
  4985.4  331.29    5000  332.67  5004.5  336.05  5010.2  336.16  5019.2  338.35
  5030.7  340.24  5064.3  342.14  5076.1  344.38  5091.8  345.19  5121.7  348.91
#Mann= 6 ,-1 , 0
  4586.5     .05       0  4607.5     .16       0  4780.3     .12       0
  4979.4     .07       0  4985.4     .12       0  5030.7     .16       0
Bank Sta=4968.3,5019.2
XS Rating Curve= 0 ,0
Exp/Cntr=0.3,0.1

Type RM Length L Ch R = 1 ,8627    ,201,201,201
BEGIN DESCRIPTION:
UNT 0424 IN LACR 19.0
END DESCRIPTION:
XS GIS Cut Line= 2
      3660456.93     10616768.09      3660795.06     10616256.55
#Sta/Elev= 30
  4682.5  357.72  4712.3  356.09  4718.3  354.54  4790.5  348.19  4805.5  347.72
  4811.8   346.2  4826.6     346  4856.7  342.93  4871.8  342.82  4913.9  338.19
  4965.1  334.64  4971.1  331.07  4976.7  329.89  4979.4  329.39  4982.7  329.89
  5015.6  330.47  5028.2  334.35  5051.6  340.04  5058.4  342.76  5073.4  344.27
  5079.4  346.08  5094.5  348.09  5115.5  349.24  5166.7  355.24  5187.8  355.95
  5217.9  358.72  5223.9  358.16    5254  360.63  5290.1   362.2  5295.7  361.64
#Mann= 3 ,-1 , 0
  4682.5     .16       0  4976.7     .07       0  4982.7     .16       0
Bank Sta=4965.1,5028.2
XS Rating Curve= 0 ,0
Exp/Cntr=0.3,0.1

Type RM Length L Ch R = 1 ,8426    ,312,312,312
BEGIN DESCRIPTION:
Mapping XS 495bce41
END DESCRIPTION:
XS GIS Cut Line= 3
      3660559.51     10616838.53      3661033.46     10616385.41
      3661444.77     10616333.34
#Sta/Elev= 30
  4675.7   359.2  4844.2  347.43  4851.5  345.26  4858.4   345.9  4893.9  342.02
    4915  336.34  4936.4  333.76  4964.7  333.19  4971.6  332.88  4982.8  329.89
  4985.5  329.39  4988.8  329.89  5007.2  329.89  5021.3  333.46  5042.4  332.88
  5148.4  338.08  5162.5   340.9  5198.1  343.04  5247.4  348.86  5289.9  350.63
  5311.3  348.77  5318.2  350.21  5325.3  348.72  5398.1  343.26    5413  343.86
  5488.1  339.81  5559.4  337.62  5670.2  337.95  5728.5  336.59    5746  337.68
#Mann= 3 ,-1 , 0
  4675.7     .16       0  4982.8     .07       0  4988.8     .16       0
Bank Sta=4964.7,5021.3
XS Rating Curve= 0 ,0
Exp/Cntr=0.3,0.1

Type RM Length L Ch R = 1 ,8114    ,466,466,466
BEGIN DESCRIPTION:
UNT 0424 IN LACR 18.0
END DESCRIPTION:
XS GIS Cut Line= 3
      3660649.66     10616910.18      3660921.75       10616871.
      3661499.63      10617160.2
#Sta/Elev= 30
  4725.1  355.84  4760.3  352.51  4785.7  347.47  4830.7  343.61  4856.4  338.55
  4906.9   333.5  4949.6  331.04  4974.6  329.89  4977.4  329.39  4980.6  329.89
  5064.7  330.88  5271.1  329.89  5279.9  329.89  5302.5  329.89  5319.2   333.4
  5324.8  333.27  5341.6  338.33  5347.2  337.41    5364  339.85  5369.5  338.77
  5391.9  339.05  5408.7  341.75  5414.3  340.26  5488.1  343.92  5542.8  346.62
  5548.4  348.09  5587.5  348.12  5593.1  351.83  5601.5  353.25  5646.2  357.67
#Mann= 7 ,-1 , 0
  4725.1     .16       0  4949.6     .05       0  4974.6    .035       0
  4980.6     .05       0  5271.1     .12       0  5279.9     .16       0
  5488.1     .05       0
#XS Ineff= 2 , 0
                         5232.26          337.73
Permanent Ineff=
       F       F
Bank Sta=4906.9,5319.2
XS Rating Curve= 0 ,0
Exp/Cntr=0.3,0.1

Type RM Length L Ch R = 1 ,7648    ,351,351,351
BEGIN DESCRIPTION:
UNT 0424 IN LACR 17.0
END DESCRIPTION:
XS GIS Cut Line= 2
      3660423.86     10617203.02      3661505.91      10617398.1
#Sta/Elev= 30
  4391.2  359.75  4447.9  358.94  4468.2   356.2    4515  358.55  4573.7  358.83
  4651.1  353.75    4712  347.09  4722.2  344.83  4744.6   344.1  4783.2  339.52
  4798.2  339.58  4844.1  334.31  4891.9  329.89  4894.7  329.39  4897.9  329.89
  4932.9  329.89    5130  329.89    5140  329.89    5149  332.75  5169.3  335.28
  5179.5  337.57  5247.2  341.89  5252.3  340.79  5281.1  344.09  5329.6  346.73
  5359.4   351.3  5364.5  350.28  5429.4   358.1  5463.5  360.82  5490.7  363.44
#Mann= 8 ,-1 , 0
  4391.2     .16       0  4891.9    .033       0  4897.9     .16       0
  4932.9     .05       0    5130     .16       0  5329.6     .12       0
  5429.4     .16       0  5463.5     .12       0
Bank Sta=4844.1,5169.3
XS Rating Curve= 0 ,0
Exp/Cntr=0.3,0.1

Type RM Length L Ch R = 1 ,7297    ,397,397,397
BEGIN DESCRIPTION:
UNT 0424 IN LACR 16.0
END DESCRIPTION:
XS GIS Cut Line= 2
      3660370.18     10617655.64      3661413.96     10617662.15
#Sta/Elev= 30
  4381.3  355.65  4410.7  354.99  4450.7   352.1  4460.7  350.43  4470.7  350.29
  4570.7  340.85  4590.7  337.68  4610.7  335.51  4630.7  334.38  4687.7  329.89
  4690.5  329.39  4693.7  329.89  4790.7  329.89  4800.7  331.37  4820.7   331.7
  4826.1  331.22  4840.7  329.89  5130.7  329.89  5150.7  331.89  5170.7  335.46
  5180.7  336.66  5200.7  342.13  5250.7   349.3  5290.7  355.81  5310.7  357.22
  5330.7  357.08  5347.2  357.79  5380.7  359.02  5410.7  361.41  5425.1  361.09
#Mann= 5 ,-1 , 0
  4381.3     .16       0  4687.7    .033       0  4693.7     .16       0
  4826.1     .05       0  5347.2     .16       0
Bank Sta=4630.7,5170.7
XS Rating Curve= 0 ,0
Exp/Cntr=0.3,0.1

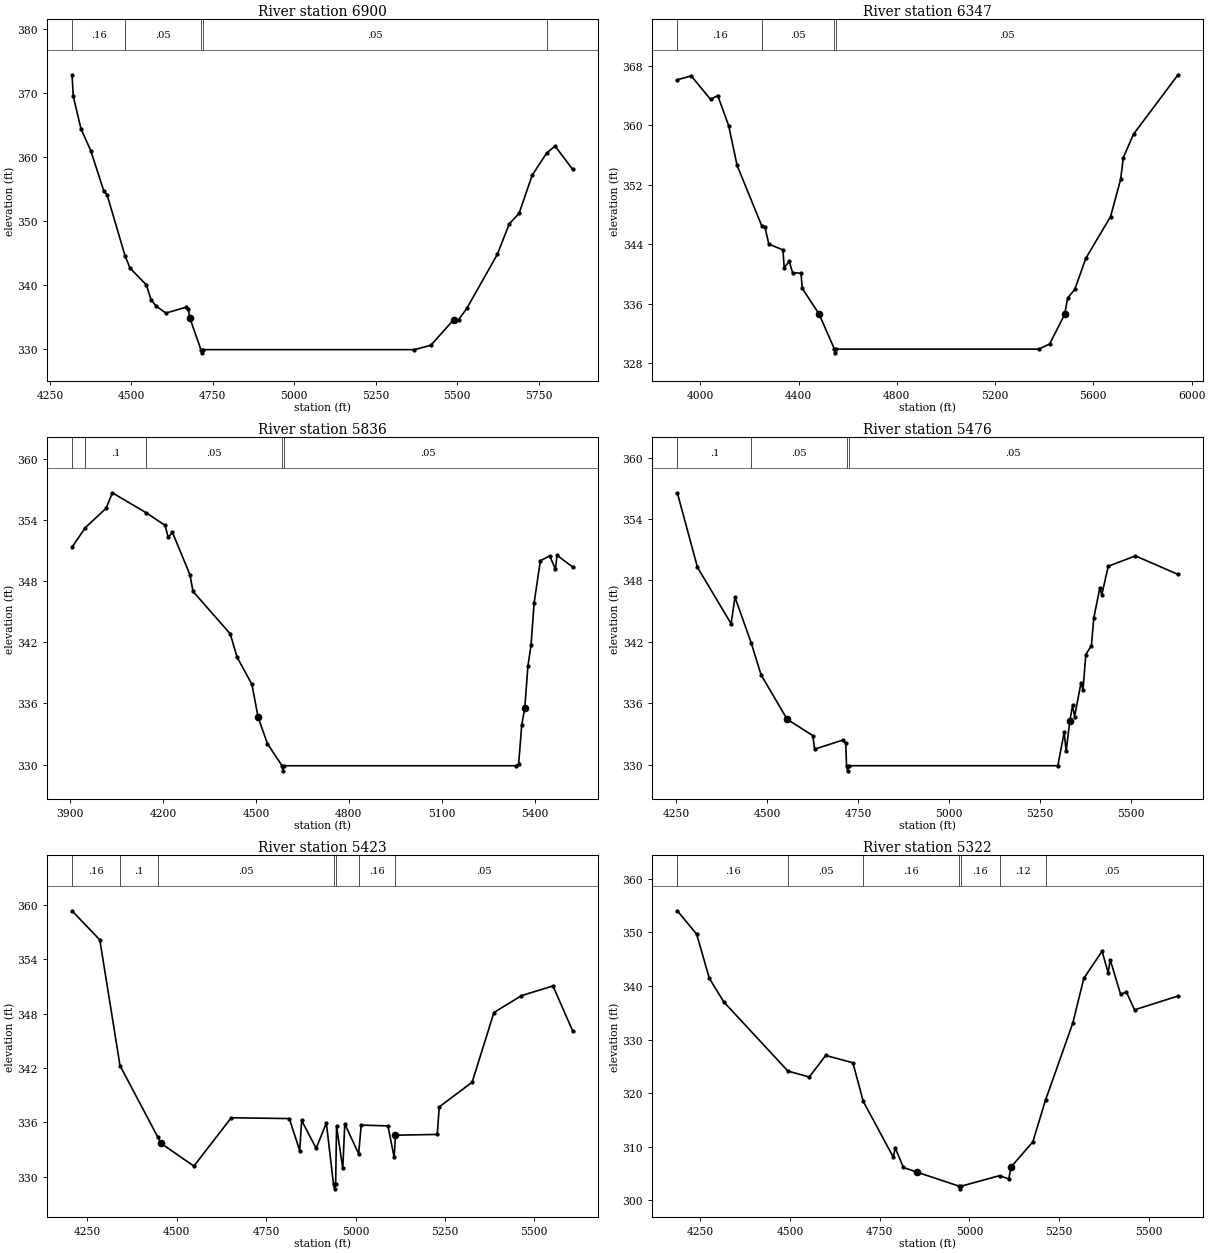
Type RM Length L Ch R = 1 ,6900    ,553,553,553
BEGIN DESCRIPTION:
UNT 0424 IN LACR 15.0
END DESCRIPTION:
XS GIS Cut Line= 2
      3660262.44     10617994.69      3661793.71      10618124.9
#Sta/Elev= 30
  4317.9   372.9  4321.9  369.51  4345.2  364.49  4375.3  361.04  4415.4  354.73
  4425.5  354.13  4480.5   344.6  4495.7  342.66  4545.9  340.03  4560.4  337.72
    4576   336.7  4606.1  335.61  4666.3  336.51  4674.6  336.27  4679.6  334.83
  4713.5  329.89  4716.3  329.39  4719.5  329.89  5368.9  329.89    5419  330.57
  5489.3  334.57  5504.2  334.58  5529.4  336.33  5623.4  344.81  5659.9  349.57
    5690  351.21  5730.2  357.17  5774.7  360.66  5800.4  361.75  5854.7  358.08
#Mann= 5 ,-1 , 0
  4317.9     .16       0  4480.5     .05       0  4713.5    .033       0
  4719.5     .05       0  5774.7     .16       0
Bank Sta=4679.6,5489.3
XS Rating Curve= 0 ,0
Exp/Cntr=0.3,0.1

Type RM Length L Ch R = 1 ,6347    ,511,511,511
BEGIN DESCRIPTION:
Mapping XS 8abcd4e5
END DESCRIPTION:
XS GIS Cut Line= 2
      3659840.58      10618309.8      3661804.05     10618856.66
#Sta/Elev= 30
  3906.4  366.15  3963.1  366.67  4041.9   363.5  4070.9  364.03  4115.5  359.96
  4149.7  354.63  4250.8  346.43  4262.7  346.36  4279.1  344.02  4336.3  343.25
  4341.5  340.86  4362.1  341.69  4375.7  340.17  4409.9  340.11  4415.1  338.06
  4483.5  334.61    4546  329.89  4548.7  329.39    4552  329.89  5377.2  329.89
  5421.7  330.57  5483.2  334.57  5495.3  336.76  5524.4  337.93  5568.9  342.09
  5670.1  347.74    5711  352.75    5722  355.68  5763.5  358.83  5944.6  366.82
#Mann= 4 ,-1 , 0
  3906.4     .16       0  4250.8     .05       0    4546    .033       0
    4552     .05       0
Bank Sta=4483.5,5483.2
XS Rating Curve= 0 ,0
Exp/Cntr=0.3,0.1

Type RM Length L Ch R = 1 ,5836    ,360,360,360
BEGIN DESCRIPTION:
Mapping XS 829a4ac4
END DESCRIPTION:
XS GIS Cut Line= 2
       3659559.5     10618989.57      3661174.11      10619067.7
#Sta/Elev= 30
  3906.4  351.33  3949.6  353.25  4016.6  355.14  4036.7  356.66  4145.8   354.7
  4206.9  353.46  4216.9  352.29  4230.7  352.77    4287  348.63    4297  346.99
  4417.1  342.83  4439.3  340.54  4487.2  337.87  4507.2  334.64  4537.2  332.06
  4584.3  329.89  4587.1  329.39  4590.3  329.89  5338.2  329.89  5348.2  330.04
  5358.2  333.88  5368.2  335.59  5378.2  339.66  5388.2  341.69  5398.3  345.87
  5418.3  349.99  5448.3  350.47  5467.1  349.17  5472.1  350.53  5522.9  349.38
#Mann= 5 ,-1 , 0
  3906.4     .16       0  3949.6      .1       0  4145.8     .05       0
  4584.3    .033       0  4590.3     .05       0
Bank Sta=4507.2,5368.2
XS Rating Curve= 0 ,0
Exp/Cntr=0.3,0.1

Type RM Length L Ch R = 1 ,5476    ,53,53,53
BEGIN DESCRIPTION:
UNT 0424 IN LACR 12.0
END DESCRIPTION:
XS GIS Cut Line= 3
      3659915.64     10619559.77      3660403.96     10619446.91
      3661200.38     10619086.68
#Sta/Elev= 30
  4253.2  356.57  4308.6  349.28    4401  343.77  4411.6  346.36  4456.6  341.85
  4483.1  338.79  4554.9  334.43  4625.2  332.84  4630.4  331.51  4708.9  332.41
  4715.8  332.07    4718  329.89  4720.7  329.39    4724  329.89  5298.4  329.89
  5315.8  333.16  5321.2  331.31  5331.3  334.28  5338.9  335.78  5344.4   334.7
    5362  337.99  5367.5  337.29  5375.2  340.76  5390.6  341.64  5397.2  344.33
  5413.7  347.28  5419.2   346.6  5436.8  349.39  5511.6   350.4  5628.5  348.59
#Mann= 4 ,-1 , 0
  4253.2      .1       0  4456.6     .05       0    4718     .03       0
    4724     .05       0
Bank Sta=4554.9,5331.3
XS Rating Curve= 0 ,0
Exp/Cntr=0.3,0.1

Type RM Length L Ch R = 1 ,5423    ,101,101,101
BEGIN DESCRIPTION:
Mapping XS cbfc66cb
END DESCRIPTION:
XS GIS Cut Line= 3
      3659920.05     10619635.71      3660390.94     10619507.68
      3661219.91     10619127.91
#Sta/Elev= 30
  4207.5  359.34  4285.2  356.13  4341.7  342.26  4447.4  334.37  4455.8   333.7
  4548.2  331.18  4652.7  336.51    4815  336.42    4844  332.89  4849.5  336.21
    4890  333.14  4918.5  335.93  4938.5  329.17  4941.3  328.67  4944.5  329.17
    4947  335.55  4964.5  330.92    4970  335.84  5008.8  332.53    5016   335.7
  5090.6  335.61  5108.1  332.15  5111.8  334.59  5228.6  334.67  5234.1  337.71
  5326.1  340.43    5387  348.12    5464  349.98    5552  351.05  5607.3  346.07
#Mann= 7 ,-1 , 0
  4207.5     .16       0  4341.7      .1       0  4447.4     .05       0
  4938.5     .03       0  4944.5     .05       0  5008.8     .16       0
  5111.8     .05       0
Bank Sta=4455.8,5111.8
XS Rating Curve= 0 ,0
Exp/Cntr=0.3,0.1

Type RM Length L Ch R = 1 ,5322    ,412,412,412
BEGIN DESCRIPTION:
Mapping XS 6f6e1880
END DESCRIPTION:
XS GIS Cut Line= 3
      3659950.41     10619718.18      3660484.25     10619579.29
      3661243.82     10619212.53
#Sta/Elev= 30
    4186  354.05  4239.8   349.7  4275.2  341.44  4315.7  337.01  4494.2   324.1
  4553.7     323  4599.4  327.02  4675.2  325.65  4704.2  318.42  4787.7  308.03
  4793.3  309.72  4815.9   306.1  4854.6   305.2  4971.1   302.6  4973.9   302.1
  4977.1   302.6  5083.7  304.56  5109.7  303.95  5115.3  306.13  5176.6  310.89
  5211.9  318.68  5287.7  333.02  5318.7  341.44  5369.5   346.5  5386.5  342.46
  5392.1  344.92    5421  338.46  5437.3  338.88  5459.9  335.54  5581.1  338.13
#Mann= 7 ,-1 , 0
    4186     .16       0  4494.2     .05       0  4704.2     .16       0
  4971.1     .07       0  4977.1     .16       0  5083.7     .12       0
  5211.9     .05       0
Bank Sta=4854.6,5115.3
XS Rating Curve= 0 ,0
Exp/Cntr=0.3,0.1

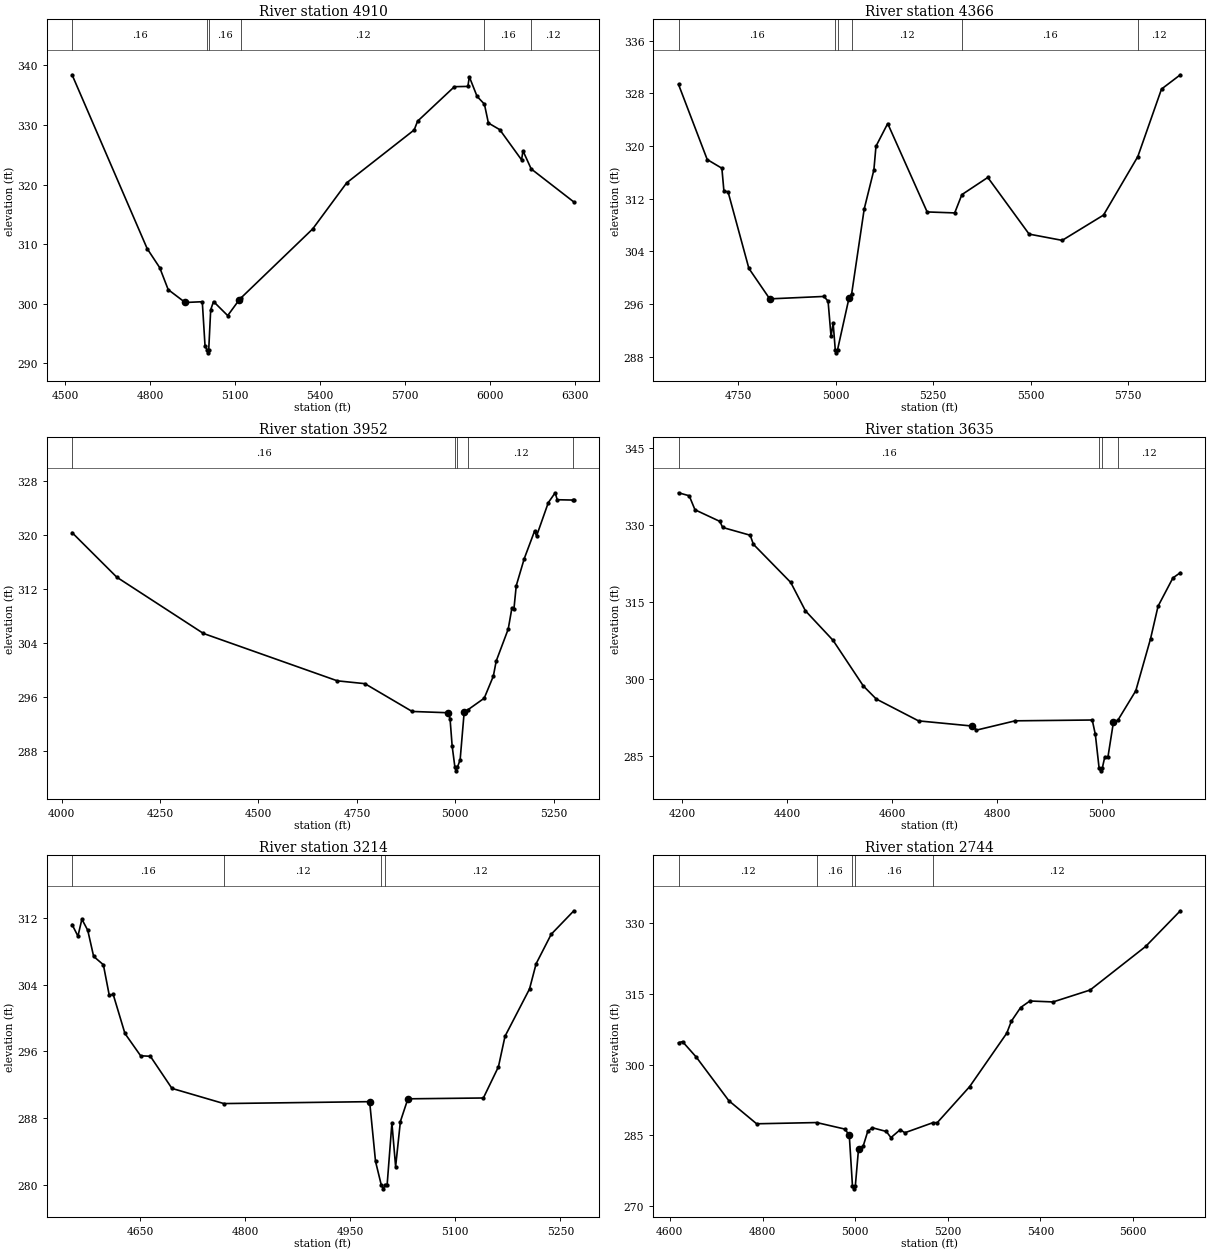
Type RM Length L Ch R = 1 ,4910    ,544,544,544
BEGIN DESCRIPTION:
UNT 0424 IN LACR 11.0
END DESCRIPTION:
XS GIS Cut Line= 2
      3660210.37     10619859.27      3661981.19     10619765.52
#Sta/Elev= 30
  4524.2  338.42  4789.7  309.23  4833.9  306.05  4863.9  302.36    4924   300.2
  4984.4  300.33  4994.1   292.9  5001.1  292.25  5003.9  291.75  5007.1  292.25
  5014.1  298.98  5024.1  300.36  5074.2     298  5114.3  300.61  5121.7  300.99
  5374.6  312.55  5494.8  320.29  5733.2  329.16  5745.2  330.63  5875.3  336.42
    5923  336.47    5928  338.09  5955.4   334.8  5981.4  333.49  5995.5  330.32
  6035.6  329.21  6112.7  324.14  6117.7  325.65  6146.7  322.62  6297.5  317.07
#Mann= 6 ,-1 , 0
  4524.2     .16       0  5001.1     .07       0  5007.1     .16       0
  5121.7     .12       0  5981.4     .16       0  6146.7     .12       0
Bank Sta=4924,5114.3
XS Rating Curve= 0 ,0
Exp/Cntr=0.3,0.1

Type RM Length L Ch R = 1 ,4366    ,414,414,414
BEGIN DESCRIPTION:
UNT 0424 IN LACR 10.0
END DESCRIPTION:
XS GIS Cut Line= 3
       3660220.8     10620145.75      3660811.91     10620369.69
      3661264.81     10620843.42
#Sta/Elev= 30
  4596.5  329.37  4670.1  317.96  4707.7  316.64    4713  313.14  4723.5  313.07
    4777  301.42  4830.5  296.79  4969.5  297.16  4980.2  296.44  4987.8  291.09
  4993.2  293.11  4998.6  289.09  5001.3  288.59  5004.6  289.09  5033.7  296.86
  5040.8  297.59  5072.9  310.45  5097.7  316.37  5103.1  319.98  5133.2  323.43
  5234.4     310  5305.1  309.85  5323.5  312.63    5390  315.24    5496  306.63
  5580.9  305.68  5686.9  309.52    5775  318.42  5835.7  328.67    5884  330.84
#Mann= 6 ,-1 , 0
  4596.5     .16       0  4998.6     .07       0  5004.6     .16       0
  5040.8     .12       0  5323.5     .16       0    5775     .12       0
Bank Sta=4830.5,5033.7
XS Rating Curve= 0 ,0
Exp/Cntr=0.3,0.1

Type RM Length L Ch R = 1 ,3952    ,317,317,317
BEGIN DESCRIPTION:
UNT 0424 IN LACR 9.0
END DESCRIPTION:
XS GIS Cut Line= 3
      3659625.99     10620626.26      3660502.72     10620630.61
      3660893.38     10620556.82
#Sta/Elev= 30
  4026.6  320.38  4140.2  313.77  4360.2  305.43  4700.2  298.41  4770.2  297.99
  4890.2  293.87  4981.4  293.68  4986.5  292.79  4991.8  288.76  4998.9  285.57
  5001.7  285.07  5004.9  285.57  5012.1   286.7  5022.3  293.74  5032.6  294.15
  5073.2  295.83  5096.4   299.1  5103.7  301.34  5134.2  306.08  5143.7  309.24
  5148.8  309.11  5154.6  312.51  5174.9  316.52  5201.1   320.6  5206.2  319.88
    5236  324.82  5253.5  326.28  5258.6  325.25  5298.9   325.2  5300.9   325.2
#Mann= 5 ,-1 , 0
  4026.6     .16       0  4998.9     .07       0  5004.9     .16       0
  5032.6     .12       0  5298.9     .16       0
Bank Sta=4981.4,5022.3
XS Rating Curve= 0 ,0
Exp/Cntr=0.3,0.1

Type RM Length L Ch R = 1 ,3635    ,421,421,421
BEGIN DESCRIPTION:
UNT 0424 IN LACR 8.0
END DESCRIPTION:
XS GIS Cut Line= 3
      3659949.66     10621010.18      3660749.61     10620860.19
       3660849.6      10620760.2
#Sta/Elev= 30
  4193.7  336.34    4214  335.76    4225  333.03  4272.5  330.76  4277.6  329.59
  4330.2  328.07  4336.1  326.32  4407.3  318.88  4435.3  313.35  4487.9   307.6
  4545.5  298.72  4570.1  296.18  4650.6  291.92  4753.2  290.91  4760.9  290.12
  4834.6  291.93  4981.3  292.09  4987.2  289.28  4994.4  282.69  4997.2  282.19
  5000.4  282.69    5005  284.82  5011.1  284.82  5021.7   291.7    5030  292.03
  5064.2  297.78  5092.4  307.95  5106.6  314.25  5134.9  319.76    5149  320.78
#Mann= 4 ,-1 , 0
  4193.7     .16       0  4994.4     .07       0  5000.4     .16       0
    5030     .12       0
Bank Sta=4753.2,5021.7
XS Rating Curve= 0 ,0
Exp/Cntr=0.3,0.1

Type RM Length L Ch R = 1 ,3214    ,470,470,470
BEGIN DESCRIPTION:
UNT 0424 IN LACR 7.0
END DESCRIPTION:
XS GIS Cut Line= 3
      3660249.59     10621010.18      3660649.61     10621210.19
      3660899.61     10621110.19
#Sta/Elev= 30
  4552.8  311.21  4561.2  309.82  4566.8  311.85  4575.2  310.52  4583.6  307.39
  4597.5  306.39  4605.9  302.73  4611.5  302.84  4628.3  298.15  4650.7  295.48
  4664.6  295.42  4695.4  291.57  4769.5  289.75  4977.7  289.98  4986.1  282.82
  4994.2  280.03    4997  279.53  5000.2  280.03  5002.7  280.03  5009.5  287.41
  5014.8  282.19  5021.6   287.6  5032.3  290.32  5140.1  290.42  5161.6  294.16
    5171  297.82    5206  303.49  5215.4  306.51    5237  310.05  5269.3  312.86
#Mann= 4 ,-1 , 0
  4552.8     .16       0  4769.5     .12       0  4994.2     .07       0
  5000.2     .12       0
Bank Sta=4977.7,5032.3
XS Rating Curve= 0 ,0
Exp/Cntr=0.3,0.1

Type RM Length L Ch R = 1 ,2744    ,571,571,571
BEGIN DESCRIPTION:
UNT 0424 IN LACR 6.0
END DESCRIPTION:
XS GIS Cut Line= 2
      3660291.06     10621559.79      3661374.43     10621567.61
#Sta/Elev= 30
  4618.7  304.65  4627.3  304.89  4657.3  301.57  4727.3  292.37  4787.3  287.48
    4917  287.74  4977.3  286.37  4987.3  285.13  4994.3   274.2    4997   273.7
  5000.3   274.2  5007.3  282.13  5017.3  282.73  5027.3   285.9  5037.3  286.64
  5067.3  285.85  5077.3  284.55  5097.3  286.23  5107.3  285.58  5168.1  287.72
  5177.3  287.72  5247.3  295.36  5327.3  306.66  5337.3  309.21  5357.3  312.11
  5377.3  313.49  5427.3  313.29  5507.3  315.81  5627.3  325.05  5702.1   332.6
#Mann= 5 ,-1 , 0
  4618.7     .12       0    4917     .16       0  4994.3     .07       0
  5000.3     .16       0  5168.1     .12       0
Bank Sta=4987.3,5007.3
XS Rating Curve= 0 ,0
Exp/Cntr=0.3,0.1

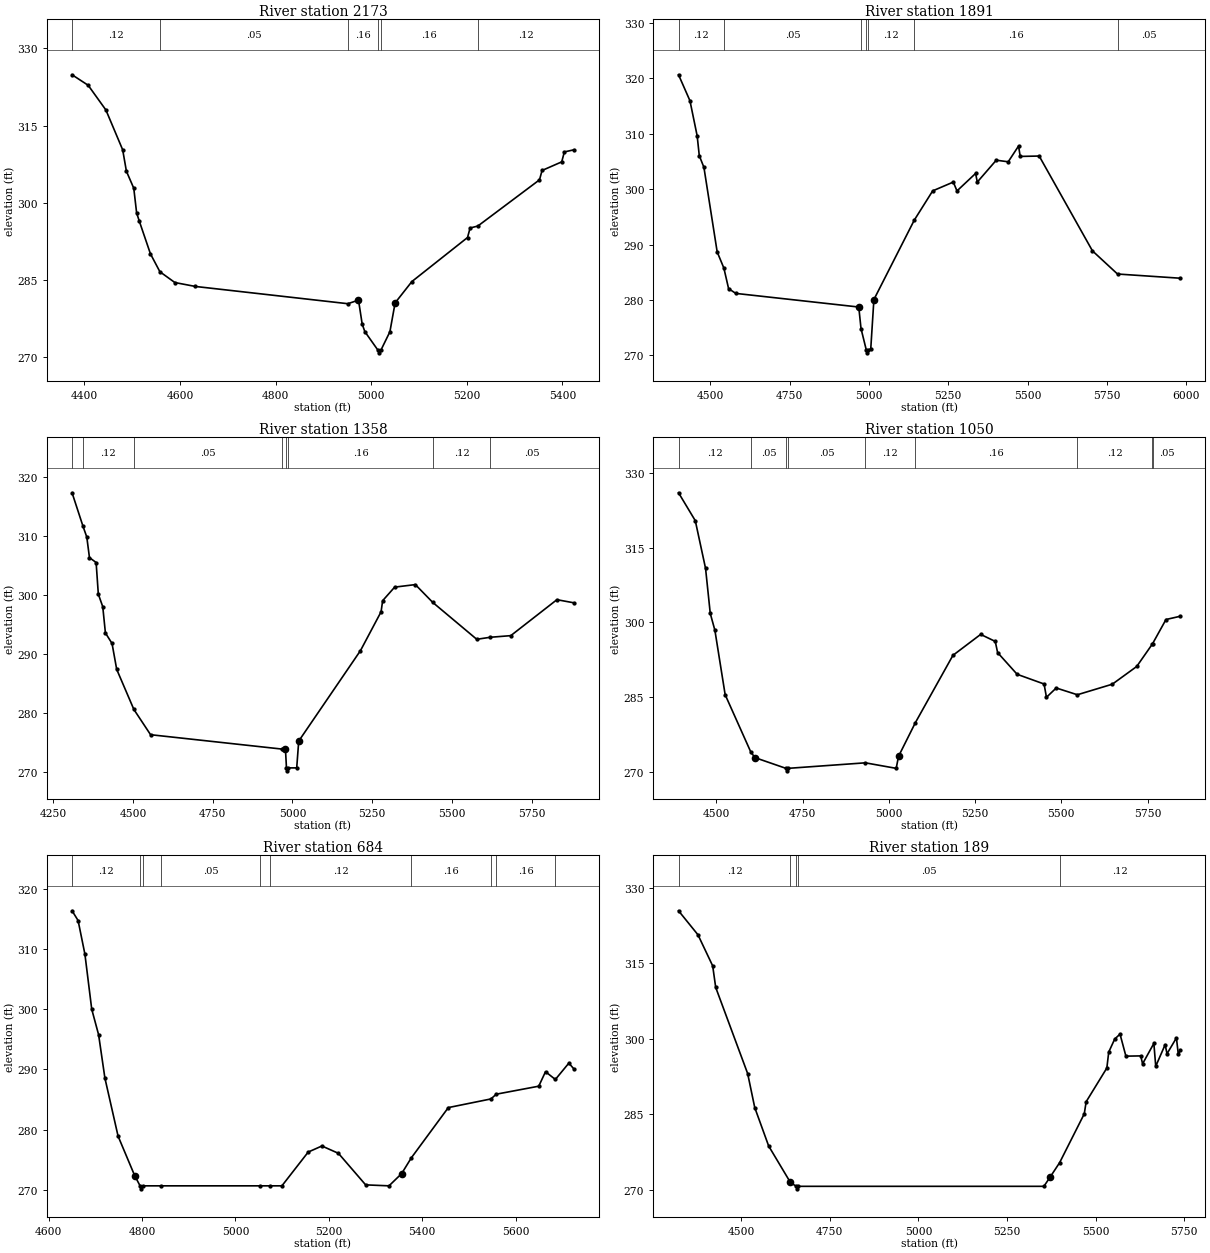
Type RM Length L Ch R = 1 ,2173    ,282,282,282
BEGIN DESCRIPTION:
UNT 0424 IN LACR 5.0
END DESCRIPTION:
XS GIS Cut Line= 3
      3660268.38     10621776.45      3660702.38     10622032.51
      3661201.49     10622253.86
#Sta/Elev= 30
  4374.1  324.89  4407.8  322.85  4444.9  318.05    4480  310.32  4487.8  306.16
  4503.2  302.86  4509.2  298.05    4515  296.41  4538.1  290.12  4557.9  286.64
  4589.2  284.55  4632.1  283.79  4951.1  280.44  4973.4  281.14  4981.1  276.49
  4986.6  275.03  5014.2   271.4  5016.9   270.9  5020.2   271.4  5039.1  274.99
    5050   280.6  5085.1  284.74  5201.5  293.29  5206.9  295.14  5223.1  295.52
  5352.1  304.49  5357.5  306.31  5398.6  307.98  5404.1  309.91    5424  310.32
#Mann= 6 ,-1 , 0
  4374.1     .12       0  4557.9     .05       0  4951.1     .16       0
  5014.2     .07       0  5020.2     .16       0  5223.1     .12       0
Bank Sta=4973.4,5050
XS Rating Curve= 0 ,0
Exp/Cntr=0.3,0.1

Type RM Length L Ch R = 1 ,1891    ,533,533,533
BEGIN DESCRIPTION:
UNT 0424 IN LACR 4.0
END DESCRIPTION:
XS GIS Cut Line= 3
       3660192.1     10621976.45      3660634.82     10622299.38
      3661621.81     10622606.67
#Sta/Elev= 30
    4400  320.65    4436  315.96  4458.8   309.6  4465.4  306.04    4480  303.94
  4521.8  288.67  4542.9  285.75  4557.8  282.04  4580.5  281.18  4968.1  278.72
  4975.2  274.83  4991.9  270.95  4994.6  270.45  4997.9  270.95  5005.9  271.16
  5015.8  280.07  5143.1  294.41  5201.1  299.69  5266.1  301.28  5277.7  299.68
  5336.4  302.84  5341.7  301.28  5401.5  305.23  5439.2  304.94  5471.8  307.79
    5477  305.91  5536.8  305.98  5704.7  288.86  5783.7  284.68  5981.7  283.92
#Mann= 7 ,-1 , 0
    4400     .12       0  4542.9     .05       0  4975.2     .12       0
  4991.9     .07       0  4997.9     .12       0  5143.1     .16       0
  5783.7     .05       0
Bank Sta=4968.1,5015.8
XS Rating Curve= 0 ,0
Exp/Cntr=0.3,0.1

Type RM Length L Ch R = 1 ,1358    ,308,308,308
BEGIN DESCRIPTION:
UNT 0424 IN LACR 3.0
END DESCRIPTION:
XS GIS Cut Line= 3
      3659923.86     10622260.29      3660702.53     10622846.25
      3661054.08      10623330.6
#Sta/Elev= 30
  4309.3  317.32  4343.6  311.63  4355.5   309.8  4363.8  306.32  4384.7  305.49
  4391.6  300.12  4405.5  297.99  4413.8  293.54  4434.6  291.75  4449.2  287.36
    4503  280.56  4555.4  276.27  4967.7  273.83  4978.1  273.92  4981.4  270.64
  4984.1  270.14  4987.4  270.64  5013.5  270.64  5019.8  275.19  5213.4  290.54
    5278  297.13  5282.9  299.01  5320.5  301.31  5385.4  301.74  5440.1  298.71
  5577.9  292.46  5619.8   292.8  5684.6  293.08  5829.2  299.18  5882.3  298.65
#Mann= 8 ,-1 , 0
  4309.3     .16       0  4343.6     .12       0    4503     .05       0
  4967.7     .16       0  4981.4     .07       0  4987.4     .16       0
  5440.1     .12       0  5619.8     .05       0
Bank Sta=4978.1,5019.8
XS Rating Curve= 0 ,0
Exp/Cntr=0.3,0.1

Type RM Length L Ch R = 1 ,1050    ,366,366,366
BEGIN DESCRIPTION:
UNT 0424 IN LACR 2.0
END DESCRIPTION:
XS GIS Cut Line= 3
      3659733.81     10622518.14      3660457.74     10623015.52
      3660875.84     10623412.84
#Sta/Elev= 30
    4390  326.02  4438.6  320.41  4468.4  310.81    4482  301.77  4495.4   298.4
  4525.2  285.44  4599.9  273.87  4611.9  272.79  4701.5  270.64  4704.3  270.14
  4707.5  270.64  4931.7  271.75  5021.2  270.64  5027.9  273.05    5077  279.85
  5185.7  293.35  5266.1  297.56  5308.4  296.15  5315.3   293.9  5371.9  289.54
    5450  287.59  5456.9  284.92  5485.2  286.79  5546.5  285.43  5647.8  287.55
  5718.6  291.11    5764  295.62  5764.7   295.7  5803.5  300.55  5845.1  301.21
#Mann= 9 ,-1 , 0
    4390     .12       0  4599.9     .05       0  4701.5     .07       0
  4707.5     .05       0  4931.7     .12       0    5077     .16       0
  5546.5     .12       0    5764     .16       0  5764.7     .05       0
Bank Sta=4611.9,5027.9
XS Rating Curve= 0 ,0
Exp/Cntr=0.3,0.1

Type RM Length L Ch R = 1 ,684     ,495,495,495
BEGIN DESCRIPTION:
Mapping XS c603118b
END DESCRIPTION:
XS GIS Cut Line= 3
      3659687.82     10622703.67      3660010.77      10623141.2
      3660330.23     10623564.84
#Sta/Elev= 30
  4650.1  316.41    4663  314.79  4677.6  309.19  4692.2  300.03  4706.9  295.79
  4720.4  288.57  4748.6  278.91  4784.1  272.35  4795.7  270.64  4798.4  270.14
  4801.7  270.64  4841.4  270.64  5053.4  270.64  5074.1  270.64  5099.4  270.64
  5155.7  276.26    5185  277.27  5220.4  276.05  5278.7   270.8  5328.7  270.64
  5355.7  272.67  5376.5   275.3  5455.7  283.66  5546.9   285.1  5558.4  285.89
  5649.3  287.22  5663.8  289.63  5684.9  288.34  5713.8  291.06  5724.5   290.1
#Mann= 10 ,-1 , 0
  4650.1     .12       0  4795.7    .035       0  4801.7     .12       0
  4841.4     .05       0  5053.4     .07       0  5074.1     .12       0
  5376.5     .16       0  5546.9     .12       0  5558.4     .16       0
  5684.9     .12       0
Bank Sta=4784.1,5355.7
XS Rating Curve= 0 ,0
Exp/Cntr=0.3,0.1

Type RM Length L Ch R = 1 ,189     ,0,0,0
BEGIN DESCRIPTION:
UNT 0424 IN LACR 1.0
END DESCRIPTION:
XS GIS Cut Line= 4
      3659580.21     10622665.47      3659542.02     10623297.45
      3659667.02     10623418.98      3660245.62     10623608.42
#Sta/Elev= 30
    4323   325.4  4377.8  320.63  4419.4  314.45  4427.9  310.17  4518.1  293.05
  4538.1  286.29  4577.4  278.65  4638.8  271.41  4655.3  270.64  4658.1  270.14
  4661.3  270.64  5354.2  270.64  5372.7  272.57  5398.6  275.34  5468.2  285.05
  5473.5  287.45  5531.9  294.15  5537.2  297.32  5554.1  299.91  5569.1  300.89
  5585.7  296.51  5627.5  296.56  5632.8  294.99  5664.6  299.04  5669.9   294.5
  5696.5   298.8  5701.7  296.98  5728.3  300.14  5733.6  296.86  5739.3  297.71
#Mann= 5 ,-1 , 0
    4323     .12       0  4638.8     .05       0  4655.3    .033       0
  4661.3     .05       0  5398.6     .12       0
Bank Sta=4638.8,5372.7
XS Rating Curve= 0 ,0
Exp/Cntr=0.3,0.1

Chan Stop Cuts=-1
Use User Specified Reach Order=0
Composite Channel Slope=5