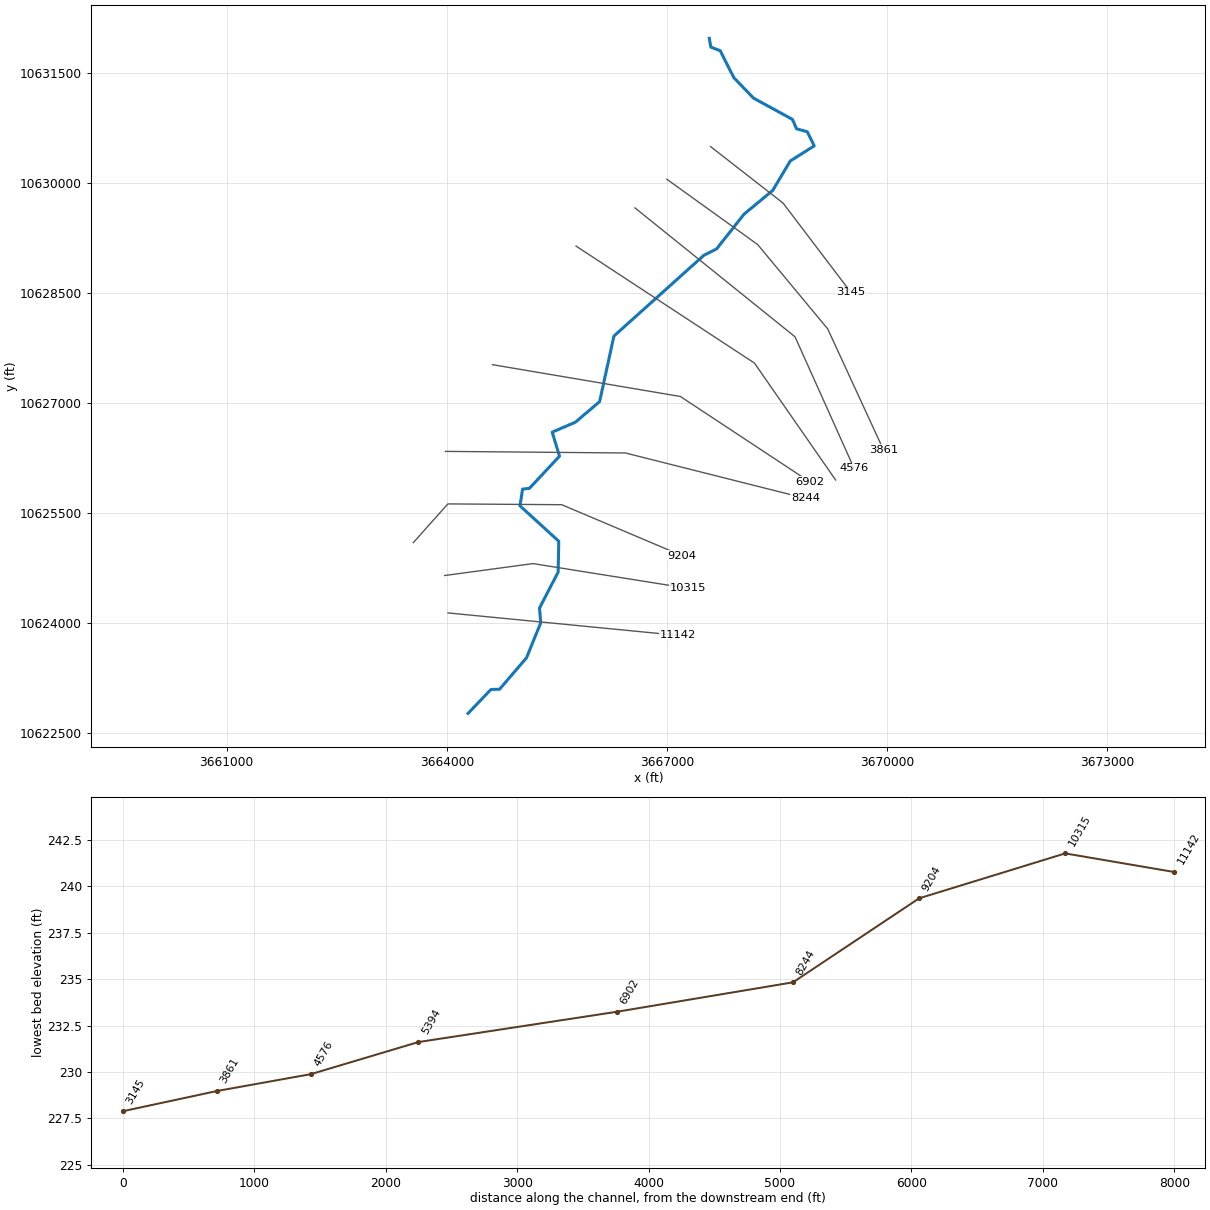
--- UNT 0425 IN LACR.prj (project) ---

Proj Title=UNT 0425 IN LACR Base Level Engineering
Current Plan=p01
Default Exp/Contr=0.3,0.1
English Units
Geom File=g01
Flow File=f01
Plan File=p01
Y Axis Title=Elevation
X Axis Title(PF)=Main Channel Distance
X Axis Title(XS)=Station
BEGIN DESCRIPTION:
UNT 0425 IN LACR
END DESCRIPTION:
DSS Export Rating Curves= 0
DSS Export Rating Curve Sorted= 0
DSS Export Volume Flow Curves= 0
DXF OffsetX= 0
DXF OffsetY= 0
DXF ScaleX= 1
DXF ScaleY= 10

--- UNT 0425 IN LACR.p01 (plan) ---

Plan Title=Multiple Run
Short Identifier=Multiple
Geom File=g01
Flow File=f01
Subcritical Flow
K Sum by GR= 0
Std Step Tol= 0.01
Critical Tol= 0.01
Num of Std Step Trials= 20
Max Error Tol= 0.3
Flow Tol Ratio= 0.001
Split Flow NTrial= 30
Split Flow Tol= 0.02
Split Flow Ratio= 0.02
Log Output Level= 0
Friction Slope Method= 1
Unsteady Friction Slope Method= 2
Unsteady Bridges Friction Slope Method= 1
Parabolic Critical Depth
Global Vel Dist=  1 , 1 , 1
Global Log Level= 0
CheckData=True
Encroach Param= -1, 0, 0, 0
BEGIN DESCRIPTION:
Multiple Run
END DESCRIPTION:

--- UNT 0425 IN LACR.f01 (steady flow) ---

Flow Title=Multiple
Program Version=4.10
Number of Profiles= 7
Profile Names=10-year,25-year,50-year,1pct_min,100-year,1pct_plu,500-year
River Rch & RM=UNT 0425 IN LACR,Reach-1         ,11142
     560     762     931     836    1131    1529    1675
River Rch & RM=UNT 0425 IN LACR,Reach-1         ,9204
     811    1118    1375    1241    1679    2271    2515
Boundary for River Rch & Prof#=UNT 0425 IN LACR,Reach-1         , 1
Up Type= 0
Dn Type= 3
Dn Slope=0.005
Boundary for River Rch & Prof#=UNT 0425 IN LACR,Reach-1         , 2
Up Type= 0
Dn Type= 3
Dn Slope=0.005
Boundary for River Rch & Prof#=UNT 0425 IN LACR,Reach-1         , 3
Up Type= 0
Dn Type= 3
Dn Slope=0.005
Boundary for River Rch & Prof#=UNT 0425 IN LACR,Reach-1         , 4
Up Type= 0
Dn Type= 3
Dn Slope=0.005
Boundary for River Rch & Prof#=UNT 0425 IN LACR,Reach-1         , 5
Up Type= 0
Dn Type= 3
Dn Slope=0.005
Boundary for River Rch & Prof#=UNT 0425 IN LACR,Reach-1         , 6
Up Type= 0
Dn Type= 3
Dn Slope=0.005
Boundary for River Rch & Prof#=UNT 0425 IN LACR,Reach-1         , 7
Up Type= 0
Dn Type= 3
Dn Slope=0.005
DSS Import GetInterval= 0
DSS Import GetPeak= 0
DSS Import FillOption= 0

--- UNT 0425 IN LACR.g01 (geometry) ---

Geom Title=Existing Conditions
Program Version=4.10

River Reach=UNT 0425 IN LACR,Reach-1
Reach XY= 30
      3664289.75       10622762.      3664601.25       10623088.
       3664718.5       10623091.      3665086.25       10623520.
       3665279.5       10623996.      3665263.25       10624199.
      3665517.25       10624688.      3665525.75       10625109.
      3664997.25       10625592.      3665032.75       10625820.
      3665125.75       10625831.       3665535.5       10626269.
       3665436.5       10626597.       3665751.5       10626732.
      3666082.25       10627013.        3666277.       10627907.
       3667502.5       10629008.      3667676.75       10629096.
        3668050.       10629569.        3668442.       10629894.
      3668679.75       10630294.      3669006.75       10630501.
       3668911.5       10630693.      3668765.75       10630734.
      3668709.75       10630862.      3668180.75       10631151.
       3667912.5       10631429.        3667725.       10631799.
        3667598.       10631847.       3667577.5       10631967.

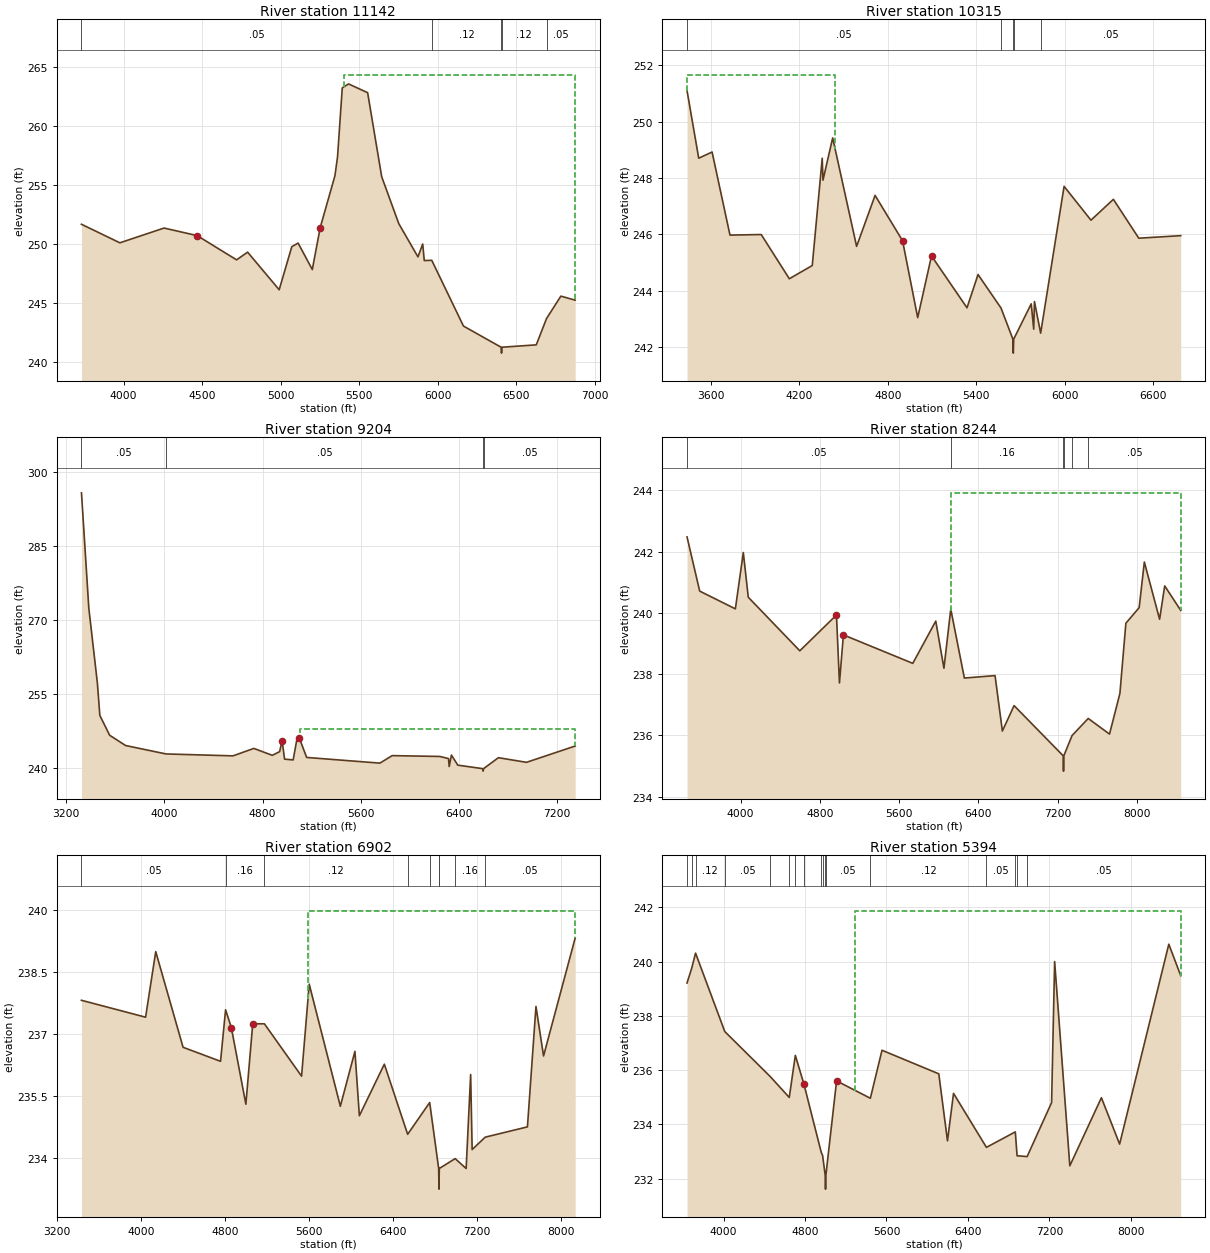
Type RM Length L Ch R = 1 ,11142   ,827,827,827
BEGIN DESCRIPTION:
UNT 0425 IN LACR 6.0
END DESCRIPTION:
XS GIS Cut Line= 2
       3664016.1     10624131.81      3667146.34     10623826.42
#Sta/Elev= 30
  3731.6  251.68  3976.3  250.11  4257.6  251.36  4468.6  250.72  4719.8  248.67
  4790.1  249.32  4991.1  246.14  5071.4  249.78  5111.6  250.09  5202.1  247.85
  5252.3  251.39  5346.2  255.78  5362.8  257.37    5393  263.22  5433.2  263.55
  5554.6  262.81  5644.1   255.7  5753.1  251.73  5875.2  248.92  5905.4  250.01
  5915.4  248.61  5963.1  248.63    6165  243.07  6404.8  241.28  6407.5  240.78
  6410.8  241.28  6628.8  241.48  6694.5  243.71  6785.5   245.6  6876.7  245.26
#Mann= 5 ,-1 , 0
  3731.6     .05       0  5963.1     .12       0  6404.8     .03       0
  6410.8     .12       0  6694.5     .05       0
#XS Ineff= 2 , 0
                         5402.63          264.32
Permanent Ineff=
       F       F
Bank Sta=4468.6,5252.3
XS Rating Curve= 0 ,0
Exp/Cntr=0.3,0.1

Type RM Length L Ch R = 1 ,10315   ,1111,1111,1111
BEGIN DESCRIPTION:
UNT 0425 IN LACR 5.0
END DESCRIPTION:
XS GIS Cut Line= 3
      3663971.02     10624641.79       3665175.4     10624804.55
      3667280.46     10624468.17
#Sta/Elev= 30
  3438.9   251.1  3518.2   248.7  3608.8  248.92  3730.1  245.97    3942  245.99
  4132.5  244.42  4287.9  244.89  4355.5   248.7  4360.6  247.92  4426.4  249.42
  4588.6  245.57  4713.9  247.38  4900.1  245.77  5002.8  243.04  5096.4  245.23
    5337  243.39  5411.8  244.57  5567.7  243.38  5647.9  242.28  5650.7  241.78
  5653.9  242.28  5772.4  243.53  5789.3  242.63  5794.3  243.61  5836.4  242.49
  5995.2   247.7  6177.5   246.5  6329.4  247.24  6501.6  245.86    6786  245.95
#Mann= 5 ,-1 , 0
  3438.9     .05       0  5567.7     .12       0  5647.9     .04       0
  5653.9     .12       0  5836.4     .05       0
#XS Ineff= 2 , 0
         4443.25  251.66
Permanent Ineff=
       F       F
Bank Sta=4900.1,5096.4
XS Rating Curve= 0 ,0
Exp/Cntr=0.3,0.1

Type RM Length L Ch R = 1 ,9204    ,960,960,960
BEGIN DESCRIPTION:
Mapping XS 0d41e723
END DESCRIPTION:
XS GIS Cut Line= 4
     3663543.143    10625089.809       3664014.4     10625618.35
      3665566.02      10625607.5      3667204.47     10624913.06
#Sta/Elev= 30
3325.904 295.7133385.739272.34623455.545257.1588 3475.49250.63753555.269246.6231
3684.911244.5466  4014.1  242.84  4559.3  242.45  4729.3  243.96  4879.3  242.56
  4939.3  243.31  4959.3  245.53  4979.3  241.79  5049.3  241.63  5079.3  245.73
  5099.3  246.06  5159.3  242.13  5755.4  240.98  5855.5   242.5  6243.2  242.33
  6314.2   241.9  6319.7  240.29  6337.9  242.61  6389.7  240.57  6593.4  239.86
  6596.1  239.36  6599.4  239.86  6720.2  242.08    6949  241.14  7345.3  244.44
#Mann= 4 ,-1 , 0
3325.904     .05       0  4014.1     .05       0  6593.4     .03       0
  6599.4     .05       0
#XS Ineff= 2 , 0
                         5108.12          247.89
Permanent Ineff=
       F       F
Bank Sta=4959.3,5099.3
XS Rating Curve= 0 ,0
Exp/Cntr=0.3,0.1

Type RM Length L Ch R = 1 ,8244    ,1342,1342,1342
BEGIN DESCRIPTION:
Mapping XS 90c91e48
END DESCRIPTION:
XS GIS Cut Line= 3
      3663981.78      10626334.5      3666434.08      10626312.8
      3668886.29     10625694.32
#Sta/Elev= 30
  3459.9  242.48  3587.7  240.71  3947.7  240.13  4027.8  241.97  4077.8  240.51
  4597.8  238.76  4967.8  239.93  4997.8  237.71  5037.8  239.28  5737.8  238.35
  5969.6  239.73  6052.1  238.19    6121  240.12  6258.3  237.87  6567.7  237.95
  6641.8  236.14  6759.9  236.97  7255.7  235.33  7258.5  234.83  7261.7  235.33
  7344.6  235.99  7507.8  236.55  7722.8  236.04  7827.7  237.37  7887.8  239.66
  8021.9  240.17  8074.2  241.66  8228.1  239.79  8279.7  240.88  8441.3  240.08
#Mann= 6 ,-1 , 0
  3459.9     .05       0    6121     .16       0  7255.7     .03       0
  7261.7     .16       0  7344.6     .16       0  7507.8     .05       0
#XS Ineff= 2 , 0
                         6125.45          243.92
Permanent Ineff=
       F       F
Bank Sta=4967.8,5037.8
XS Rating Curve= 0 ,0
Exp/Cntr=0.3,0.1

Type RM Length L Ch R = 1 ,6902    ,1508,1508,1508
BEGIN DESCRIPTION:
Mapping XS f901fba4
END DESCRIPTION:
XS GIS Cut Line= 3
      3664621.96     10627517.23      3667182.77     10627083.19
      3668940.62     10625922.15
#Sta/Elev= 30
  3429.9  237.82  4040.8  237.41  4137.5     239  4397.9  236.68  4754.9  236.34
  4803.1  237.59  4857.6  237.16  4996.3   235.3  5061.7  237.25  5172.8  237.25
    5527  235.98  5599.8  238.21  5896.4  235.25  6035.4  236.58  6077.7  235.02
  6315.5  236.27  6537.8  234.57  6747.6  235.34  6833.3  233.74    6836  233.24
  6839.3  233.74  6990.4  233.98  7095.1  233.74    7138  236.02  7152.3   234.2
  7276.5   234.5    7679  234.75  7760.3  237.67  7832.6  236.47  8133.9  239.33
#Mann= 9 ,-1 , 0
  3429.9     .05       0  4803.1     .16       0  5172.8     .12       0
  6537.8     .16       0  6747.6     .12       0  6833.3     .07       0
  6839.3     .12       0  6990.4     .16       0  7276.5     .05       0
#XS Ineff= 2 , 0
                         5587.81          239.99
Permanent Ineff=
       F       F
Bank Sta=4857.6,5061.7
XS Rating Curve= 0 ,0
Exp/Cntr=0.3,0.1

Type RM Length L Ch R = 1 ,5394    ,818,818,818
BEGIN DESCRIPTION:
UNT 0425 IN LACR 3.0
END DESCRIPTION:
XS GIS Cut Line= 3
      3665761.35     10629133.97      3668191.89     10627538.92
       3669298.2     10625944.53
#Sta/Elev= 30
  3641.5  239.21  3687.1  239.75  3725.3  240.31  4012.1  237.42  4458.6  235.76
  4645.3  234.99    4705  236.54  4790.1  235.47  4959.1  232.97  4972.8  232.85
  4998.6  232.11  5001.4  231.61  5004.6  232.11  5110.1   235.6  5441.7  234.96
  5556.1  236.73  6113.7  235.86  6199.1  233.39  6258.4  235.14  6581.5  233.15
  6864.9  233.72  6882.5  232.84  6981.1  232.81  7221.3   234.8  7251.1     240
  7400.3  232.47  7710.4  234.98  7889.3  233.27  8372.3  240.64  8489.3  239.48
#Mann= 17 ,-1 , 0
  3641.5     .12       0  3687.1     .16       0  3725.3     .12       0
  4012.1     .05       0  4458.6     .12       0  4645.3     .16       0
    4705     .05       0  4790.1     .16       0  4959.1     .12       0
  4972.8     .05       0  4998.6     .03       0  5004.6     .05       0
  5441.7     .12       0  6581.5     .05       0  6864.9     .16       0
  6882.5     .12       0  6981.1     .05       0
#XS Ineff= 2 , 0
                         5293.91          241.87
Permanent Ineff=
       F       F
Bank Sta=4790.1,5110.1
XS Rating Curve= 0 ,0
Exp/Cntr=0.3,0.1

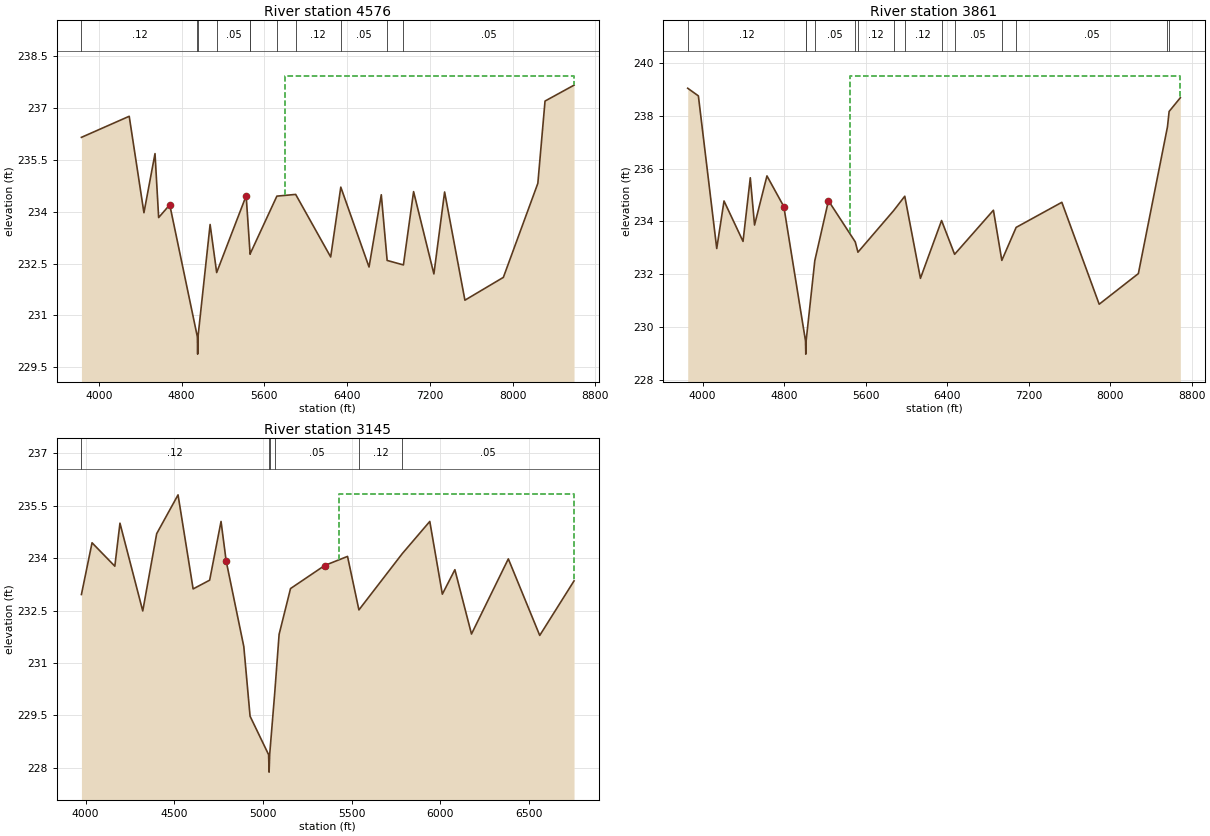
Type RM Length L Ch R = 1 ,4576    ,715,715,715
BEGIN DESCRIPTION:
Mapping XS 4bdd4ae2
END DESCRIPTION:
XS GIS Cut Line= 3
      3666564.32     10629654.78      3668745.27       10627897.
      3669548.22     10626106.64
#Sta/Elev= 30
  3831.5  236.15  4293.6  236.76    4436  233.97  4543.1  235.68  4578.3  233.83
  4685.5   234.2  4952.7  230.38  4955.4  229.88  4958.7  230.38  5075.8  233.63
  5139.3  232.24  5424.4  234.46  5462.7  232.77  5462.9  232.78  5721.5  234.45
  5903.1   234.5  6241.8  232.69  6339.6  234.71  6612.5   232.4    6731  234.49
  6787.7  232.59  6945.1  232.46  7043.3  234.58  7239.7   232.2  7343.3  234.57
  7539.7  231.44  7911.4   232.1  8244.8  234.82  8314.3   237.2  8594.8  237.66
#Mann= 11 ,-1 , 0
  3831.5     .12       0  4952.7     .07       0  4958.7     .12       0
  5139.3     .05       0  5462.7     .16       0  5462.9     .12       0
  5721.5     .07       0  5903.1     .12       0  6339.6     .05       0
  6787.7     .12       0  6945.1     .05       0
#XS Ineff= 2 , 0
                         5802.87          237.93
Permanent Ineff=
       F       F
Bank Sta=4685.5,5424.4
XS Rating Curve= 0 ,0
Exp/Cntr=0.3,0.1

Type RM Length L Ch R = 1 ,3861    ,716,716,716
BEGIN DESCRIPTION:
UNT 0425 IN LACR 2.0
END DESCRIPTION:
XS GIS Cut Line= 4
      3666998.35     10630045.41      3668235.29     10629155.68
      3669190.15      10628005.5      3669949.71     10626356.17
#Sta/Elev= 30
  3854.8  239.04  3959.5  238.75  4139.7  232.97  4211.1  234.77  4397.7  233.24
  4468.9  235.65  4510.7  233.86  4632.4  235.72  4797.9  234.56  5010.9  229.47
  5013.6  228.97  5016.9  229.47  5102.1  232.51    5236  234.78  5499.2  233.22
  5525.4  232.83  5876.8  234.41  5984.9  234.95  6138.7  231.84  6346.1  234.03
    6474  232.75  6854.9  234.42  6937.4  232.52    7078  233.77  7526.4  234.72
  7892.8  230.86  8277.4  232.02  8563.1  237.58  8579.2  238.16  8689.2  238.68
#Mann= 14 ,-1 , 0
  3854.8     .12       0  5010.9     .07       0  5016.9     .12       0
  5102.1     .05       0  5499.2     .16       0  5525.4     .12       0
  5876.8     .07       0  5984.9     .12       0  6346.1     .16       0
    6474     .05       0  6937.4     .12       0    7078     .05       0
  8563.1     .08       0  8579.2     .05       0
#XS Ineff= 2 , 0
                         5444.44          239.51
Permanent Ineff=
       F       F
Bank Sta=4797.9,5236
XS Rating Curve= 0 ,0
Exp/Cntr=0.3,0.1

Type RM Length L Ch R = 1 ,3145    ,0,0,0
BEGIN DESCRIPTION:
UNT 0425 IN LACR 1.0
END DESCRIPTION:
XS GIS Cut Line= 3
      3667595.11      10630490.3      3668582.51     10629719.91
      3669504.51     10628505.04
#Sta/Elev= 30
    3977  232.96  4036.9  234.44  4165.4  233.77  4194.3     235  4322.8  232.49
  4401.3   234.7  4521.8  235.81  4606.8  233.12    4700  233.37  4764.2  235.05
  4793.1  233.92  4892.6  231.47  4927.9  229.48  5032.4  228.38  5035.2  227.88
  5038.4  228.38  5067.3  230.17  5091.6  231.82  5155.9  233.13  5348.5  233.79
  5477.4  234.05  5541.6  232.52  5786.1  234.13  5941.2  235.05    6012  232.97
  6082.7  233.67  6176.3  231.83    6384  233.98  6561.1  231.79  6754.5  233.35
#Mann= 6 ,-1 , 0
    3977     .12       0  5032.4     .07       0  5038.4     .12       0
  5067.3     .05       0  5541.6     .12       0  5786.1     .05       0
#XS Ineff= 2 , 0
                         5427.72          235.84
Permanent Ineff=
       F       F
Bank Sta=4793.1,5348.5
XS Rating Curve= 0 ,0
Exp/Cntr=0.3,0.1

Chan Stop Cuts=-1
Use User Specified Reach Order=0
Composite Channel Slope=5