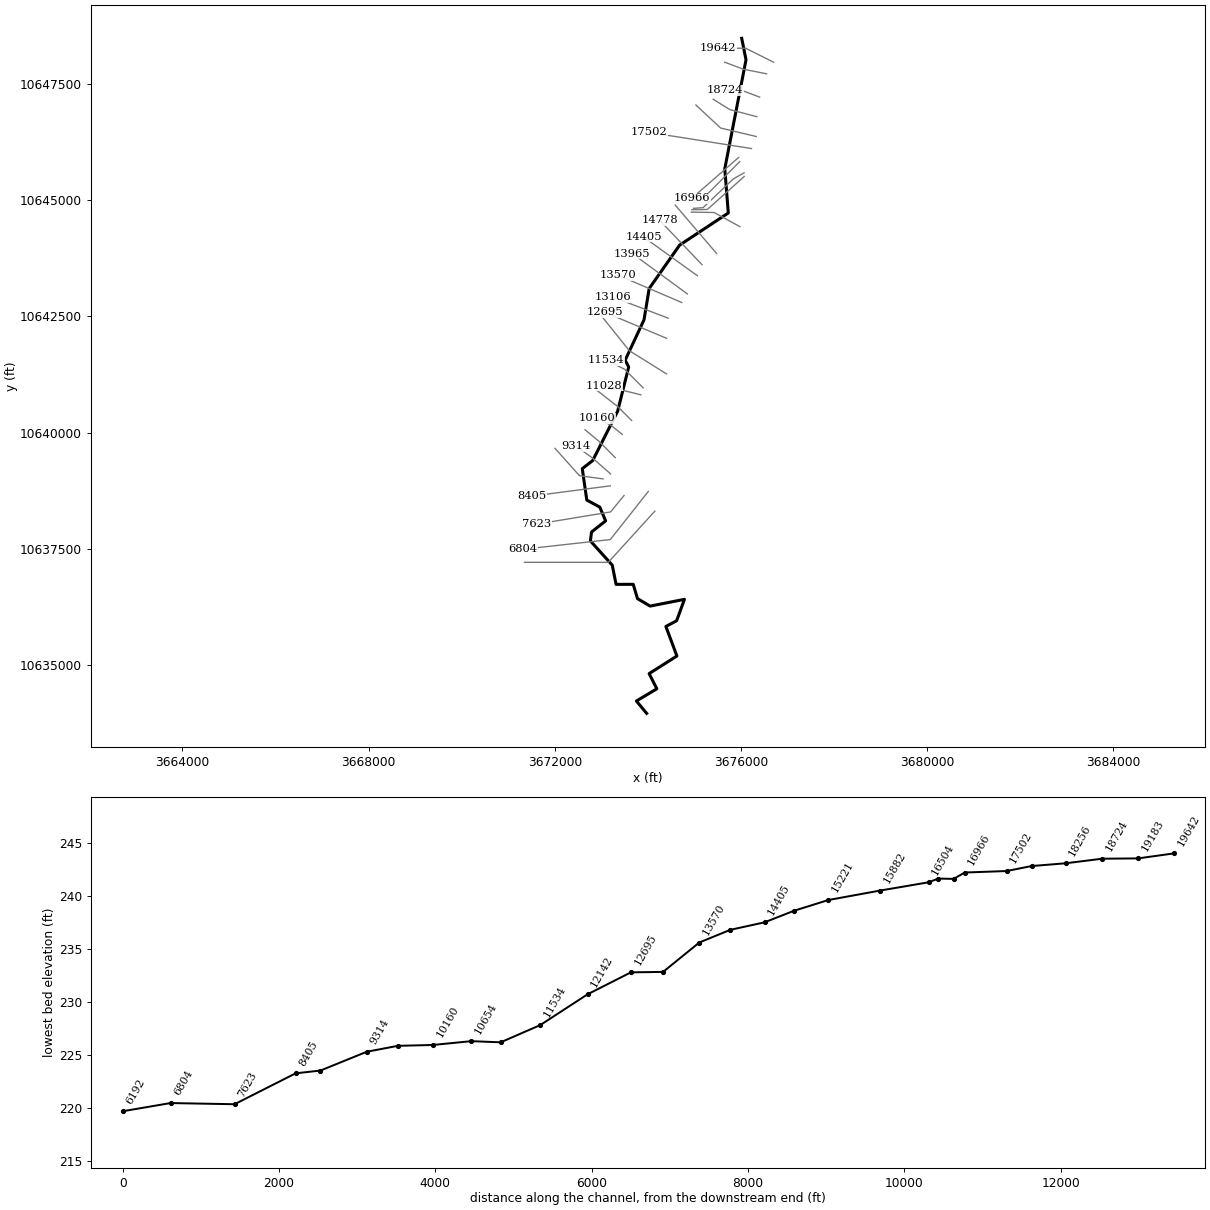
--- UNT 0426 IN LACR.prj (project) ---

Proj Title=UNT 0426 IN LACR Base Level Engineering
Current Plan=p01
Default Exp/Contr=0.3,0.1
English Units
Geom File=g01
Flow File=f01
Plan File=p01
BEGIN DESCRIPTION:
UNT 0426 IN LACR
END DESCRIPTION:

--- UNT 0426 IN LACR.p01 (plan) ---

Plan Title=Multiple Run
Short Identifier=Multiple
Geom File=g01
Flow File=f01
Subcritical Flow
K Sum by GR= 0
Std Step Tol= 0.01
Critical Tol= 0.01
Num of Std Step Trials= 20
Max Error Tol= 0.3
Flow Tol Ratio= 0.001
Split Flow NTrial= 30
Split Flow Tol= 0.02
Split Flow Ratio= 0.02
Log Output Level= 0
Friction Slope Method= 1
Unsteady Friction Slope Method= 2
Unsteady Bridges Friction Slope Method= 1
Parabolic Critical Depth
Global Vel Dist=  1 , 1 , 1
Global Log Level= 0
CheckData=True
Encroach Param= -1, 0, 0, 0
BEGIN DESCRIPTION:
Multiple Run
END DESCRIPTION:

--- UNT 0426 IN LACR.f01 (steady flow) ---

Flow Title=Multiple
Number of Profiles=7
Profile Names=10-year,25-year,50-year,1pct_min,100-year,1pct_plu,500-year
River Rch & RM= UNT 0426 IN LACR,Reach-1,19642
     554     735     880     772    1044    1412    1479
River Rch & RM= UNT 0426 IN LACR,Reach-1,13106
     863    1169    1419    1262    1707    2308    2482
River Rch & RM= UNT 0426 IN LACR,Reach-1,7623
    1063    1447    1763    1570    2124    2872    3100
Boundary for River Rch & Prof#=UNT 0426 IN LACR,Reach-1,1
Up Type=0
Dn Type=3
Dn Slope=0.005
Boundary for River Rch & Prof#=UNT 0426 IN LACR,Reach-1,2
Up Type=0
Dn Type=3
Dn Slope=0.005
Boundary for River Rch & Prof#=UNT 0426 IN LACR,Reach-1,3
Up Type=0
Dn Type=3
Dn Slope=0.005
Boundary for River Rch & Prof#=UNT 0426 IN LACR,Reach-1,4
Up Type=0
Dn Type=3
Dn Slope=0.005
Boundary for River Rch & Prof#=UNT 0426 IN LACR,Reach-1,5
Up Type=0
Dn Type=3
Dn Slope=0.005
Boundary for River Rch & Prof#=UNT 0426 IN LACR,Reach-1,6
Up Type=0
Dn Type=3
Dn Slope=0.005
Boundary for River Rch & Prof#=UNT 0426 IN LACR,Reach-1,7
Up Type=0
Dn Type=3
Dn Slope=0.005

--- UNT 0426 IN LACR.g01 (geometry) ---

Geom Title=Existing Conditions

River Reach=UNT 0426 IN LACR,Reach-1
Reach XY= 30
      3676015.50     10648473.00      3676108.00     10648011.00
      3675651.75     10645670.00      3675727.25     10644719.00
      3674681.25     10644028.00      3674027.75     10643095.00
      3673916.75     10642422.00      3673511.50     10641555.00
      3673587.75     10641410.00      3673350.75     10640459.00
      3672814.25     10639397.00      3672590.75     10639224.00
      3672687.50     10638548.00      3672967.00     10638397.00
      3673092.00     10638101.00      3672789.00     10637861.00
      3672765.00     10637670.00      3673234.50     10637149.00
      3673317.00     10636736.00      3673685.00     10636737.00
      3673776.25     10636430.00      3674047.00     10636269.00
      3674785.00     10636414.00      3674617.50     10635954.00
      3674386.25     10635831.00      3674623.50     10635196.00
      3674026.50     10634818.00      3674193.00     10634491.00
      3673753.00     10634229.00      3673973.50     10633963.00

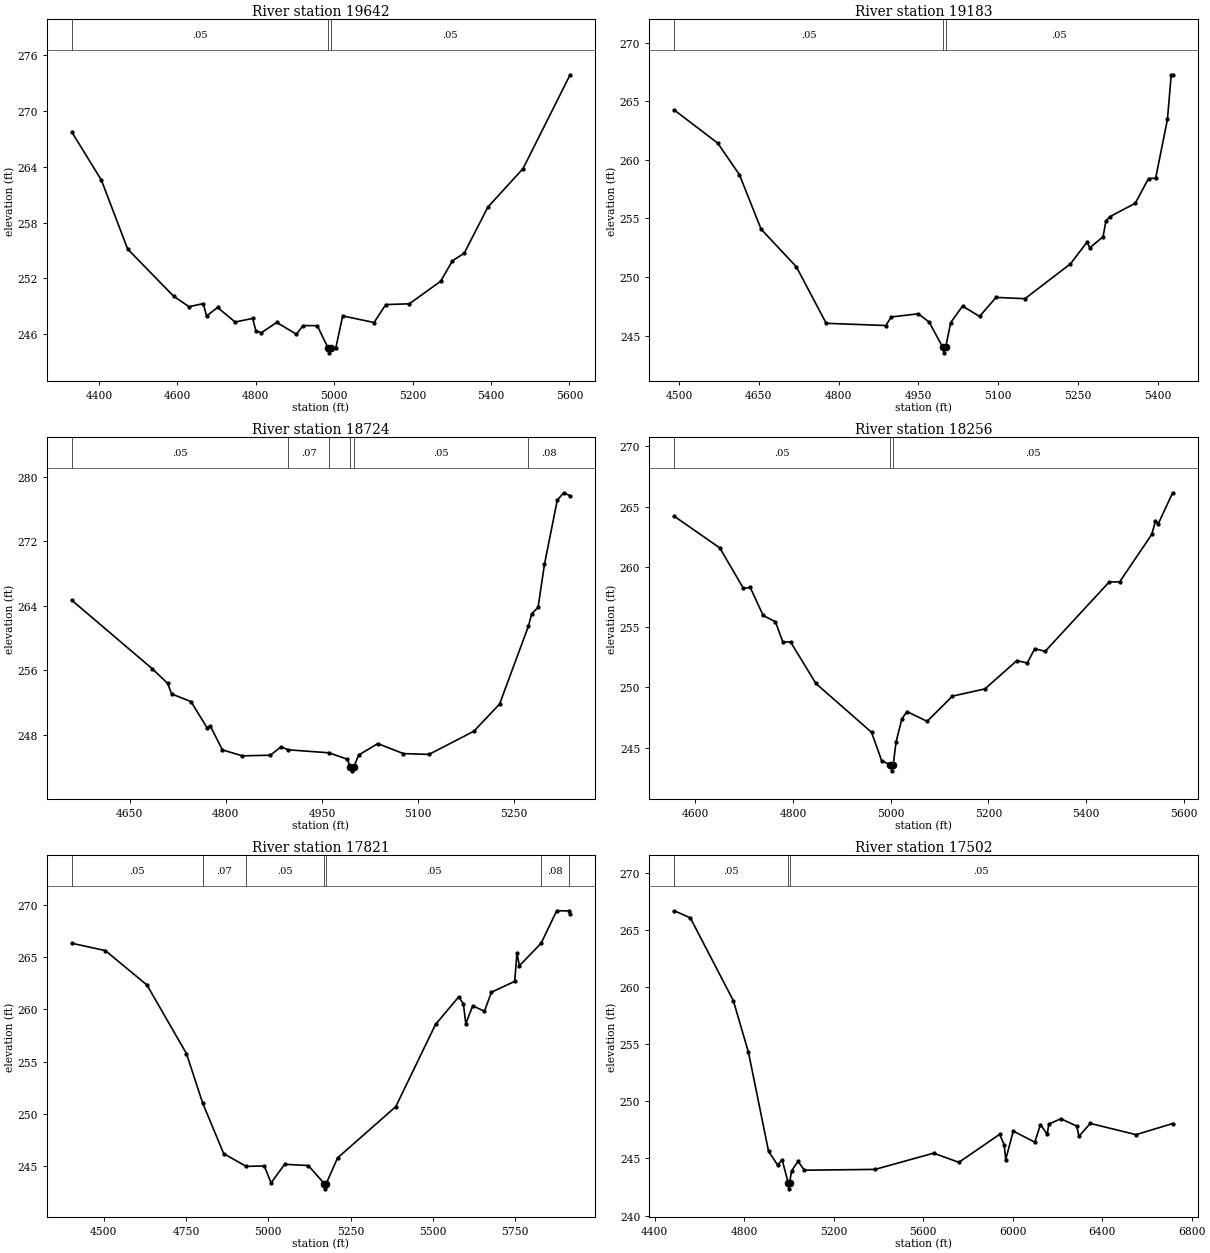
Type RM Length L Ch R = 1,19642,459,459,459
BEGIN DESCRIPTION:
UNT 0426 IN LACR 30.0
END DESCRIPTION:
XS GIS Cut Line= 3
      3676699.64     10647960.17      3676099.61     10648260.19
      3675499.57     10648260.19
#Sta/Elev= 30
  4330.7  267.74  4406.2  262.57  4473.3  255.15  4590.7  250.08  4629.8  248.96
  4666.1  249.29  4674.5  247.96  4702.5  248.88  4747.2  247.31  4791.9  247.70
  4800.3  246.36  4814.3  246.16  4853.4  247.27  4903.7  246.00  4920.5  246.93
  4956.8  246.92  4984.6  244.50  4987.3  244.00  4990.6  244.50  5004.1  244.53
  5021.6  247.97  5101.6  247.26  5131.6  249.19  5191.6  249.27  5271.6  251.70
  5301.6  253.90  5331.6  254.71  5391.6  259.65  5481.6  263.81  5601.6  273.89
#Mann=3,-1,0
  4330.7    0.05       0  4984.6    0.03       0  4990.6    0.05       0
Bank Sta=4984.6,4990.6
Exp/Cntr=0.3,0.1

Type RM Length L Ch R = 1,19183,459,459,459
BEGIN DESCRIPTION:
UNT 0426 IN LACR 29.0
END DESCRIPTION:
XS GIS Cut Line= 3
      3676549.62     10647710.19      3676049.61     10647810.19
      3675649.62     10647960.18
#Sta/Elev= 30
  4491.0  264.24  4572.6  261.42  4613.4  258.73  4654.2  254.08  4720.5  250.87
  4776.6  246.05  4888.7  245.86  4898.9  246.59  4949.9  246.86  4970.3  246.15
  4995.4  244.03  4998.1  243.53  5001.4  244.03  5010.7  246.11  5033.0  247.52
  5065.0  246.64  5096.1  248.26  5150.4  248.15  5235.9  251.12  5267.0  252.97
  5272.4  252.49  5297.3  253.44  5302.6  254.79  5310.6  255.16  5357.8  256.29
  5382.7  258.40  5396.1  258.42  5418.3  263.45  5425.4  267.25  5428.1  267.25
#Mann=3,-1,0
  4491.0    0.05       0  4995.4    0.03       0  5001.4    0.05       0
Bank Sta=4995.4,5001.4
Exp/Cntr=0.3,0.1

Type RM Length L Ch R = 1,18724,468,468,468
BEGIN DESCRIPTION:
UNT 0426 IN LACR 28.0
END DESCRIPTION:
XS GIS Cut Line= 3
      3676399.57     10647210.20      3675999.61     10647360.19
      3675649.57     10647360.19
#Sta/Elev= 30
  4559.9  264.67  4685.4  256.17  4709.4  254.35  4715.6  253.04  4745.9  252.09
  4770.8  248.85  4776.1  249.04  4794.8  246.10  4826.0  245.36  4869.6  245.44
  4886.5  246.49  4897.3  246.11  4960.9  245.74  4989.6  244.94  4994.1  244.00
  4996.8  243.50  5000.1  244.00  5007.1  245.45  5037.1  246.88  5077.1  245.64
  5117.1  245.54  5187.1  248.42  5227.1  251.79  5272.1  261.45  5277.1  262.97
  5287.1  263.78  5297.1  269.12  5317.1  277.09  5327.1  278.00  5337.1  277.63
#Mann=6,-1,0
  4559.9    0.05       0  4897.3    0.07       0  4960.9    0.05       0
  4994.1    0.03       0  5000.1    0.05       0  5272.1    0.08       0
Bank Sta=4994.1,5000.1
Exp/Cntr=0.3,0.1

Type RM Length L Ch R = 1,18256,435,435,435
BEGIN DESCRIPTION:
UNT 0426 IN LACR 27.0
END DESCRIPTION:
XS GIS Cut Line= 3
      3676339.67     10646788.72      3675759.84     10646941.49
      3675403.37     10647162.98
#Sta/Elev= 30
  4557.5  264.20  4650.6  261.57  4698.9  258.21  4712.7  258.30  4739.2  255.97
  4764.4  255.44  4779.5  253.76  4795.4  253.76  4847.1  250.32  4960.9  246.27
  4981.6  243.91  4999.2  243.57  5002.0  243.07  5005.2  243.57  5011.0  245.46
  5022.9  247.38  5033.3  247.99  5074.6  247.18  5126.3  249.27  5192.7  249.87
  5258.2  252.22  5279.4  252.02  5294.8  253.21  5316.0  252.99  5447.1  258.75
  5468.3  258.75  5534.1  262.70  5541.6  263.80  5547.4  263.58  5576.8  266.15
#Mann=3,-1,0
  4557.5    0.05       0  4999.2    0.03       0  5005.2    0.05       0
Bank Sta=4999.2,5005.2
Exp/Cntr=0.3,0.1

Type RM Length L Ch R = 1,17821,319,319,319
BEGIN DESCRIPTION:
UNT 0426 IN LACR 26.0
END DESCRIPTION:
XS GIS Cut Line= 3
      3676328.27     10646362.66      3675562.62     10646544.96
      3675031.39     10647039.73
#Sta/Elev= 30
  4403.5  266.32  4505.4  265.62  4631.9  262.32  4751.6  255.76  4800.6  251.05
  4864.7  246.18  4933.1  244.96  4988.1  245.00  5008.6  243.38  5049.7  245.16
  5121.7  245.04  5170.1  243.31  5172.8  242.81  5176.1  243.31  5210.4  245.77
  5387.2  250.68  5507.9  258.55  5578.3  261.19  5592.4  260.52  5599.8  258.63
  5620.8  260.33  5656.4  259.81  5677.4  261.63  5748.3  262.67  5755.1  265.37
  5762.5  264.17  5828.3  266.31  5875.8  269.43  5912.2  269.42  5916.5  269.15
#Mann=7,-1,0
  4403.5    0.05       0  4800.6    0.07       0  4933.1    0.05       0
  5170.1    0.03       0  5176.1    0.05       0  5828.3    0.08       0
  5912.2    0.05       0
Bank Sta=5170.1,5176.1
Exp/Cntr=0.3,0.1

Type RM Length L Ch R = 1,17502,536,536,536
BEGIN DESCRIPTION:
UNT 0426 IN LACR 25.0
END DESCRIPTION:
XS GIS Cut Line= 2
      3676225.51     10646104.07      3674026.14     10646451.21
#Sta/Elev= 30
  4488.5  266.66  4560.0  266.04  4752.4  258.79  4819.9  254.27  4909.6  245.62
  4950.0  244.43  4970.3  244.87  4997.7  242.84  5000.4  242.34  5003.7  242.84
  5012.3  243.91  5041.2  244.75  5069.7  243.97  5385.4  244.04  5646.9  245.46
  5760.0  244.66  5942.2  247.11  5962.4  246.18  5969.2  244.90  6002.9  247.39
  6099.2  246.42  6124.4  247.96  6154.8  247.11  6161.6  248.00  6215.5  248.47
  6286.4  247.83  6296.6  246.94  6347.1  248.06  6551.4  247.08  6715.1  248.05
#Mann=3,-1,0
  4488.5    0.05       0  4997.7    0.03       0  5003.7    0.05       0
Bank Sta=4997.7,5003.7
Exp/Cntr=0.3,0.1

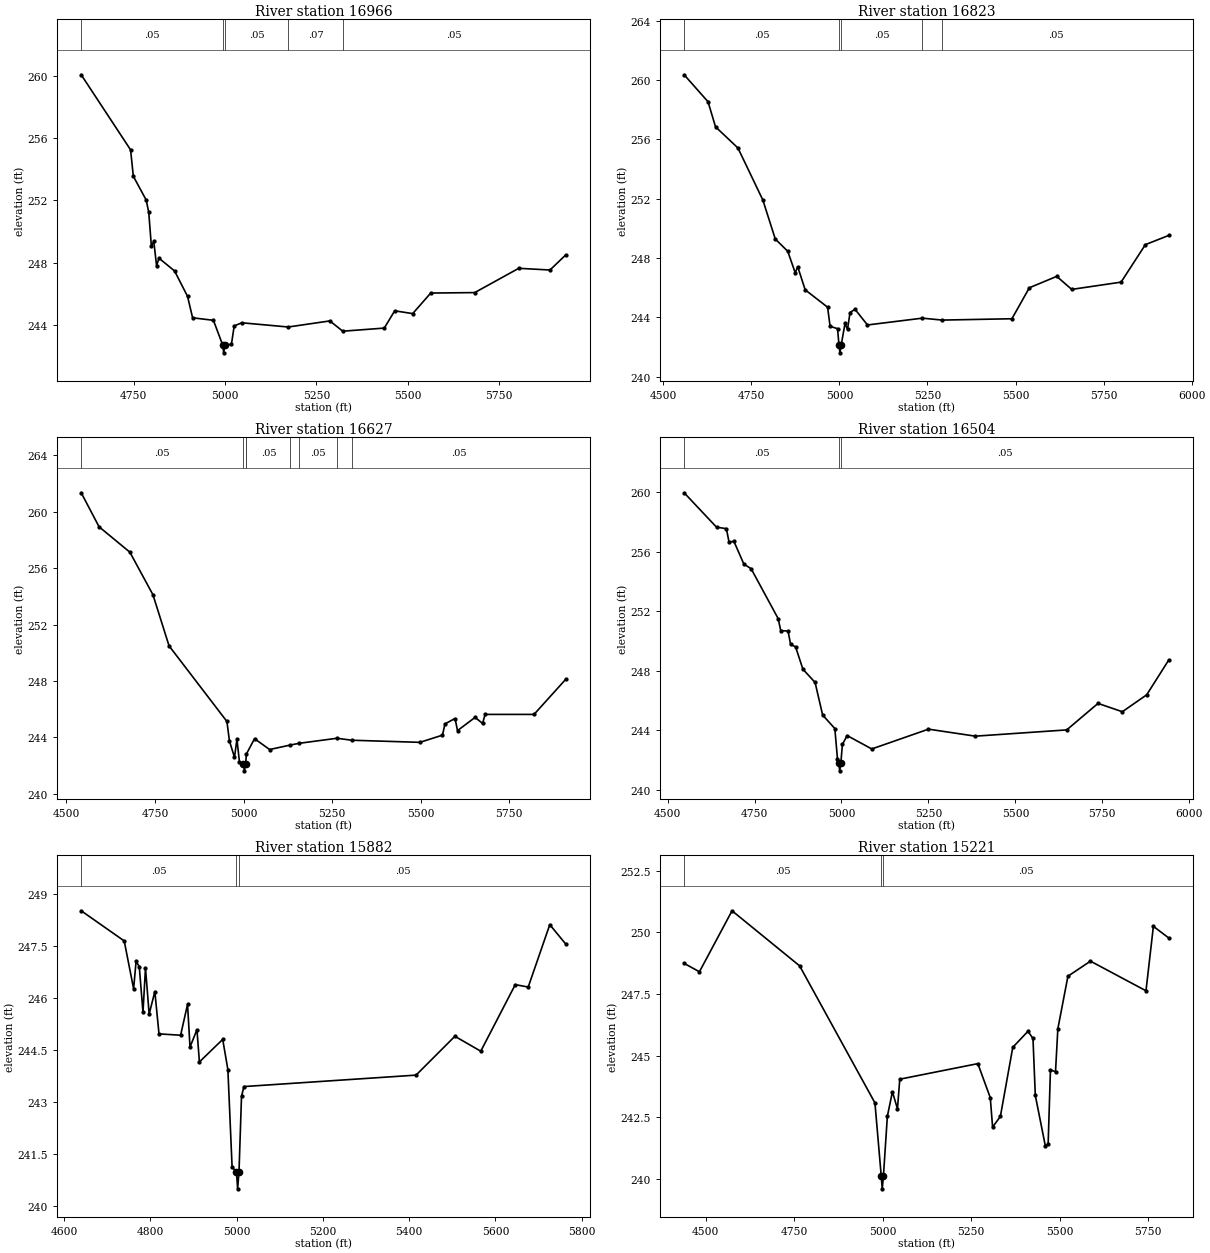
Type RM Length L Ch R = 1,16966,143,143,143
BEGIN DESCRIPTION:
Mapping XS d4e5fb3a
END DESCRIPTION:
XS GIS Cut Line= 2
      3675949.04     10645911.81      3674949.01     10645039.38
#Sta/Elev= 30
  4606.0  260.06  4741.2  255.24  4748.8  253.54  4783.9  252.02  4791.0  251.22
  4798.1  249.07  4804.8  249.36  4812.4  247.80  4819.0  248.28  4861.7  247.46
  4897.2  245.83  4911.1  244.45  4968.1  244.29  4993.5  242.70  4996.3  242.20
  4999.5  242.70  5017.4  242.74  5025.0  243.93  5045.9  244.13  5173.0  243.86
  5287.0  244.25  5322.4  243.59  5436.1  243.79  5464.6  244.90  5513.9  244.72
  5563.3  246.04  5683.8  246.07  5804.4  247.63  5889.9  247.52  5933.1  248.49
#Mann=5,-1,0
  4606.0    0.05       0  4993.5    0.03       0  4999.5    0.05       0
  5173.0    0.07       0  5322.4    0.05       0
Bank Sta=4993.5,4999.5
Exp/Cntr=0.3,0.1

Type RM Length L Ch R = 1,16823,196,196,196
BEGIN DESCRIPTION:
UNT 0426 IN LACR 24.0
END DESCRIPTION:
XS GIS Cut Line= 3
      3675972.46     10645823.25      3675175.58     10645021.16
      3674933.36     10644984.70
#Sta/Elev= 30
  4559.2  260.36  4627.0  258.54  4648.2  256.85  4711.9  255.42  4782.6  251.91
  4817.9  249.28  4853.3  248.45  4874.5  247.00  4881.6  247.41  4902.8  245.85
  4966.4  244.68  4973.5  243.39  4994.7  243.23  4998.8  242.10  5001.5  241.60
  5004.8  242.10  5015.9  243.58  5023.0  243.18  5030.1  244.32  5044.2  244.54
  5079.6  243.48  5235.3  243.94  5291.6  243.81  5489.7  243.90  5539.2  245.99
  5617.0  246.76  5659.4  245.88  5799.6  246.37  5868.6  248.90  5934.8  249.52
#Mann=5,-1,0
  4559.2    0.05       0  4998.8    0.03       0  5004.8    0.05       0
  5235.3    0.07       0  5291.6    0.05       0
Bank Sta=4998.8,5004.8
Exp/Cntr=0.3,0.1

Type RM Length L Ch R = 1,16627,123,123,123
BEGIN DESCRIPTION:
UNT 0426 IN LACR 23.0
END DESCRIPTION:
XS GIS Cut Line= 4
      3676066.22     10645581.06      3675837.04     10645453.45
      3675185.99     10644833.66      3674980.29     10644818.04
#Sta/Elev= 30
  4541.8  261.34  4592.2  258.93  4679.1  257.13  4744.3  254.11  4789.7  250.49
  4953.0  245.13  4960.2  243.74  4974.4  242.59  4981.3  243.87  4988.5  242.24
  4999.7  242.13  5002.4  241.63  5005.7  242.13  5008.2  242.83  5031.0  243.91
  5073.5  243.14  5132.2  243.46  5156.4  243.58  5263.9  243.94  5304.7  243.80
  5497.8  243.65  5561.3  244.16  5568.6  244.96  5596.9  245.34  5603.8  244.48
  5653.5  245.42  5674.5  244.99  5681.8  245.63  5819.8  245.63  5909.3  248.12
#Mann=8,-1,0
  4541.8    0.05       0  4999.7    0.03       0  5005.7    0.05       0
  5008.2    0.05       0  5132.2    0.08       0  5156.4    0.05       0
  5263.9    0.08       0  5304.7    0.05       0
Bank Sta=4999.7,5005.7
Exp/Cntr=0.3,0.1

Type RM Length L Ch R = 1,16504,622,622,622
BEGIN DESCRIPTION:
Mapping XS bdc2d976
END DESCRIPTION:
XS GIS Cut Line= 3
      3676068.77     10645502.90      3675277.14     10644794.60
      3674946.43     10644789.39
#Sta/Elev= 30
  4547.7  259.96  4640.7  257.65  4669.1  257.55  4676.6  256.66  4690.9  256.69
  4719.3  255.17  4740.2  254.86  4817.9  251.51  4825.4  250.70  4846.4  250.67
  4853.8  249.77  4868.1  249.61  4889.0  248.11  4924.1  247.22  4945.8  245.03
  4980.9  244.12  4988.4  242.10  4992.1  241.78  4994.9  241.28  4998.1  241.78
  5002.6  243.05  5016.2  243.65  5087.1  242.75  5250.1  244.08  5384.7  243.61
  5647.5  244.03  5737.5  245.81  5807.5  245.25  5877.5  246.39  5940.7  248.72
#Mann=3,-1,0
  4547.7    0.05       0  4992.1    0.03       0  4998.1    0.05       0
Bank Sta=4992.1,4998.1
Exp/Cntr=0.3,0.1

Type RM Length L Ch R = 1,15882,661,661,661
BEGIN DESCRIPTION:
UNT 0426 IN LACR 22.0
END DESCRIPTION:
XS GIS Cut Line= 3
      3675977.62     10644424.83      3675422.97     10644729.49
      3674932.65     10644737.28
#Sta/Elev= 30
  4639.9  248.52  4739.6  247.65  4761.4  246.27  4767.1  247.06  4774.5  246.91
  4783.1  245.59  4788.9  246.87  4797.4  245.54  4810.6  246.19  4820.2  244.97
  4870.3  244.93  4886.4  245.82  4892.1  244.59  4908.2  245.09  4913.9  244.16
  4967.9  244.81  4979.9  243.94  4989.7  241.12  4999.7  241.00  5002.5  240.50
  5005.7  241.00  5011.5  243.17  5017.2  243.45  5416.1  243.78  5506.1  244.90
  5566.1  244.47  5646.1  246.39  5676.1  246.32  5726.1  248.12  5763.1  247.56
#Mann=3,-1,0
  4639.9    0.05       0  4999.7    0.03       0  5005.7    0.05       0
Bank Sta=4999.7,5005.7
Exp/Cntr=0.3,0.1

Type RM Length L Ch R = 1,15221,443,443,443
BEGIN DESCRIPTION:
UNT 0426 IN LACR 21.0
END DESCRIPTION:
XS GIS Cut Line= 2
      3675476.76     10643847.17      3674587.03     10644888.80
#Sta/Elev= 30
  4438.8  248.74  4482.0  248.40  4574.2  250.87  4765.2  248.64  4978.2  243.09
  4996.1  240.11  4998.8  239.61  5002.1  240.11  5013.3  242.55  5027.6  243.54
  5041.9  242.85  5048.4  244.05  5269.1  244.68  5304.3  243.30  5310.8  242.11
  5332.8  242.54  5367.9  245.34  5410.8  245.99  5425.0  245.70  5431.6  243.39
  5460.2  241.33  5467.9  241.44  5474.4  244.43  5488.7  244.35  5495.3  246.09
  5523.8  248.22  5587.5  248.83  5744.5  247.63  5765.4  250.24  5808.7  249.77
#Mann=3,-1,0
  4438.8    0.05       0  4996.1    0.03       0  5002.1    0.05       0
Bank Sta=4996.1,5002.1
Exp/Cntr=0.3,0.1

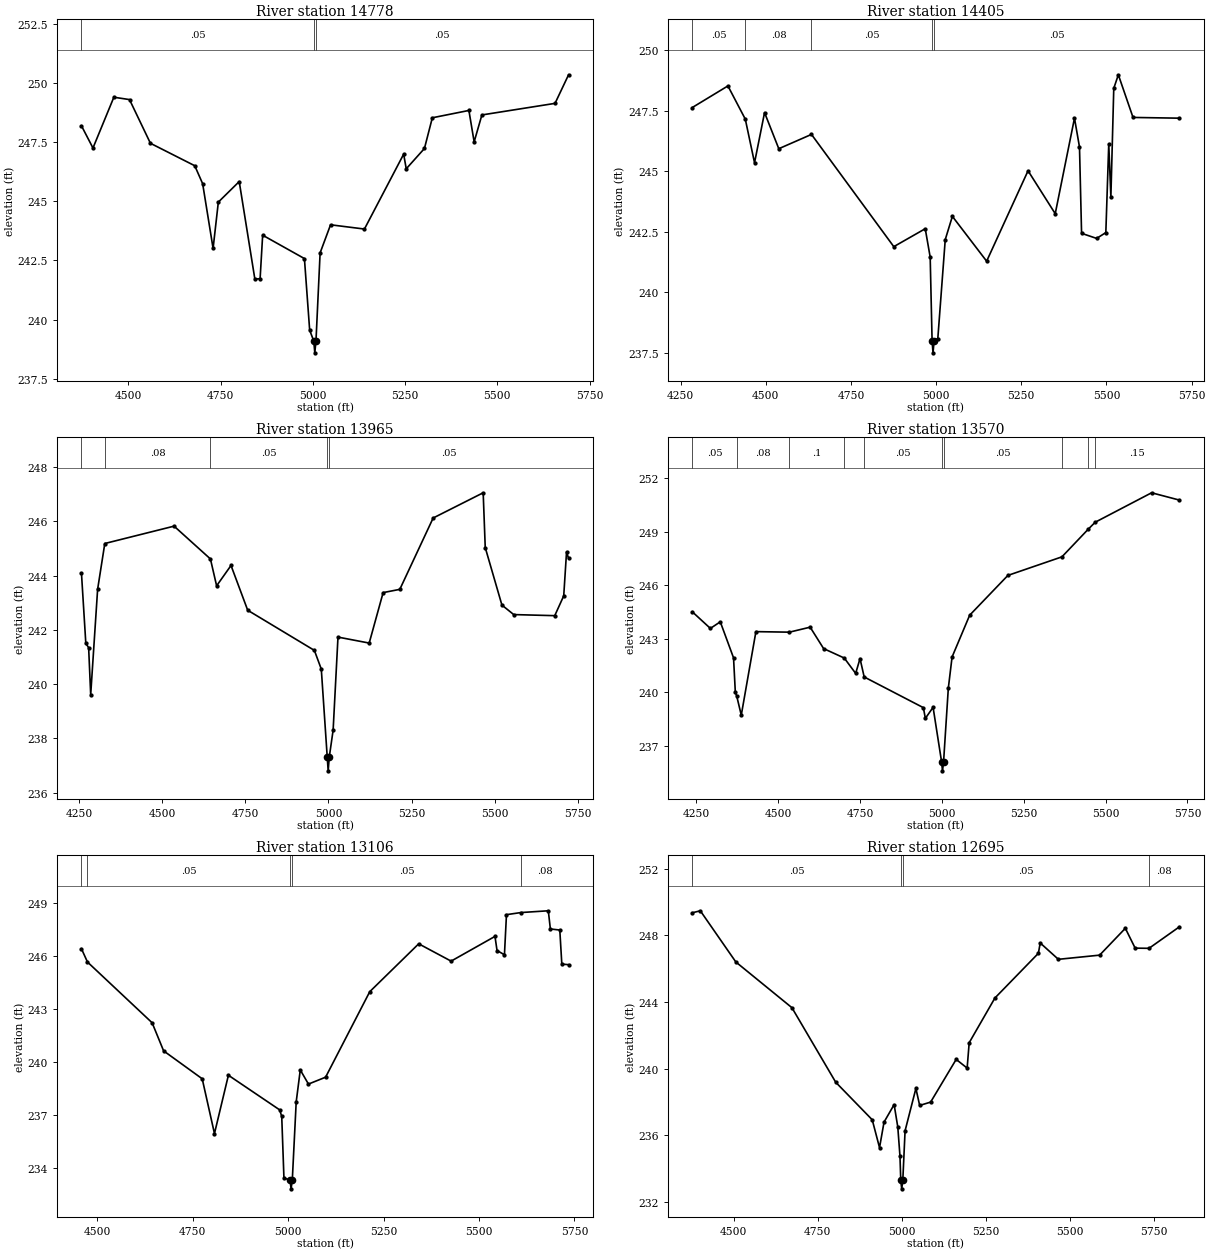
Type RM Length L Ch R = 1,14778,373,373,373
BEGIN DESCRIPTION:
UNT 0426 IN LACR 20.0
END DESCRIPTION:
XS GIS Cut Line= 2
      3675162.10     10643608.43      3674250.68     10644563.26
#Sta/Elev= 30
  4373.1  248.20  4404.3  247.26  4460.9  249.41  4503.3  249.31  4560.0  247.46
  4680.1  246.51  4701.5  245.75  4729.8  243.01  4744.0  244.97  4800.6  245.84
  4843.0  241.71  4857.2  241.73  4864.1  243.57  4977.3  242.58  4991.5  239.55
  5002.6  239.09  5005.4  238.59  5008.6  239.09  5019.8  242.82  5048.1  244.01
  5139.9  243.83  5246.2  247.00  5253.2  246.38  5302.5  247.24  5323.9  248.54
  5423.0  248.85  5437.2  247.52  5458.2  248.66  5656.4  249.15  5693.1  250.36
#Mann=3,-1,0
  4373.1    0.05       0  5002.6    0.03       0  5008.6    0.05       0
Bank Sta=5002.6,5008.6
Exp/Cntr=0.3,0.1

Type RM Length L Ch R = 1,14405,440,440,440
BEGIN DESCRIPTION:
UNT 0426 IN LACR 19.0
END DESCRIPTION:
XS GIS Cut Line= 2
      3675064.44     10643369.71      3673904.07     10644204.75
#Sta/Elev= 30
  4284.6  247.63  4389.1  248.52  4440.1  247.15  4467.2  245.35  4496.6  247.42
  4538.4  245.93  4634.3  246.52  4875.9  241.89  4968.2  242.63  4982.7  241.46
  4988.3  238.01  4991.0  237.51  4994.3  238.01  5005.1  238.10  5026.9  242.18
  5047.8  243.14  5148.4  241.29  5269.9  245.02  5349.7  243.25  5406.2  247.19
  5420.9  246.00  5427.0  242.44  5471.2  242.23  5498.2  242.47  5506.8  246.13
  5513.0  243.94  5521.5  248.42  5534.9  248.98  5578.0  247.22  5714.2  247.19
#Mann=5,-1,0
  4284.6    0.05       0  4440.1    0.08       0  4634.3    0.05       0
  4988.3    0.03       0  4994.3    0.05       0
Bank Sta=4988.3,4994.3
Exp/Cntr=0.3,0.1

Type RM Length L Ch R = 1,13965,395,395,395
BEGIN DESCRIPTION:
UNT 0426 IN LACR 18.0
END DESCRIPTION:
XS GIS Cut Line= 2
      3674847.43     10642979.09      3673666.07     10643846.14
#Sta/Elev= 30
  4257.0  244.09  4270.1  241.50  4278.6  241.34  4284.8  239.61  4305.6  243.49
  4327.2  245.18  4535.6  245.82  4645.0  244.61  4663.6  243.62  4706.9  244.37
  4757.1  242.72  4957.7  241.24  4978.5  240.55  4996.4  237.30  4999.2  236.80
  5002.4  237.30  5014.1  238.30  5028.7  241.73  5122.6  241.51  5164.5  243.37
  5214.7  243.49  5315.0  246.12  5465.5  247.05  5471.7  245.03  5521.9  242.91
  5557.4  242.56  5680.8  242.52  5707.8  243.25  5716.3  244.87  5722.4  244.63
#Mann=5,-1,0
  4257.0    0.05       0  4327.2    0.08       0  4645.0    0.05       0
  4996.4    0.03       0  5002.4    0.05       0
Bank Sta=4996.4,5002.4
Exp/Cntr=0.3,0.1

Type RM Length L Ch R = 1,13570,464,464,464
BEGIN DESCRIPTION:
UNT 0426 IN LACR 17.0
END DESCRIPTION:
XS GIS Cut Line= 2
      3674728.06     10642794.62      3673360.93     10643380.54
#Sta/Elev= 30
  4238.0  244.52  4293.2  243.59  4323.4  243.96  4363.9  241.94  4369.3  240.02
  4373.6  239.80  4387.5  238.73  4432.2  243.41  4534.5  243.38  4597.8  243.66
  4638.9  242.46  4702.0  241.93  4736.8  241.07  4750.1  241.90  4762.8  240.87
  4943.5  239.15  4949.6  238.55  4973.2  239.17  4999.2  236.11  5001.9  235.61
  5005.2  236.11  5019.7  240.24  5031.2  241.99  5084.9  244.33  5201.6  246.56
  5366.6  247.60  5447.5  249.16  5468.2  249.54  5640.4  251.19  5725.4  250.78
#Mann=10,-1,0
  4238.0    0.05       0  4373.6    0.08       0  4534.5     0.1       0
  4702.0    0.08       0  4762.8    0.05       0  4999.2    0.03       0
  5005.2    0.05       0  5366.6    0.08       0  5447.5     0.1       0
  5468.2    0.15       0
Bank Sta=4999.2,5005.2
Exp/Cntr=0.3,0.1

Type RM Length L Ch R = 1,13106,411,411,411
BEGIN DESCRIPTION:
UNT 0426 IN LACR 16.0
END DESCRIPTION:
XS GIS Cut Line= 2
      3674435.13     10642458.24      3673243.07     10642913.39
#Sta/Elev= 30
  4458.5  246.43  4474.2  245.68  4643.6  242.24  4673.7  240.65  4774.8  239.07
  4806.9  235.97  4843.4  239.27  4977.7  237.31  4983.1  236.94  4988.9  233.45
  5004.8  233.34  5007.6  232.84  5010.8  233.34  5021.0  237.76  5031.7  239.57
  5053.1  238.77  5098.0  239.16  5213.7  244.00  5341.9  246.71  5426.8  245.73
  5541.7  247.13  5547.1  246.33  5566.5  246.09  5571.8  248.36  5609.7  248.48
  5681.4  248.58  5686.8  247.55  5711.5  247.49  5716.8  245.56  5734.5  245.53
#Mann=5,-1,0
  4458.5    0.08       0  4474.2    0.05       0  5004.8    0.03       0
  5010.8    0.05       0  5609.7    0.08       0
Bank Sta=5004.8,5010.8
Exp/Cntr=0.3,0.1

Type RM Length L Ch R = 1,12695,553,553,553
BEGIN DESCRIPTION:
UNT 0426 IN LACR 15.0
END DESCRIPTION:
XS GIS Cut Line= 2
      3674402.55     10642024.22      3673067.92     10642588.46
#Sta/Elev= 30
  4376.8  249.35  4400.6  249.47  4506.3  246.40  4673.1  243.66  4803.4  239.19
  4912.0  236.94  4933.7  235.27  4947.1  236.80  4977.1  237.85  4988.0  236.51
  4994.5  234.76  4996.9  233.30  4999.7  232.80  5002.9  233.30  5009.7  236.28
  5041.9  238.82  5053.1  237.80  5085.7  238.00  5161.7  240.56  5194.3  240.04
  5200.4  241.56  5276.9  244.24  5406.2  246.92  5411.7  247.54  5465.7  246.56
  5588.4  246.81  5664.9  248.42  5694.1  247.23  5735.4  247.22  5825.8  248.51
#Mann=4,-1,0
  4376.8    0.05       0  4996.9    0.03       0  5002.9    0.05       0
  5735.4    0.08       0
Bank Sta=4996.9,5002.9
Exp/Cntr=0.3,0.1

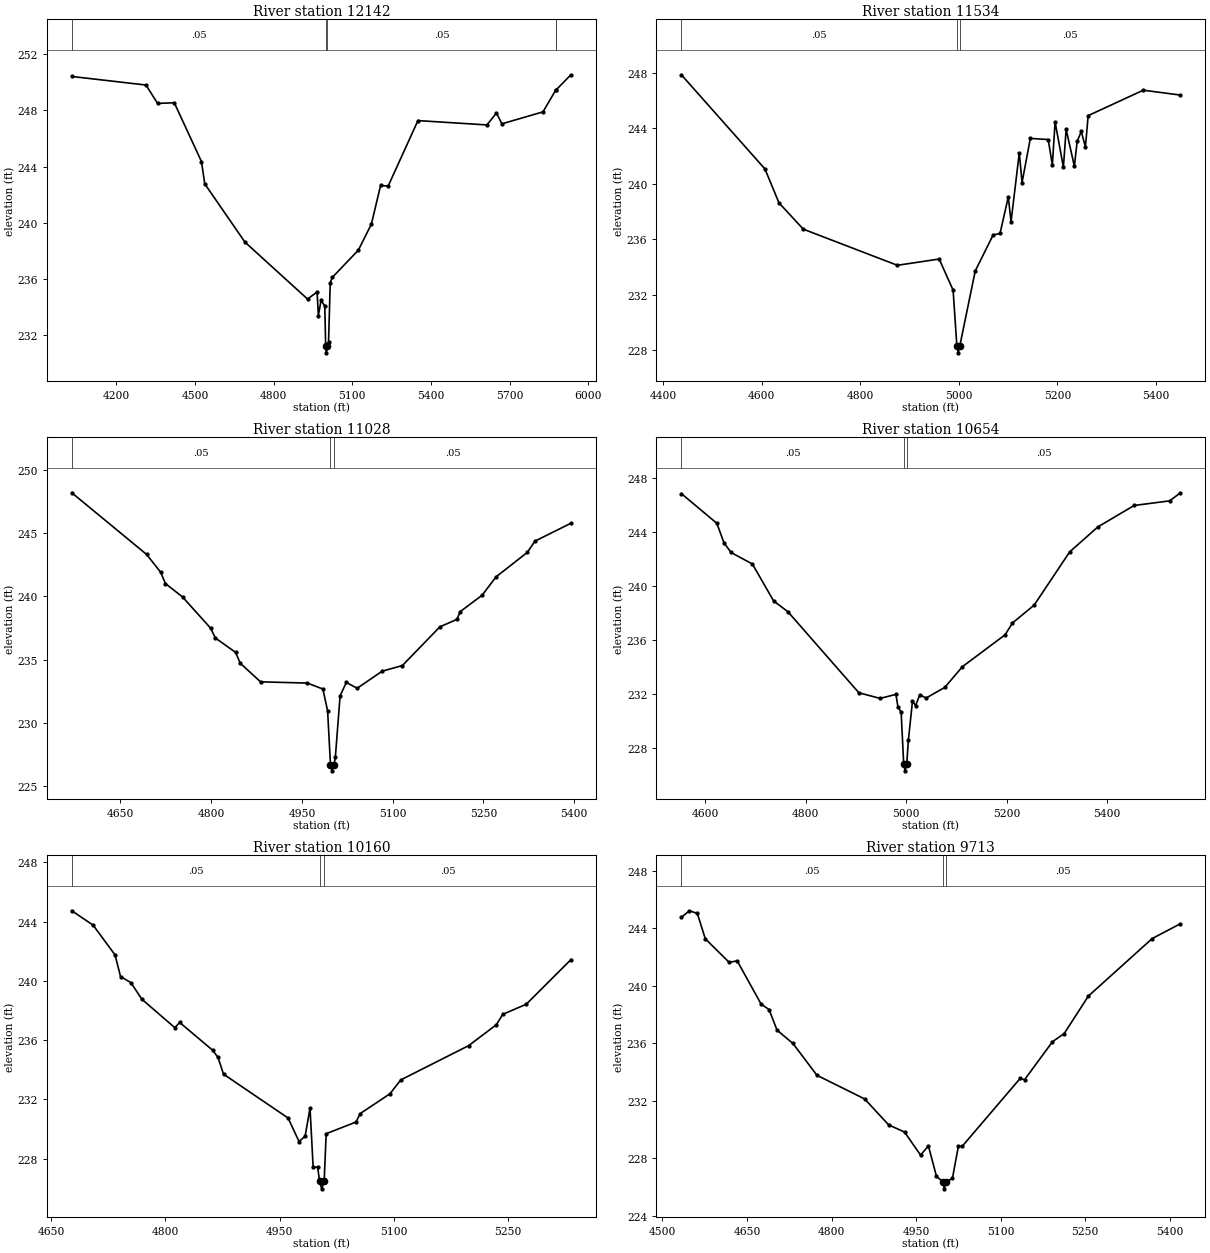
Type RM Length L Ch R = 1,12142,608,608,608
BEGIN DESCRIPTION:
UNT 0426 IN LACR 14.0
END DESCRIPTION:
XS GIS Cut Line= 3
      3674399.63     10641260.17      3673599.61     10641760.19
      3672999.60     10642510.19
#Sta/Elev= 30
  4029.9  250.41  4312.9  249.80  4357.2  248.49  4420.8  248.54  4524.6  244.35
  4537.0  242.77  4690.3  238.62  4929.1  234.57  4965.7  235.07  4970.4  233.38
  4980.5  234.47  4994.9  234.07  4998.3  231.24  5001.1  230.74  5004.3  231.24
  5009.3  231.53  5015.7  235.73  5023.7  236.11  5123.0  238.05  5172.6  239.90
  5207.8  242.65  5236.7  242.61  5350.3  247.27  5613.6  246.96  5649.7  247.81
  5670.5  247.04  5827.3  247.89  5875.4  249.42  5876.6  249.44  5933.8  250.53
#Mann=5,-1,0
  4029.9    0.05       0  4998.3    0.03       0  5004.3    0.05       0
  5875.4    0.08       0  5876.6    0.15       0
Bank Sta=4998.3,5004.3
Exp/Cntr=0.3,0.1

Type RM Length L Ch R = 1,11534,506,506,506
BEGIN DESCRIPTION:
UNT 0426 IN LACR 13.0
END DESCRIPTION:
XS GIS Cut Line= 3
      3673899.58     10640960.22      3673499.61     10641360.19
      3673099.57     10641560.21
#Sta/Elev= 30
  4436.7  247.84  4606.4  241.06  4634.7  238.63  4684.1  236.73  4875.1  234.13
  4959.9  234.58  4988.2  232.34  4995.8  228.33  4998.6  227.83  5001.8  228.33
  5033.1  233.72  5069.4  236.31  5083.4  236.42  5100.2  239.05  5105.8  237.26
  5122.5  242.23  5128.1  240.08  5144.9  243.26  5181.2  243.18  5189.6  241.35
  5195.2  244.45  5212.0  241.19  5217.6  243.91  5234.3  241.26  5239.9  243.04
  5248.3  243.76  5256.7  242.64  5262.3  244.90  5374.1  246.73  5449.6  246.38
#Mann=3,-1,0
  4436.7    0.05       0  4995.8    0.03       0  5001.8    0.05       0
Bank Sta=4995.8,5001.8
Exp/Cntr=0.3,0.1

Type RM Length L Ch R = 1,11028,374,374,374
BEGIN DESCRIPTION:
UNT 0426 IN LACR 12.0
END DESCRIPTION:
XS GIS Cut Line= 3
      3673849.65     10640810.18      3673449.61     10640910.19
      3673049.57     10641010.20
#Sta/Elev= 30
  4569.8  248.20  4693.5  243.32  4716.7  241.91  4724.5  241.02  4752.8  239.96
  4799.2  237.49  4806.9  236.72  4840.4  235.58  4848.1  234.72  4881.6  233.25
  4959.0  233.15  4984.7  232.68  4992.5  230.94  4997.2  226.71  4999.9  226.21
  5003.2  226.71  5005.3  227.31  5013.1  232.14  5023.4  233.20  5041.4  232.74
  5082.6  234.09  5116.1  234.54  5178.0  237.60  5206.3  238.19  5211.5  238.80
  5247.6  240.09  5270.8  241.55  5322.3  243.48  5335.2  244.38  5394.5  245.79
#Mann=3,-1,0
  4569.8    0.05       0  4997.2    0.03       0  5003.2    0.05       0
Bank Sta=4997.2,5003.2
Exp/Cntr=0.3,0.1

Type RM Length L Ch R = 1,10654,494,494,494
BEGIN DESCRIPTION:
UNT 0426 IN LACR 11.0
END DESCRIPTION:
XS GIS Cut Line= 3
      3673649.63     10640260.16      3673349.61     10640560.19
      3672899.60     10640910.20
#Sta/Elev= 30
  4552.1  246.84  4622.8  244.64  4637.0  243.20  4651.1  242.48  4693.6  241.63
  4736.0  238.89  4764.3  238.10  4905.7  232.10  4948.1  231.68  4979.6  231.98
  4983.6  231.06  4990.0  230.65  4995.1  226.82  4997.9  226.32  5001.1  226.82
  5004.5  228.62  5012.6  231.48  5018.9  231.15  5027.1  231.95  5039.7  231.71
  5076.8  232.49  5112.1  234.03  5197.2  236.39  5211.7  237.26  5255.1  238.59
  5325.7  242.52  5381.8  244.37  5454.2  245.96  5524.8  246.30  5546.5  246.90
#Mann=3,-1,0
  4552.1    0.05       0  4995.1    0.03       0  5001.1    0.05       0
Bank Sta=4995.1,5001.1
Exp/Cntr=0.3,0.1

Type RM Length L Ch R = 1,10160,447,447,447
BEGIN DESCRIPTION:
UNT 0426 IN LACR 10.0
END DESCRIPTION:
XS GIS Cut Line= 3
      3673449.61     10639960.19      3673199.61     10640160.19
      3672899.58     10640310.21
#Sta/Elev= 30
  4677.1  244.73  4705.1  243.76  4733.9  241.75  4741.1  240.29  4754.7  239.88
  4769.1  238.76  4812.4  236.84  4818.8  237.19  4862.0  235.32  4869.2  234.83
  4876.4  233.70  4961.2  230.74  4975.6  229.15  4983.6  229.52  4990.0  231.41
  4994.1  227.43  5000.0  227.43  5002.6  226.46  5005.4  225.96  5008.6  226.46
  5011.2  229.68  5050.4  230.47  5055.9  231.04  5095.1  232.38  5109.1  233.31
  5198.5  235.63  5234.8  237.04  5243.2  237.74  5274.0  238.42  5332.7  241.43
#Mann=3,-1,0
  4677.1    0.05       0  5002.6    0.03       0  5008.6    0.05       0
Bank Sta=5002.6,5008.6
Exp/Cntr=0.3,0.1

Type RM Length L Ch R = 1,9713,399,399,399
BEGIN DESCRIPTION:
UNT 0426 IN LACR 9.0
END DESCRIPTION:
XS GIS Cut Line= 3
      3673299.64     10639460.16      3672949.61     10639810.19
      3672649.63     10640060.17
#Sta/Elev= 30
  4533.5  244.76  4547.7  245.22  4561.8  245.04  4576.0  243.27  4618.4  241.63
  4632.5  241.74  4675.0  238.73  4689.1  238.35  4703.2  236.92  4731.5  235.99
  4774.0  233.78  4858.8  232.13  4901.2  230.33  4929.5  229.83  4957.8  228.23
  4971.9  228.86  4986.1  226.75  4997.2  226.38  5000.0  225.88  5003.2  226.38
  5014.4  226.60  5025.0  228.84  5031.8  228.84  5134.6  233.56  5142.4  233.47
  5191.9  236.11  5212.7  236.68  5255.7  239.29  5368.9  243.29  5419.0  244.32
#Mann=3,-1,0
  4533.5    0.05       0  4997.2    0.03       0  5003.2    0.05       0
Bank Sta=4997.2,5003.2
Exp/Cntr=0.3,0.1

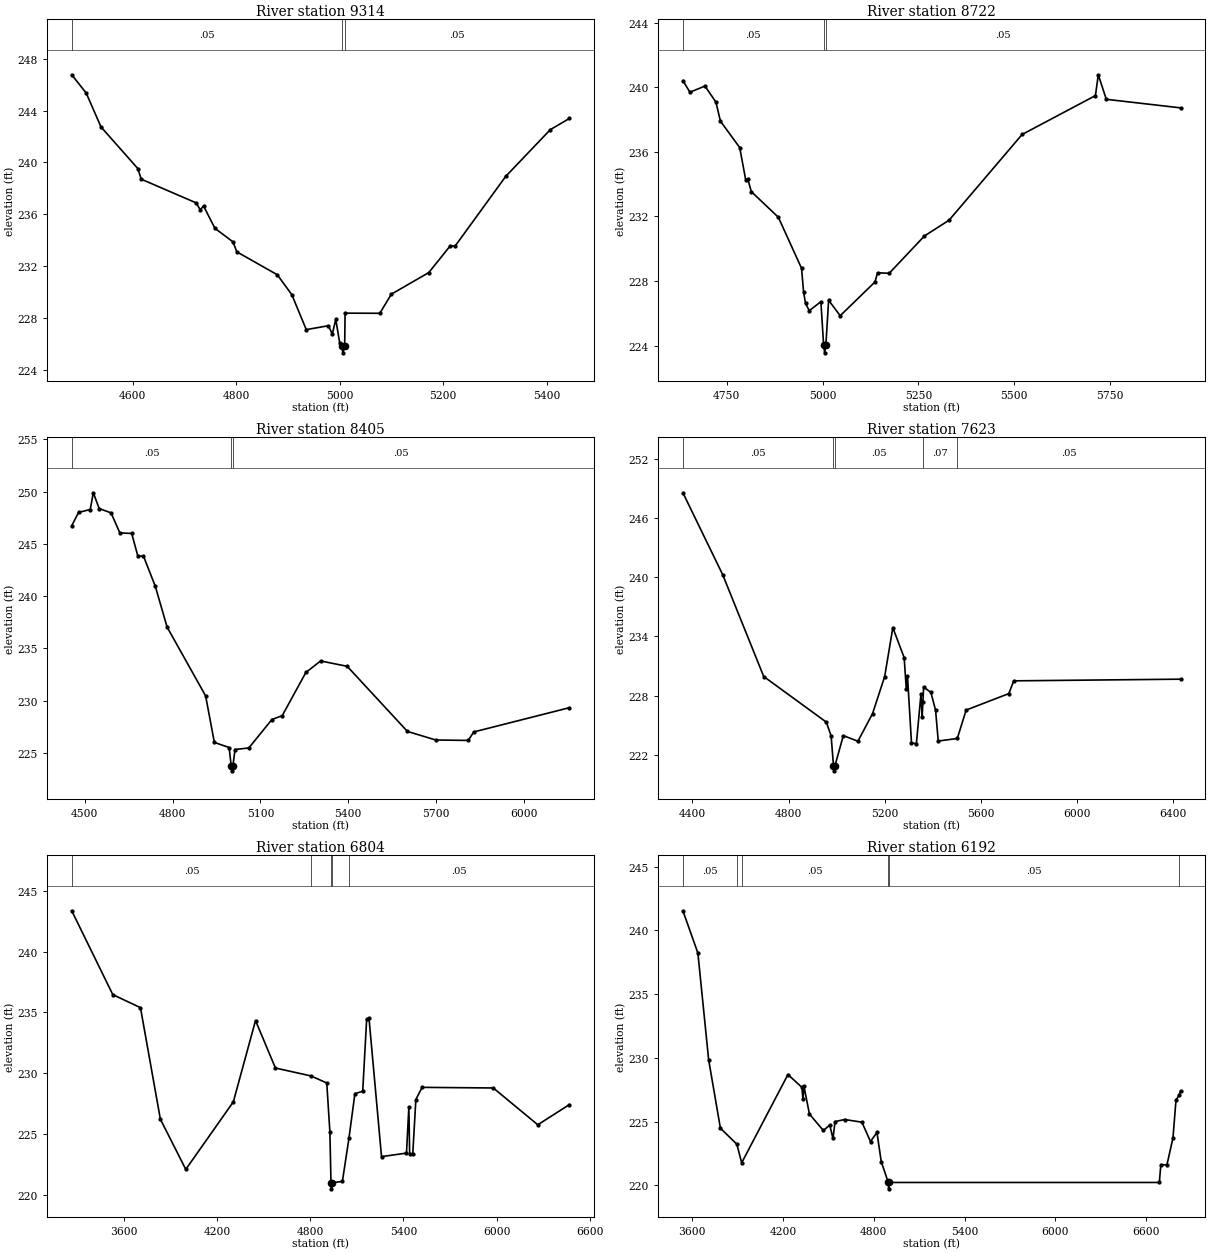
Type RM Length L Ch R = 1,9314,592,592,592
BEGIN DESCRIPTION:
UNT 0426 IN LACR 8.0
END DESCRIPTION:
XS GIS Cut Line= 3
      3673199.61     10639110.19      3672799.61     10639460.19
      3672449.63     10639710.17
#Sta/Elev= 30
  4482.3  246.76  4510.3  245.35  4538.8  242.74  4610.0  239.53  4616.6  238.71
  4722.9  236.88  4730.5  236.35  4737.1  236.64  4759.0  234.92  4794.1  233.87
  4801.2  233.11  4879.5  231.34  4907.5  229.81  4935.5  227.11  4978.2  227.41
  4985.8  226.77  4992.5  227.90  5000.0  226.11  5003.7  225.82  5006.4  225.32
  5009.7  225.82  5010.5  228.38  5077.7  228.37  5099.8  229.84  5172.3  231.51
  5214.1  233.59  5222.7  233.53  5321.0  238.93  5407.1  242.53  5443.9  243.39
#Mann=3,-1,0
  4482.3    0.05       0  5003.7    0.03       0  5009.7    0.05       0
Bank Sta=5003.7,5009.7
Exp/Cntr=0.3,0.1

Type RM Length L Ch R = 1,8722,317,317,317
BEGIN DESCRIPTION:
UNT 0426 IN LACR 7.0
END DESCRIPTION:
XS GIS Cut Line= 3
      3673036.61     10639003.29      3672531.37     10639071.00
      3672005.34     10639659.52
#Sta/Elev= 30
  4635.3  240.42  4653.6  239.70  4692.8  240.08  4721.5  239.09  4733.2  237.91
  4783.6  236.27  4799.5  234.24  4804.5  234.33  4813.9  233.54  4884.5  231.95
  4945.0  228.79  4950.4  227.31  4955.5  226.61  4965.2  226.16  4995.5  226.72
  5002.6  224.05  5005.3  223.55  5008.6  224.05  5015.7  226.81  5045.9  225.85
  5136.7  227.94  5143.4  228.51  5173.9  228.48  5265.8  230.79  5330.2  231.77
  5520.8  237.08  5712.2  239.49  5719.7  240.78  5740.6  239.26  5934.4  238.73
#Mann=3,-1,0
  4635.3    0.05       0  5002.6    0.03       0  5008.6    0.05       0
Bank Sta=5002.6,5008.6
Exp/Cntr=0.3,0.1

Type RM Length L Ch R = 1,8405,782,782,782
BEGIN DESCRIPTION:
UNT 0426 IN LACR 6.0
END DESCRIPTION:
XS GIS Cut Line= 2
      3673192.64     10638853.99      3671507.03     10638633.23
#Sta/Elev= 30
  4455.2  246.73  4478.4  248.01  4518.3  248.29  4528.9  249.89  4549.0  248.38
  4589.4  247.97  4619.6  246.05  4660.0  246.00  4681.1  243.83  4700.3  243.83
  4740.6  240.95  4781.0  237.04  4912.6  230.46  4942.4  226.01  4992.8  225.52
  4999.9  223.79  5002.6  223.29  5005.9  223.79  5013.0  225.33  5060.2  225.48
  5139.0  228.20  5174.3  228.57  5255.0  232.70  5305.4  233.80  5396.2  233.29
  5602.0  227.06  5698.8  226.24  5809.7  226.20  5828.5  227.01  6155.2  229.33
#Mann=3,-1,0
  4455.2    0.05       0  4999.9    0.03       0  5005.9    0.05       0
Bank Sta=4999.9,5005.9
Exp/Cntr=0.3,0.1

Type RM Length L Ch R = 1,7623,819,819,819
BEGIN DESCRIPTION:
UNT 0426 IN LACR 5.0
END DESCRIPTION:
XS GIS Cut Line= 3
      3673487.72     10638645.62      3673199.45     10638293.30
      3671604.36     10638029.38
#Sta/Elev= 30
  4360.1  248.56  4525.8  240.26  4696.6  229.94  4957.1  225.32  4977.3  223.92
  4987.1  220.88  4989.8  220.38  4993.1  220.88  5028.0  223.95  5088.8  223.38
  5149.7  226.18  5200.3  229.94  5234.2  234.89  5281.4  231.85  5290.2  228.67
  5295.2  229.99  5311.8  223.24  5332.1  223.11  5351.2  228.12  5356.3  225.85
  5359.3  227.32  5362.5  228.88  5392.9  228.32  5412.2  226.51  5423.3  223.40
  5502.6  223.66  5539.4  226.54  5717.3  228.21  5737.5  229.50  6432.1  229.67
#Mann=5,-1,0
  4360.1    0.05       0  4987.1    0.03       0  4993.1    0.05       0
  5359.3    0.07       0  5502.6    0.05       0
Bank Sta=4987.1,4993.1
Exp/Cntr=0.3,0.1

Type RM Length L Ch R = 1,6804,612,612,612
BEGIN DESCRIPTION:
UNT 0426 IN LACR 4.0
END DESCRIPTION:
XS GIS Cut Line= 3
      3674008.58     10638732.46      3673192.61     10637699.47
      3671317.63     10637491.14
#Sta/Elev= 30
  3265.0  243.37  3529.3  236.47  3707.3  235.40  3835.5  226.22  3999.0  222.09
  4305.2  227.65  4447.9  234.34  4576.1  230.43  4805.1  229.78  4906.4  229.20
  4926.5  225.19  4933.6  220.99  4936.3  220.49  4939.6  220.99  5007.0  221.10
  5049.2  224.65  5087.5  228.32  5137.8  228.52  5163.2  234.45  5178.0  234.57
  5258.8  223.14  5419.5  223.43  5434.9  227.23  5439.9  223.32  5459.8  223.33
  5479.9  227.84  5520.1  228.84  5978.2  228.79  6264.7  225.76  6467.9  227.42
#Mann=5,-1,0
  3265.0    0.05       0  4805.1    0.07       0  4933.6    0.07       0
  4939.6    0.07       0  5049.2    0.05       0
Bank Sta=4933.6,4939.6
Exp/Cntr=0.3,0.1

Type RM Length L Ch R = 1,6192,1003,1003,1003
BEGIN DESCRIPTION:
UNT 0426 IN LACR 3.0
END DESCRIPTION:
XS GIS Cut Line= 3
      3674149.62     10638310.20      3673149.61     10637210.19
      3671349.63     10637210.19
#Sta/Elev= 30
  3539.4  241.54  3638.4  238.22  3709.4  229.85  3787.1  224.48  3895.8  223.22
  3927.6  221.76  4233.1  228.69  4325.0  227.69  4332.4  226.75  4339.1  227.76
  4375.0  225.59  4466.9  224.30  4509.4  224.72  4530.4  223.68  4544.6  225.00
  4608.1  225.16  4721.6  224.95  4778.4  223.43  4820.9  224.15  4849.3  221.86
  4895.7  220.22  4898.4  219.72  4901.7  220.22  6686.0  220.22  6696.0  221.62
  6736.0  221.59  6776.0  223.71  6796.0  226.68  6816.0  227.06  6826.0  227.38
#Mann=6,-1,0
  3539.4    0.05       0  3895.8    0.07       0  3927.6    0.05       0
  4895.7   0.033       0  4901.7    0.05       0  6816.0    0.07       0
Bank Sta=4895.7,4901.7
Exp/Cntr=0.3,0.1