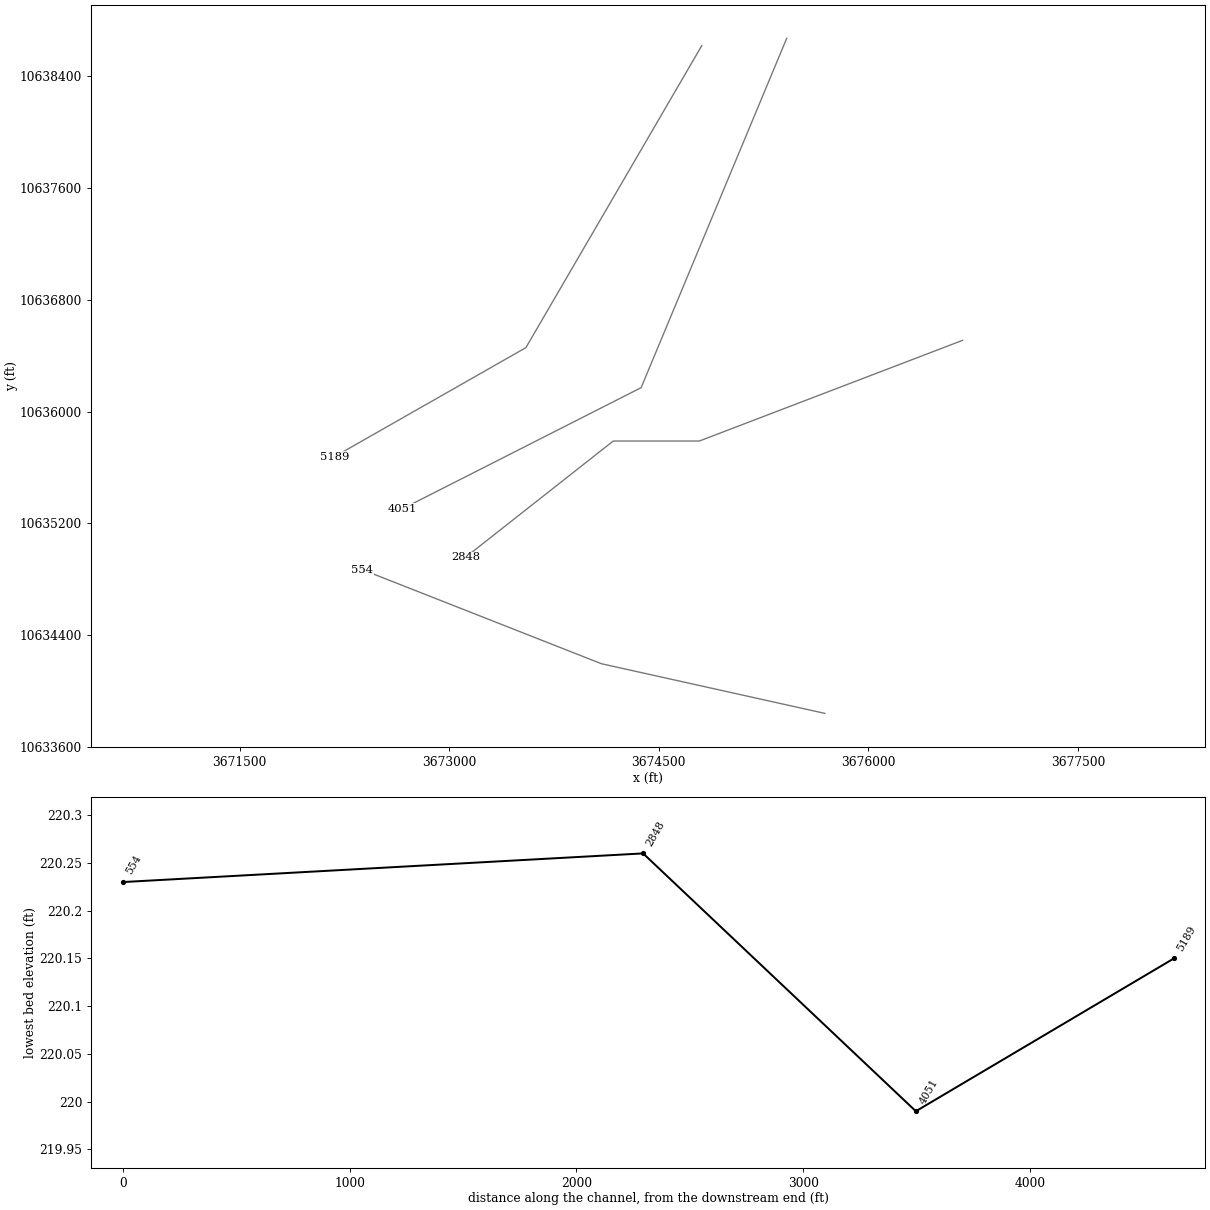
HEC-RAS study UNT 0426 IN LACR.prj: UNT 0426 IN LACR Base Level Engineering

--- UNT 0426 IN LACR.g01 (geometry) --- (continued)

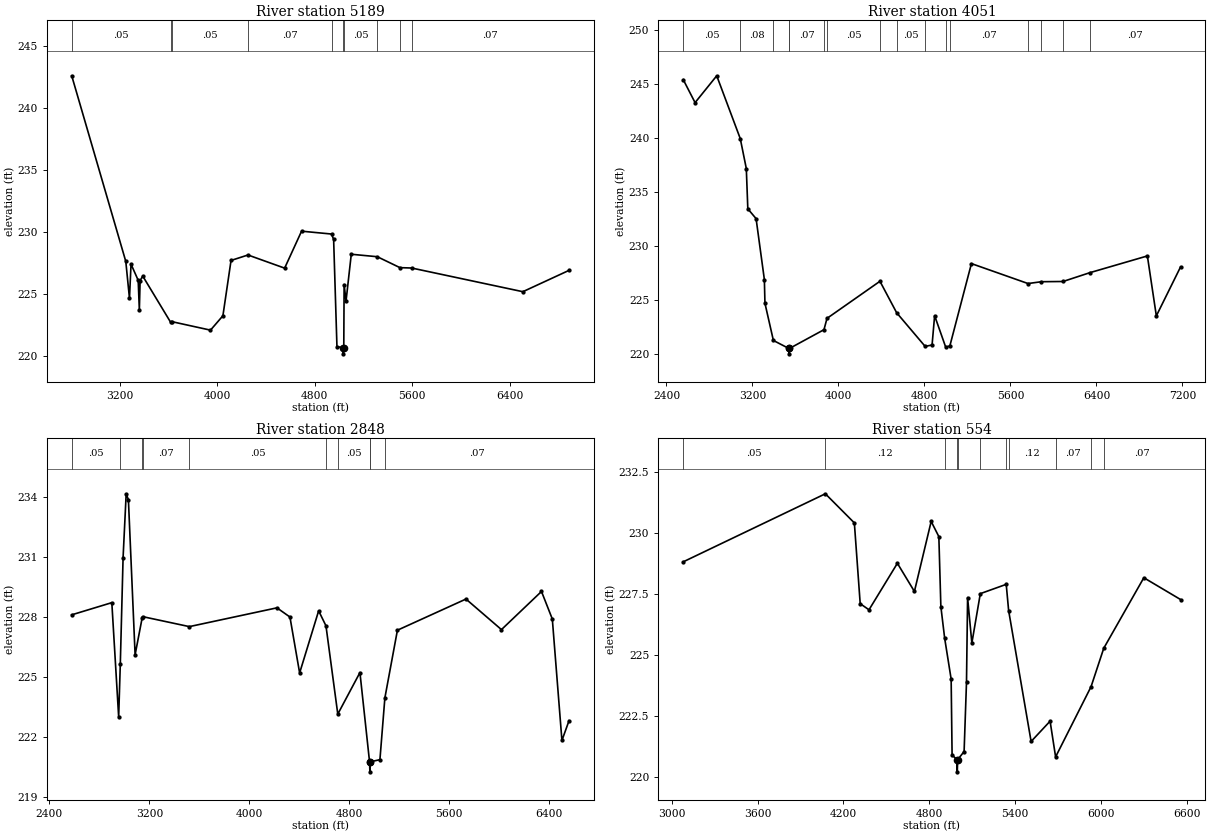
Type RM Length L Ch R = 1,5189,1138,1138,1138
BEGIN DESCRIPTION:
UNT 0426 IN LACR 2.0
END DESCRIPTION:
XS GIS Cut Line= 3
      3674807.20     10638619.62      3673548.51     10636458.15
      3672176.96     10635676.89
#Sta/Elev= 30
  2805.7  242.57  3249.3  227.60  3279.5  224.63  3292.3  227.38  3351.0  226.08
  3360.5  223.69  3366.8  226.06  3388.3  226.42  3616.9  222.70  3629.4  222.74
  3944.2  222.06  4046.0  223.22  4112.7  227.68  4251.7  228.12  4552.4  227.06
  4691.3  230.04  4936.9  229.81  4954.3  229.38  4981.6  220.73  5031.6  220.65
  5034.3  220.15  5037.6  220.65  5040.4  225.74  5056.1  224.41  5099.1  228.18
  5312.8  227.98  5498.3  227.10  5594.3  227.07  6506.6  225.16  6885.4  226.88
#Mann=10,-1,0
  2805.7    0.05       0  3616.9    0.07       0  3629.4    0.05       0
  4251.7    0.07       0  4936.9    0.05       0  5031.6    0.03       0
  5037.6    0.05       0  5312.8    0.07       0  5498.3    0.05       0
  5594.3    0.07       0
Bank Sta=5031.6,5037.6
Exp/Cntr=0.3,0.1

Type RM Length L Ch R = 1,4051,1203,1203,1203
BEGIN DESCRIPTION:
Mapping XS bf12bd45
END DESCRIPTION:
XS GIS Cut Line= 3
      3675414.83     10638671.70      3674373.17     10636171.69
      3672663.10     10635303.64
#Sta/Elev= 30
  2556.3  245.42  2666.3  243.29  2867.8  245.78  3086.8  239.95  3142.9  237.18
  3157.0  233.44  3233.9  232.53  3310.9  226.88  3316.3  224.68  3394.8  221.23
  3538.6  220.49  3541.4  219.99  3544.6  220.49  3865.4  222.23  3893.6  223.28
  4386.1  226.72  4541.5  223.80  4806.6  220.68  4870.9  220.81  4894.7  223.53
  4998.1  220.60  5036.5  220.73  5237.0  228.36  5763.5  226.51  5888.6  226.68
  6089.1  226.70  6339.5  227.52  6873.8  229.07  6957.2  223.51  7182.4  228.05
#Mann=16,-1,0
  2556.3    0.05       0  3086.8    0.08       0  3394.8    0.07       0
  3538.6    0.03       0  3544.6    0.07       0  3865.4    0.08       0
  3893.6    0.05       0  4386.1    0.07       0  4541.5    0.05       0
  4806.6    0.07       0  4998.1    0.05       0  5036.5    0.07       0
  5763.5    0.05       0  5888.6    0.07       0  6089.1    0.05       0
  6339.5    0.07       0
Bank Sta=3538.6,3544.6
Exp/Cntr=0.3,0.1

Type RM Length L Ch R = 1,2848,2294,2294,2294
BEGIN DESCRIPTION:
Mapping XS 1a839922
END DESCRIPTION:
XS GIS Cut Line= 4
      3676673.50     10636510.23      3674789.83     10635789.75
      3674173.51     10635789.75      3673114.53     10634956.45
#Sta/Elev= 30
  2578.9  228.12  2899.9  228.73  2954.7  223.01  2967.9  225.68  2990.1  230.99
  3014.8  234.18  3032.7  233.88  3086.3  226.12  3142.5  227.96  3146.5  228.03
  3520.5  227.53  4221.5  228.47  4325.7  228.01  4403.2  225.21  4555.4  228.32
  4614.0  227.57  4708.6  223.15  4885.9  225.23  4962.9  220.76  4965.6  220.26
  4968.9  220.76  5045.9  220.87  5085.5  223.96  5185.9  227.35  5734.6  228.91
  6018.6  227.38  6339.1  229.29  6425.8  227.91  6502.7  221.83  6559.5  222.82
#Mann=10,-1,0
  2578.9    0.05       0  2967.9    0.08       0  3142.5    0.05       0
  3146.5    0.07       0  3520.5    0.05       0  4614.0    0.07       0
  4708.6    0.05       0  4962.9    0.03       0  4968.9    0.05       0
  5085.5    0.07       0
Bank Sta=4962.9,4968.9
Exp/Cntr=0.3,0.1

Type RM Length L Ch R = 1,554,0,0,0
BEGIN DESCRIPTION:
UNT 0426 IN LACR 1.0
END DESCRIPTION:
XS GIS Cut Line= 3
      3675687.68     10633840.62      3674089.36     10634195.80
      3672376.64     10634869.61
#Sta/Elev= 30
  3079.4  228.81  4073.2  231.59  4276.0  230.40  4316.9  227.10  4378.4  226.85
  4576.9  228.75  4696.0  227.60  4813.2  230.46  4866.9  229.84  4881.0  226.98
  4907.5  225.69  4952.9  224.02  4959.5  220.92  4992.8  220.73  4995.6  220.23
  4998.8  220.73  5043.5  221.06  5060.3  223.90  5067.9  227.35  5097.7  225.49
  5156.9  227.51  5338.1  227.89  5354.9  226.82  5512.1  221.47  5644.9  222.30
  5683.4  220.84  5931.4  223.71  6020.2  225.28  6300.4  228.16  6557.2  227.27
#Mann=11,-1,0
  3079.4    0.05       0  4073.2    0.12       0  4907.5    0.07       0
  4992.8    0.07       0  4998.8    0.07       0  5156.9    0.12       0
  5338.1    0.07       0  5354.9    0.12       0  5683.4    0.07       0
  5931.4    0.05       0  6020.2    0.07       0
Bank Sta=4992.8,4998.8
Exp/Cntr=0.3,0.1

Chan Stop Cuts=-1