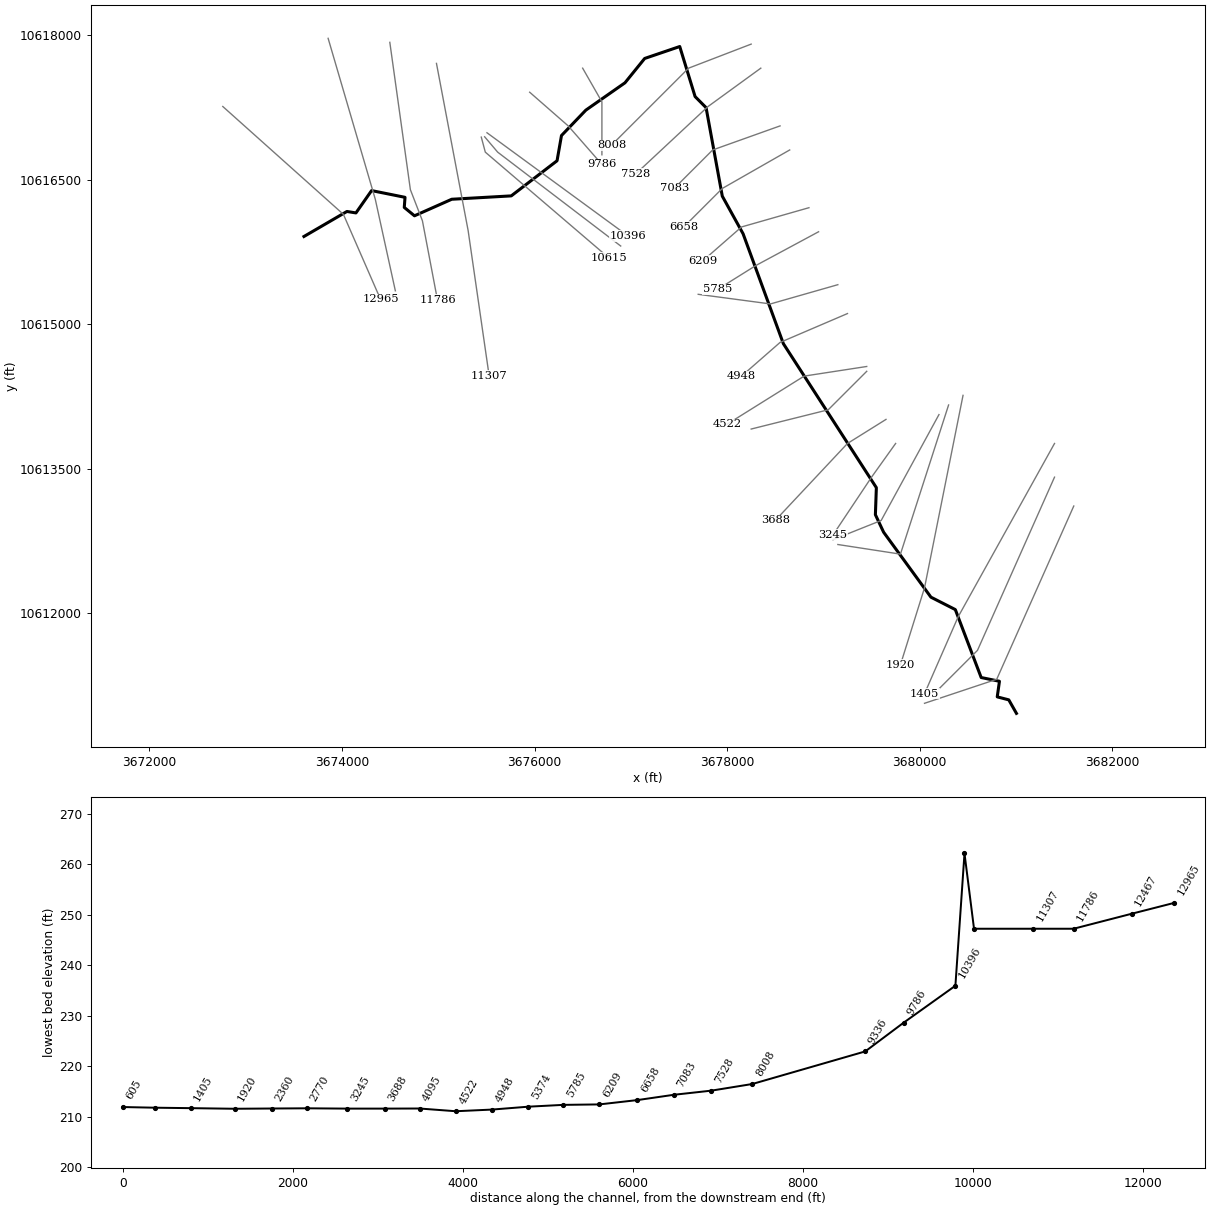
--- UNT 0431 IN LACR.prj (project) ---

Proj Title=UNT 0431 IN LACR Base Level Engineering
Current Plan=p01
Default Exp/Contr=0.3,0.1
English Units
Geom File=g01
Flow File=f01
Plan File=p01
BEGIN DESCRIPTION:
UNT 0431 IN LACR
END DESCRIPTION:

--- UNT 0431 IN LACR.p01 (plan) ---

Plan Title=Multiple Run
Short Identifier=Multiple
Geom File=g01
Flow File=f01
Subcritical Flow
K Sum by GR= 0
Std Step Tol= 0.01
Critical Tol= 0.01
Num of Std Step Trials= 20
Max Error Tol= 0.3
Flow Tol Ratio= 0.001
Split Flow NTrial= 30
Split Flow Tol= 0.02
Split Flow Ratio= 0.02
Log Output Level= 0
Friction Slope Method= 1
Unsteady Friction Slope Method= 2
Unsteady Bridges Friction Slope Method= 1
Parabolic Critical Depth
Global Vel Dist=  1 , 1 , 1
Global Log Level= 0
CheckData=True
Encroach Param= -1, 0, 0, 0
BEGIN DESCRIPTION:
Multiple Run
END DESCRIPTION:

--- UNT 0431 IN LACR.f01 (steady flow) ---

Flow Title=Multiple
Number of Profiles=7
Profile Names=10-year,25-year,50-year,1pct_min,100-year,1pct_plu,500-year
River Rch & RM= UNT 0431 IN LACR,Reach-1,12965
     711     990    1226    1118    1511    2044    2305
River Rch & RM= UNT 0431 IN LACR,Reach-1,8008
    1678    2433    3099    2894    3914    5294    6276
River Rch & RM= UNT 0431 IN LACR,Reach-1,4948
    1997    2921    3741    3512    4750    6424    7696
Boundary for River Rch & Prof#=UNT 0431 IN LACR,Reach-1,1
Up Type=0
Dn Type=3
Dn Slope=0.005
Boundary for River Rch & Prof#=UNT 0431 IN LACR,Reach-1,2
Up Type=0
Dn Type=3
Dn Slope=0.005
Boundary for River Rch & Prof#=UNT 0431 IN LACR,Reach-1,3
Up Type=0
Dn Type=3
Dn Slope=0.005
Boundary for River Rch & Prof#=UNT 0431 IN LACR,Reach-1,4
Up Type=0
Dn Type=3
Dn Slope=0.005
Boundary for River Rch & Prof#=UNT 0431 IN LACR,Reach-1,5
Up Type=0
Dn Type=3
Dn Slope=0.005
Boundary for River Rch & Prof#=UNT 0431 IN LACR,Reach-1,6
Up Type=0
Dn Type=3
Dn Slope=0.005
Boundary for River Rch & Prof#=UNT 0431 IN LACR,Reach-1,7
Up Type=0
Dn Type=3
Dn Slope=0.005

--- UNT 0431 IN LACR.g01 (geometry) ---

Geom Title=Existing Conditions

River Reach=UNT 0431 IN LACR,Reach-1
Reach XY= 30
      3673605.50     10615911.00      3674051.75     10616171.00
      3674145.50     10616156.00      3674307.75     10616388.00
      3674655.00     10616318.00      3674647.25     10616213.00
      3674753.25     10616126.00      3675140.25     10616298.00
      3675758.25     10616333.00      3676233.75     10616698.00
      3676279.75     10616960.00      3676532.75     10617224.00
      3676939.00     10617508.00      3677143.75     10617761.00
      3677507.75     10617885.00      3677667.25     10617365.00
      3677781.25     10617250.00      3677949.75     10616330.00
      3678165.75     10615939.00      3678584.00     10614797.00
      3679549.50     10613301.00      3679539.50     10613020.00
      3679625.00     10612838.00      3680116.25     10612163.00
      3680369.50     10612034.00      3680638.00     10611328.00
      3680827.75     10611289.00      3680804.75     10611127.00
      3680924.50     10611096.00      3681004.24     10610955.47

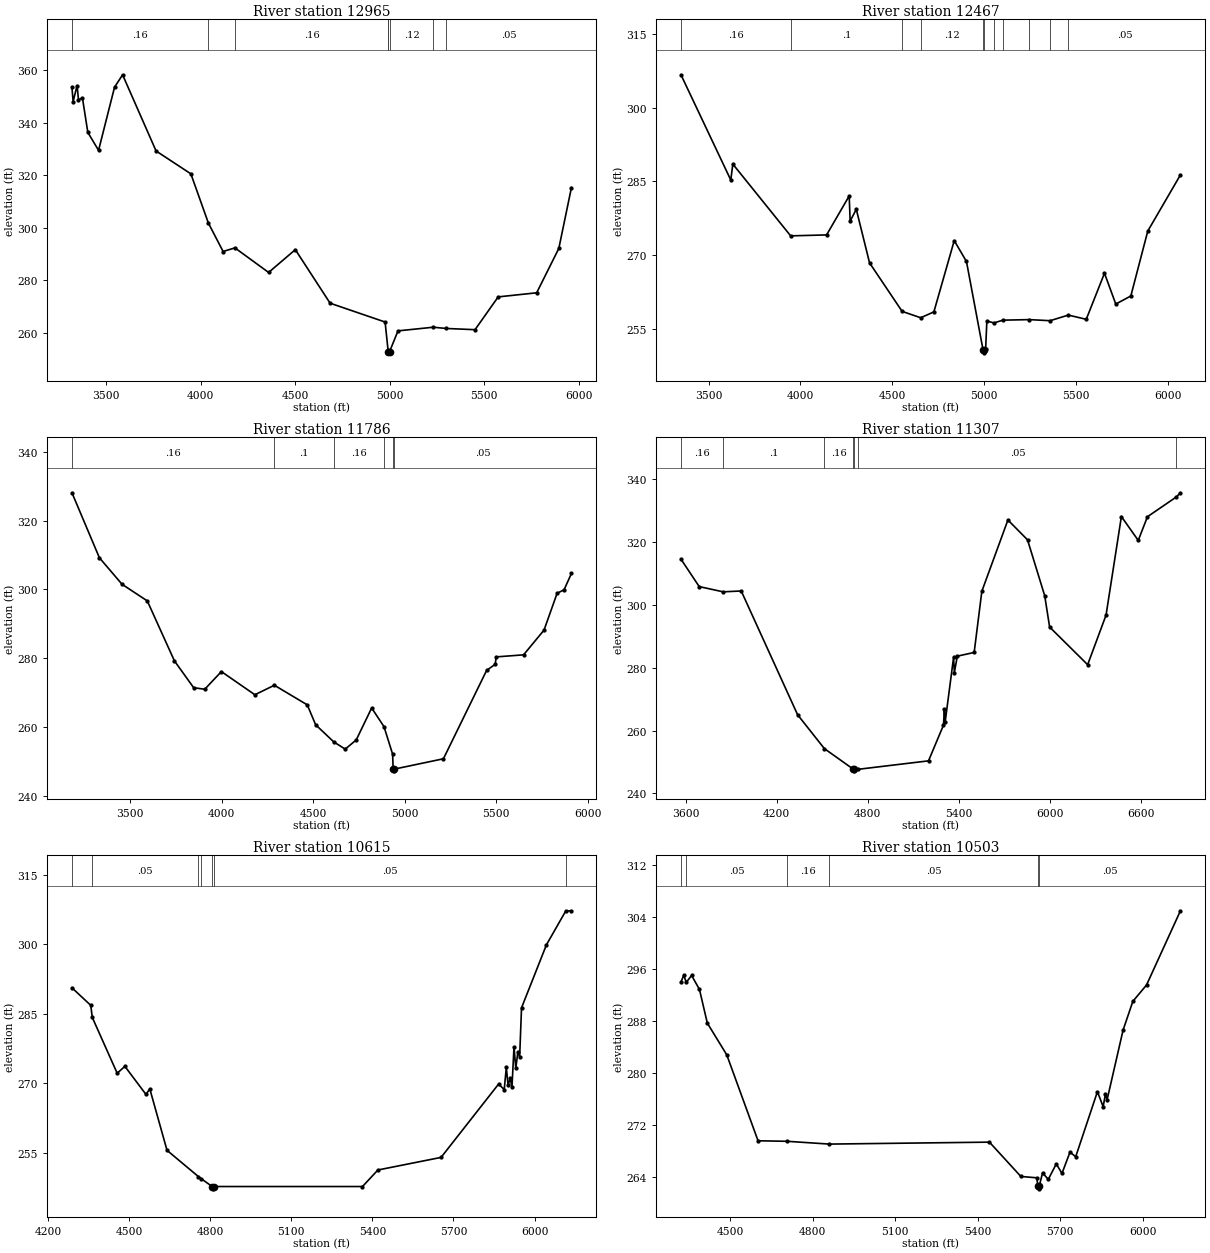
Type RM Length L Ch R = 1,12965,498,498,498
BEGIN DESCRIPTION:
UNT 0431 IN LACR 27.0
END DESCRIPTION:
XS GIS Cut Line= 3
      3672762.84     10617261.81      3674015.25     10616141.00
      3674399.60     10615260.21
#Sta/Elev= 30
  3319.3  353.51  3325.5  348.15  3346.4  354.23  3353.9  348.85  3374.8  349.51
  3403.2  336.39  3460.0  329.53  3544.5  353.60  3587.1  358.35  3764.3  329.28
  3948.2  320.57  4041.0  301.77  4118.7  290.95  4181.1  292.33  4359.5  282.96
  4500.7  291.66  4684.7  271.23  4975.5  264.05  4991.0  253.40  4993.4  252.80
  4996.2  252.30  4999.4  252.80  5043.7  260.68  5230.4  262.07  5298.1  261.60
  5451.1  261.13  5573.6  273.64  5777.2  275.20  5894.3  292.12  5961.0  315.32
#Mann=8,-1,0
  3319.3    0.16       0  4041.0    0.05       0  4181.1    0.16       0
  4991.0    0.12       0  4993.4    0.07       0  4999.4    0.12       0
  5230.4    0.16       0  5298.1    0.05       0
Bank Sta=4993.4,4999.4
Exp/Cntr=0.3,0.1

Type RM Length L Ch R = 1,12467,681,681,681
BEGIN DESCRIPTION:
UNT 0431 IN LACR 26.0
END DESCRIPTION:
XS GIS Cut Line= 3
      3673856.56     10617970.15      3674346.31     10616297.97
      3674554.63     10615346.64
#Sta/Elev= 30
  3350.1  306.66  3621.0  285.28  3632.2  288.51  3946.6  273.93  4142.0  274.12
  4265.0  282.04  4270.2  276.93  4303.6  279.33  4375.7  268.44  4552.9  258.58
  4653.9  257.29  4725.5  258.48  4836.2  272.96  4902.7  268.73  4993.4  250.66
  4996.2  250.16  4999.4  250.66  5006.9  250.86  5013.7  256.63  5052.3  256.24
  5100.9  256.80  5244.9  256.91  5357.3  256.69  5456.8  257.83  5554.1  256.97
  5653.3  266.34  5714.7  260.07  5796.6  261.71  5888.7  274.90  6066.4  286.32
#Mann=11,-1,0
  3350.1    0.16       0  3946.6     0.1       0  4552.9    0.16       0
  4653.9    0.12       0  4993.4    0.07       0  4999.4    0.12       0
  5052.3    0.16       0  5100.9    0.12       0  5244.9    0.16       0
  5357.3    0.12       0  5456.8    0.05       0
Bank Sta=4993.4,4999.4
Exp/Cntr=0.3,0.1

Type RM Length L Ch R = 1,11786,479,479,479
BEGIN DESCRIPTION:
UNT 0431 IN LACR 25.0
END DESCRIPTION:
XS GIS Cut Line= 4
      3674497.17     10617928.53      3674710.72     10616397.26
      3674835.72     10616074.34      3674991.62     10615253.26
#Sta/Elev= 30
  3182.9  328.10  3332.7  309.20  3456.4  301.48  3594.4  296.64  3742.6  279.19
  3847.6  271.39  3908.2  270.94  3999.1  276.08  4181.9  269.34  4288.5  272.10
  4468.1  266.40  4514.0  260.60  4613.1  255.61  4675.5  253.52  4735.5  256.18
  4819.9  265.49  4887.2  260.06  4934.3  252.06  4937.3  247.70  4940.1  247.20
  4943.3  247.70  5211.8  250.71  5447.8  276.42  5494.9  278.21  5500.0  280.35
  5649.5  280.95  5761.3  288.14  5832.7  298.85  5870.9  299.89  5911.0  304.63
#Mann=6,-1,0
  3182.9    0.16       0  4288.5     0.1       0  4613.1    0.16       0
  4887.2    0.05       0  4937.3    0.03       0  4943.3    0.05       0
Bank Sta=4937.3,4943.3
Exp/Cntr=0.3,0.1

Type RM Length L Ch R = 1,11307,692,692,692
BEGIN DESCRIPTION:
Mapping XS 02db20c5
END DESCRIPTION:
XS GIS Cut Line= 3
      3674981.56     10617709.73      3675310.43     10615972.58
      3675528.41     10614465.06
#Sta/Elev= 30
  3568.7  314.63  3688.9  305.89  3846.4  304.22  3965.8  304.49  4337.2  265.07
  4513.6  254.28  4705.1  247.70  4707.9  247.20  4711.1  247.70  4738.2  247.70
  5199.8  250.38  5298.4  261.73  5304.5  266.75  5309.5  262.73  5365.1  283.34
  5370.2  278.49  5389.6  283.73  5500.7  284.91  5551.3  304.40  5723.1  327.10
  5852.2  320.79  5965.6  302.96  5997.9  293.00  6248.5  281.01  6369.7  296.79
  6470.8  328.20  6581.9  320.60  6642.5  328.14  6833.3  334.45  6859.9  335.77
#Mann=7,-1,0
  3568.7    0.16       0  3846.4     0.1       0  4513.6    0.16       0
  4705.1   0.033       0  4711.1    0.16       0  4738.2    0.05       0
  6833.3    0.08       0
Bank Sta=4705.1,4711.1
Exp/Cntr=0.3,0.1

Type RM Length L Ch R = 1,10615,112,112,112
BEGIN DESCRIPTION:
UNT 0431 IN LACR 22.0
END DESCRIPTION:
XS GIS Cut Line= 3
      3675447.01     10616943.77      3675488.67     10616787.55
      3676769.89     10615690.35
#Sta/Elev= 30
  4288.0  290.63  4357.6  286.84  4363.2  284.24  4455.4  272.17  4483.9  273.66
  4561.9  267.60  4576.1  268.80  4639.8  255.52  4756.1  249.84  4766.9  249.37
  4806.9  247.70  4809.7  247.20  4812.9  247.70  5363.2  247.70  5420.2  251.27
  5654.0  253.99  5867.0  269.84  5887.8  268.64  5895.5  273.44  5902.1  269.53
  5909.8  271.11  5916.4  269.11  5924.0  277.89  5930.6  273.21  5938.3  276.82
  5944.9  275.74  5951.8  286.30  6044.0  299.92  6115.3  307.21  6136.5  307.27
#Mann=7,-1,0
  4288.0    0.16       0  4363.2    0.05       0  4756.1    0.16       0
  4766.9    0.05       0  4806.9   0.033       0  4812.9    0.05       0
  6115.3    0.08       0
Bank Sta=4806.9,4812.9
Exp/Cntr=0.3,0.1

Type RM Length L Ch R = 1,10503,107,107,107
BEGIN DESCRIPTION:
Mapping XS 545b16b1
END DESCRIPTION:
XS GIS Cut Line= 3
      3675481.74     10616947.26      3675617.14     10616787.55
      3676894.77     10615811.97
#Sta/Elev= 30
  4320.4  294.00  4330.5  295.04  4339.7  293.94  4359.1  295.01  4387.7  292.85
  4416.3  287.66  4487.0  282.77  4600.8  269.52  4706.4  269.44  4860.1  269.01
  5442.5  269.31  5556.8  264.02  5614.9  263.81  5618.2  262.61  5621.0  262.11
  5624.2  262.61  5635.7  264.57  5656.6  263.57  5685.6  265.95  5706.4  264.49
  5735.5  267.77  5756.3  267.06  5835.3  277.09  5856.1  274.78  5864.3  276.66
  5870.6  275.86  5928.7  286.59  5964.1  291.01  6014.0  293.54  6137.3  304.98
#Mann=6,-1,0
  4320.4    0.16       0  4339.7    0.05       0  4706.4    0.16       0
  4860.1    0.05       0  5618.2    0.03       0  5624.2    0.05       0
Bank Sta=5618.2,5624.2
Exp/Cntr=0.3,0.1

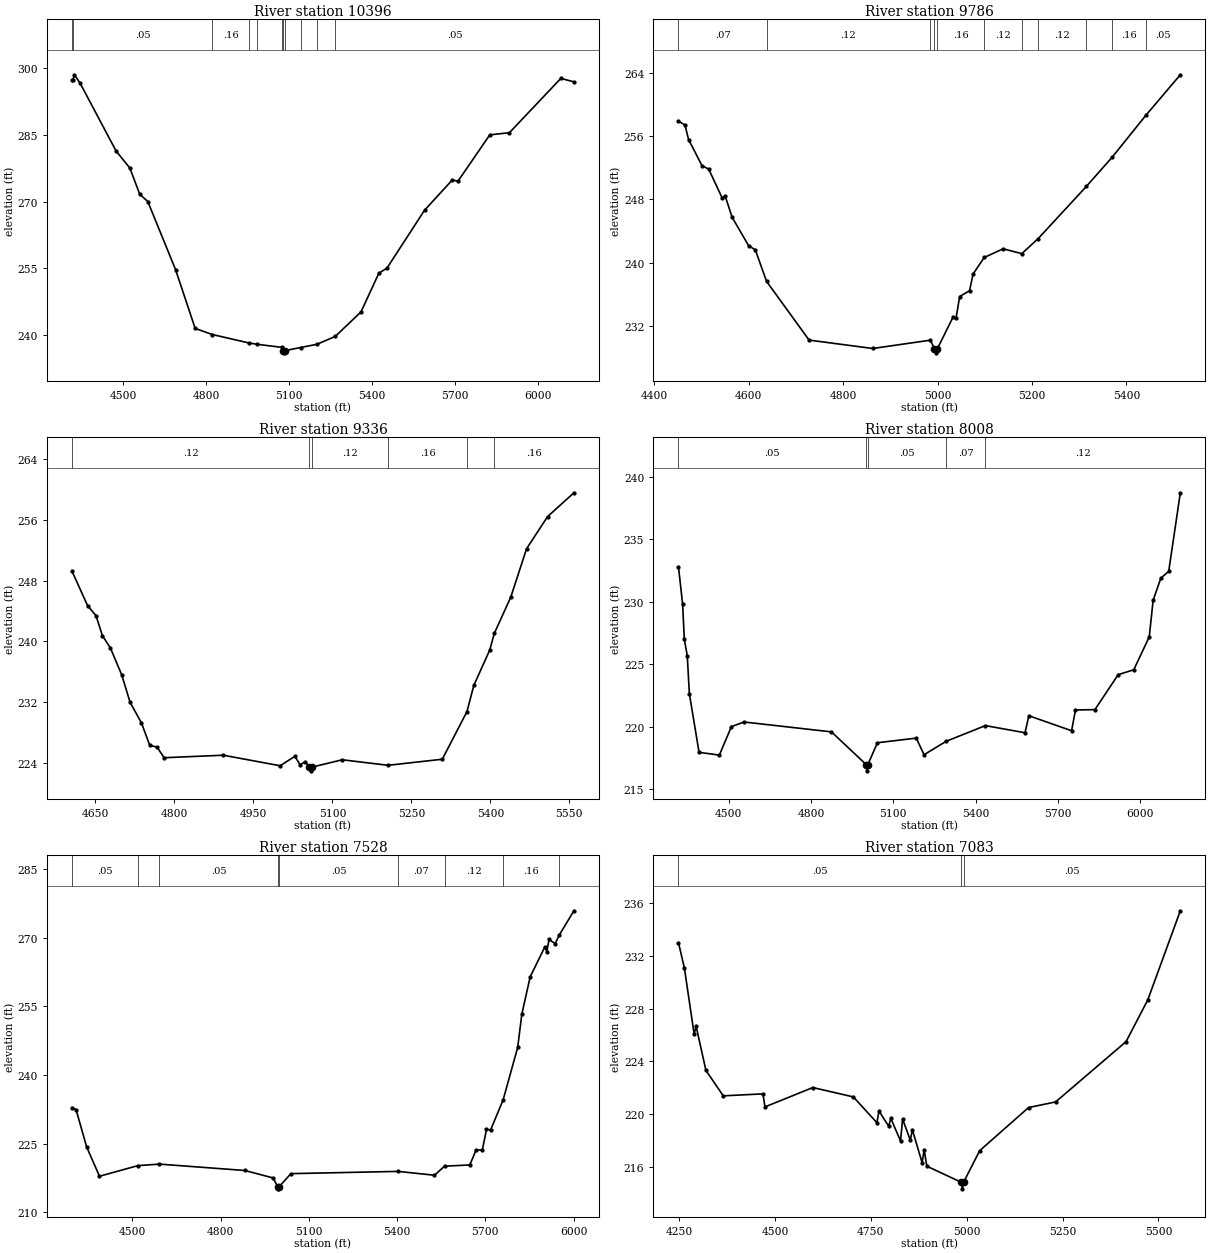
Type RM Length L Ch R = 1,10396,610,610,610
BEGIN DESCRIPTION:
UNT 0431 IN LACR 21.0
END DESCRIPTION:
XS GIS Cut Line= 2
      3675506.00     10616988.96      3676971.28     10615916.04
#Sta/Elev= 30
  4314.2  297.32  4316.8  297.32  4322.7  298.55  4343.6  296.62  4473.3  281.40
  4523.4  277.53  4559.0  271.65  4588.3  270.00  4688.6  254.68  4759.7  241.42
  4821.5  240.05  4953.8  238.15  4983.5  237.85  5073.9  237.15  5078.6  236.42
  5081.4  235.92  5084.6  236.42  5141.2  237.12  5200.1  237.84  5266.4  239.61
  5359.8  245.14  5424.4  253.86  5453.7  255.00  5589.6  268.03  5689.9  274.84
  5710.8  274.58  5825.8  285.02  5896.8  285.50  6082.9  297.73  6130.3  296.96
#Mann=11,-1,0
  4314.2     0.1       0  4316.8    0.05       0  4821.5    0.16       0
  4953.8    0.12       0  4983.5    0.16       0  5073.9    0.12       0
  5078.6    0.07       0  5084.6    0.12       0  5141.2    0.16       0
  5200.1    0.12       0  5266.4    0.05       0
Bank Sta=5078.6,5084.6
Exp/Cntr=0.3,0.1

Type RM Length L Ch R = 1,9786,450,450,450
BEGIN DESCRIPTION:
UNT 0431 IN LACR 20.0
END DESCRIPTION:
XS GIS Cut Line= 3
      3675949.59     10617410.21      3676349.61     10617060.19
      3676699.58     10616660.22
#Sta/Elev= 30
  4451.1  257.90  4464.9  257.37  4472.5  255.55  4501.0  252.25  4515.2  251.81
  4543.7  248.16  4550.3  248.37  4564.6  245.74  4599.7  242.13  4613.9  241.61
  4637.6  237.63  4727.8  230.20  4862.6  229.14  4984.6  230.19  4993.4  229.09
  4996.1  228.59  4999.4  229.09  5032.5  233.09  5039.1  233.01  5046.7  235.71
  5067.6  236.44  5075.2  238.56  5098.8  240.65  5138.8  241.74  5178.3  241.13
  5212.8  243.02  5315.1  249.63  5370.0  253.34  5441.2  258.62  5514.1  263.74
#Mann=11,-1,0
  4451.1    0.07       0  4637.6    0.12       0  4984.6    0.16       0
  4993.4    0.07       0  4999.4    0.16       0  5098.8    0.12       0
  5178.3    0.16       0  5212.8    0.12       0  5315.1    0.05       0
  5370.0    0.16       0  5441.2    0.05       0
Bank Sta=4993.4,4999.4
Exp/Cntr=0.3,0.1

Type RM Length L Ch R = 1,9336,1328,1328,1328
BEGIN DESCRIPTION:
UNT 0431 IN LACR 19.0
END DESCRIPTION:
XS GIS Cut Line= 3
      3676499.61     10617660.19      3676699.61     10617310.19
      3676699.61     10616760.20
#Sta/Elev= 30
  4605.6  249.23  4635.1  244.70  4651.0  243.39  4663.2  240.75  4678.3  239.14
  4699.9  235.58  4715.7  231.97  4737.3  229.25  4753.2  226.27  4766.8  226.06
  4780.5  224.65  4892.8  224.98  5000.8  223.59  5028.7  224.83  5038.7  223.72
  5048.7  224.13  5055.7  223.42  5058.5  222.92  5061.7  223.42  5118.7  224.38
  5205.6  223.65  5308.7  224.45  5355.6  230.74  5368.7  234.21  5398.7  238.83
  5407.7  241.08  5438.7  245.81  5468.7  252.20  5508.7  256.45  5558.7  259.59
#Mann=6,-1,0
  4605.6    0.12       0  5055.7    0.07       0  5061.7    0.12       0
  5205.6    0.16       0  5355.6    0.12       0  5407.7    0.16       0
Bank Sta=5055.7,5061.7
Exp/Cntr=0.3,0.1

Type RM Length L Ch R = 1,8008,480,480,480
BEGIN DESCRIPTION:
UNT 0431 IN LACR 18.0
END DESCRIPTION:
XS GIS Cut Line= 3
      3678249.60     10617910.19      3677599.61     10617660.19
      3676799.60     10616860.18
#Sta/Elev= 30
  4317.6  232.82  4332.6  229.82  4339.0  226.99  4349.7  225.68  4357.2  222.65
  4392.6  217.95  4466.5  217.73  4510.4  220.01  4556.5  220.38  4874.7  219.59
  5001.4  216.97  5004.1  216.47  5007.4  216.97  5042.3  218.72  5183.7  219.09
  5212.0  217.76  5293.1  218.84  5435.4  220.09  5579.7  219.52  5593.8  220.88
  5749.4  219.68  5763.5  221.34  5834.3  221.37  5919.1  224.17  5975.7  224.56
  6032.2  227.19  6046.4  230.13  6074.7  231.91  6103.0  232.43  6145.4  238.73
#Mann=5,-1,0
  4317.6    0.05       0  5001.4    0.03       0  5007.4    0.05       0
  5293.1    0.07       0  5435.4    0.12       0
Bank Sta=5001.4,5007.4
Exp/Cntr=0.3,0.1

Type RM Length L Ch R = 1,7528,445,445,445
BEGIN DESCRIPTION:
UNT 0431 IN LACR 17.0
END DESCRIPTION:
XS GIS Cut Line= 3
      3678349.65     10617660.22      3677799.61     10617260.19
      3677049.64     10616560.21
#Sta/Elev= 30
  4295.2  232.89  4308.8  232.46  4344.7  224.32  4388.4  217.91  4518.8  220.23
  4592.3  220.56  4882.2  219.17  4978.7  217.54  4993.6  215.66  4996.3  215.16
  4999.6  215.66  5039.1  218.48  5403.7  218.97  5527.1  218.13  5561.4  220.11
  5647.3  220.38  5668.8  223.68  5689.8  223.63  5704.0  228.14  5718.1  228.04
  5760.4  234.56  5810.0  246.04  5824.1  253.30  5852.5  261.47  5902.3  268.00
  5909.1  266.97  5916.5  269.63  5937.5  268.72  5950.6  270.52  6001.2  275.90
#Mann=9,-1,0
  4295.2    0.05       0  4518.8    0.07       0  4592.3    0.05       0
  4993.6    0.03       0  4999.6    0.05       0  5403.7    0.07       0
  5561.4    0.12       0  5760.4    0.16       0  5950.6    0.05       0
Bank Sta=4993.6,4999.6
Exp/Cntr=0.3,0.1

Type RM Length L Ch R = 1,7083,425,425,425
BEGIN DESCRIPTION:
UNT 0431 IN LACR 16.0
END DESCRIPTION:
XS GIS Cut Line= 3
      3678549.57     10617060.17      3677849.61     10616810.19
      3677449.64     10616410.22
#Sta/Elev= 30
  4248.3  233.02  4263.7  231.10  4289.1  226.09  4294.4  226.66  4319.9  223.32
  4365.1  221.39  4468.6  221.54  4473.9  220.55  4598.7  222.02  4704.3  221.31
  4765.9  219.35  4771.2  220.24  4796.7  219.08  4802.0  219.69  4827.5  217.96
  4832.8  219.63  4853.0  218.02  4858.3  218.82  4883.8  216.31  4889.1  217.30
  4896.0  216.05  4985.9  214.83  4988.7  214.33  4991.9  214.83  5034.0  217.23
  5161.3  220.50  5232.0  220.93  5415.8  225.51  5472.4  228.68  5557.2  235.44
#Mann=3,-1,0
  4248.3    0.05       0  4985.9    0.03       0  4991.9    0.05       0
Bank Sta=4985.9,4991.9
Exp/Cntr=0.3,0.1

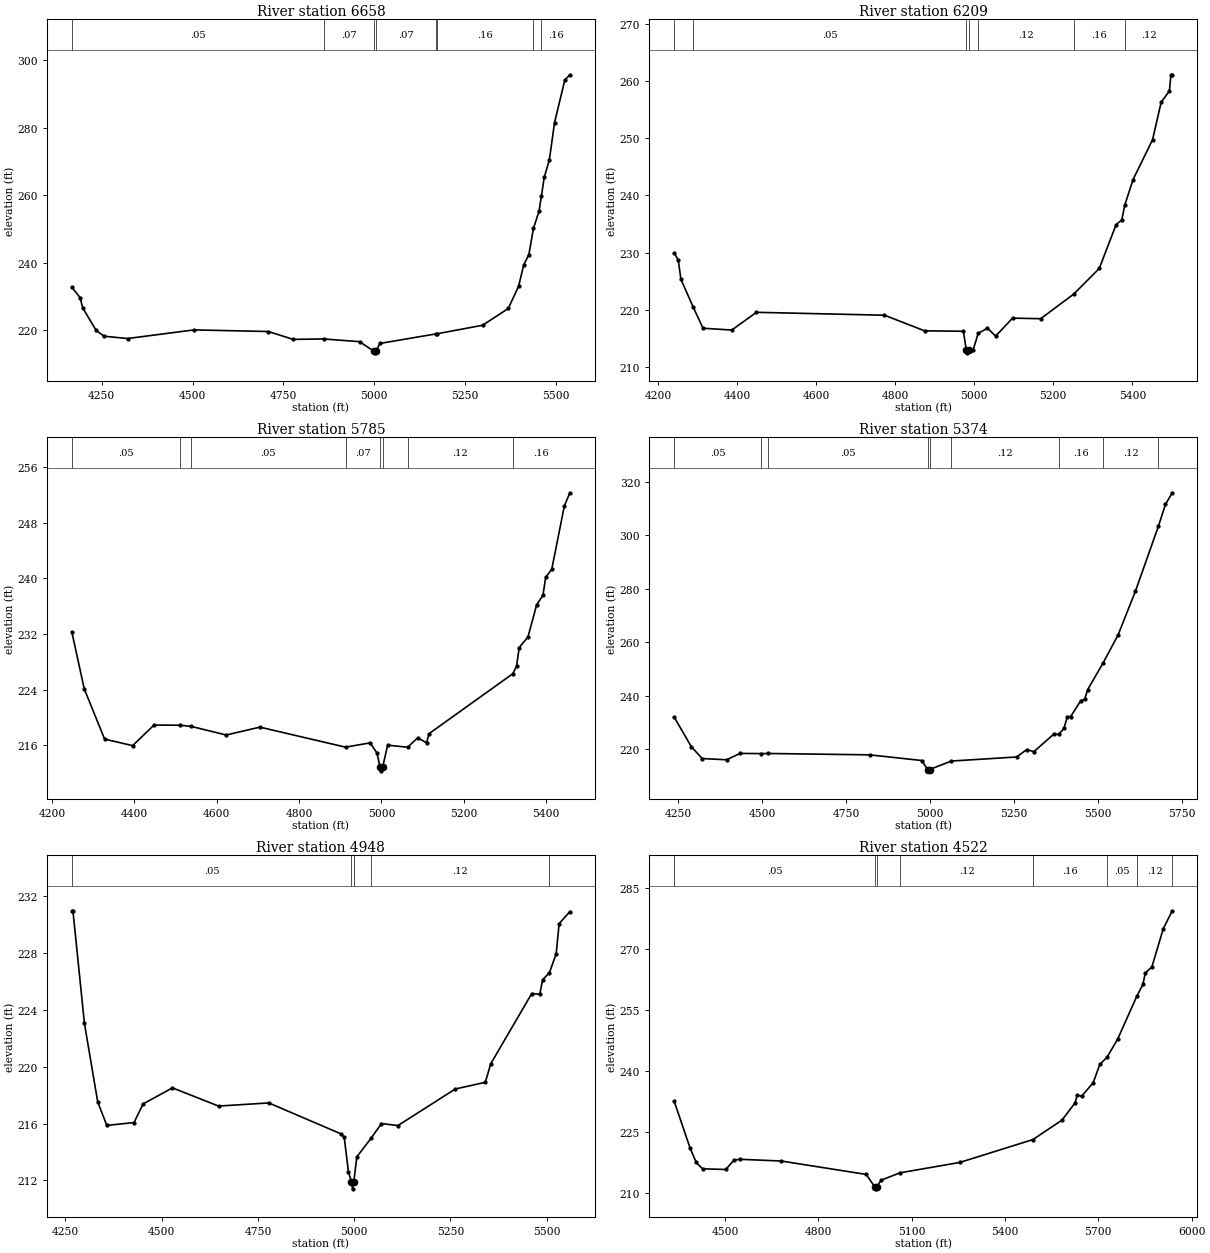
Type RM Length L Ch R = 1,6658,449,449,449
BEGIN DESCRIPTION:
UNT 0431 IN LACR 15.0
END DESCRIPTION:
XS GIS Cut Line= 3
      3678649.60     10616810.19      3677949.61     10616410.19
      3677549.61     10616010.19
#Sta/Elev= 30
  4167.7  232.72  4190.7  229.62  4197.2  226.67  4234.6  219.94  4256.2  218.22
  4321.0  217.53  4503.9  220.09  4709.0  219.61  4777.4  217.28  4860.9  217.41
  4960.2  216.60  4999.2  213.79  5002.0  213.29  5005.2  213.79  5016.3  216.08
  5169.9  218.89  5172.6  218.92  5299.2  221.47  5369.9  226.45  5398.2  233.01
  5412.3  239.32  5426.5  242.41  5439.2  250.17  5454.8  255.36  5461.2  259.88
  5468.9  265.32  5483.0  270.47  5497.2  281.52  5525.5  294.11  5539.6  295.70
#Mann=8,-1,0
  4167.7    0.05       0  4860.9    0.07       0  4999.2    0.07       0
  5005.2    0.07       0  5169.9    0.12       0  5172.6    0.16       0
  5439.2    0.12       0  5461.2    0.16       0
Bank Sta=4999.2,5005.2
Exp/Cntr=0.3,0.1

Type RM Length L Ch R = 1,6209,424,424,424
BEGIN DESCRIPTION:
UNT 0431 IN LACR 14.0
END DESCRIPTION:
XS GIS Cut Line= 3
      3678849.59     10616210.18      3678149.61     10616010.19
      3677749.60     10615660.18
#Sta/Elev= 30
  4241.4  229.94  4251.8  228.62  4258.3  225.32  4289.7  220.40  4314.2  216.74
  4387.0  216.42  4449.4  219.53  4773.1  219.02  4874.5  216.29  4972.7  216.21
  4980.1  212.93  4982.9  212.43  4986.1  212.93  4997.4  212.93  5010.1  215.84
  5033.5  216.75  5054.3  215.36  5097.0  218.51  5168.2  218.41  5251.9  222.73
  5316.3  227.21  5359.0  234.90  5373.2  235.70  5380.7  238.28  5401.7  242.77
  5451.1  249.76  5472.9  256.33  5493.8  258.33  5497.6  261.14  5500.9  261.14
#Mann=7,-1,0
  4241.4    0.07       0  4289.7    0.05       0  4980.1    0.03       0
  4986.1    0.05       0  5010.1    0.12       0  5251.9    0.16       0
  5380.7    0.12       0
Bank Sta=4980.1,4986.1
Exp/Cntr=0.3,0.1

Type RM Length L Ch R = 1,5785,411,411,411
BEGIN DESCRIPTION:
UNT 0431 IN LACR 13.0
END DESCRIPTION:
XS GIS Cut Line= 3
      3678949.60     10615960.18      3678299.61     10615610.19
      3677899.63     10615360.20
#Sta/Elev= 30
  4248.1  232.26  4278.1  224.12  4327.6  216.90  4395.7  215.96  4447.7  218.92
  4510.9  218.89  4537.5  218.73  4622.9  217.49  4704.8  218.62  4913.0  215.74
  4972.5  216.36  4989.3  214.90  4996.9  212.84  4999.6  212.34  5002.9  212.84
  5015.2  216.03  5063.7  215.73  5088.3  217.09  5109.6  216.37  5116.0  217.69
  5319.2  226.29  5328.3  227.34  5334.8  230.06  5356.0  231.56  5377.2  236.19
  5392.6  237.57  5399.1  240.15  5413.8  241.27  5444.5  250.41  5458.0  252.29
#Mann=8,-1,0
  4248.1    0.05       0  4510.9    0.07       0  4537.5    0.05       0
  4913.0    0.07       0  4996.9    0.07       0  5002.9    0.07       0
  5063.7    0.12       0  5319.2    0.16       0
Bank Sta=4996.9,5002.9
Exp/Cntr=0.3,0.1

Type RM Length L Ch R = 1,5374,426,426,426
BEGIN DESCRIPTION:
UNT 0431 IN LACR 12.0
END DESCRIPTION:
XS GIS Cut Line= 3
      3679149.56     10615410.18      3678449.61     10615210.19
      3677699.61     10615310.19
#Sta/Elev= 30
  4237.6  232.06  4288.3  221.06  4320.8  216.59  4393.6  216.11  4433.9  218.49
  4495.2  218.43  4518.3  218.47  4820.0  217.96  4975.7  215.84  4992.8  212.48
  4995.6  211.98  4998.8  212.48  5063.8  215.64  5258.1  217.16  5288.4  219.91
  5309.8  219.16  5369.1  225.72  5383.8  225.59  5399.4  227.87  5409.5  232.25
  5419.5  232.30  5449.8  238.26  5461.2  238.69  5470.0  242.34  5516.0  252.30
  5560.8  262.82  5612.5  279.18  5680.9  303.43  5702.0  311.64  5722.2  315.96
#Mann=9,-1,0
  4237.6    0.05       0  4495.2    0.07       0  4518.3    0.05       0
  4992.8    0.03       0  4998.8    0.05       0  5063.8    0.12       0
  5383.8    0.16       0  5516.0    0.12       0  5680.9    0.16       0
Bank Sta=4992.8,4998.8
Exp/Cntr=0.3,0.1

Type RM Length L Ch R = 1,4948,426,426,426
BEGIN DESCRIPTION:
UNT 0431 IN LACR 11.0
END DESCRIPTION:
XS GIS Cut Line= 3
      3679249.56     10615110.17      3678549.61     10614810.19
      3678149.64     10614460.21
#Sta/Elev= 30
  4267.1  230.96  4269.8  230.96  4299.7  223.04  4334.1  217.53  4357.7  215.87
  4428.4  216.07  4452.0  217.38  4528.2  218.51  4647.8  217.23  4778.4  217.45
  4967.0  215.26  4974.2  215.03  4985.1  212.60  4993.0  211.91  4995.7  211.41
  4999.0  211.91  5006.9  213.66  5044.5  214.99  5070.9  216.00  5113.6  215.86
  5262.6  218.43  5340.4  218.90  5354.7  220.21  5461.0  225.14  5481.8  225.09
  5489.4  226.12  5506.9  226.60  5524.5  227.95  5532.1  230.06  5560.1  230.90
#Mann=5,-1,0
  4267.1    0.05       0  4993.0    0.03       0  4999.0    0.05       0
  5044.5    0.12       0  5506.9    0.16       0
Bank Sta=4993,4999
Exp/Cntr=0.3,0.1

Type RM Length L Ch R = 1,4522,427,427,427
BEGIN DESCRIPTION:
UNT 0431 IN LACR 10.0
END DESCRIPTION:
XS GIS Cut Line= 3
      3679449.59     10614560.19      3678799.61     10614460.19
      3677999.63     10613960.20
#Sta/Elev= 30
  4336.6  232.58  4387.2  221.18  4407.4  217.56  4427.6  216.00  4502.3  215.83
  4528.8  218.14  4549.0  218.33  4680.6  217.91  4953.8  214.62  4981.1  211.58
  4983.9  211.08  4987.1  211.58  5001.9  213.21  5062.7  215.02  5254.2  217.55
  5489.5  223.17  5583.3  227.96  5625.7  232.25  5631.6  234.02  5646.9  233.87
  5683.5  237.14  5704.7  241.62  5727.9  243.38  5762.5  247.91  5823.7  258.37
  5843.3  261.25  5850.9  264.07  5872.2  265.58  5908.7  274.93  5937.6  279.35
#Mann=8,-1,0
  4336.6    0.05       0  4981.1    0.03       0  4987.1    0.05       0
  5062.7    0.12       0  5489.5    0.16       0  5727.9    0.05       0
  5823.7    0.12       0  5937.6    0.16       0
Bank Sta=4981.1,4987.1
Exp/Cntr=0.3,0.1

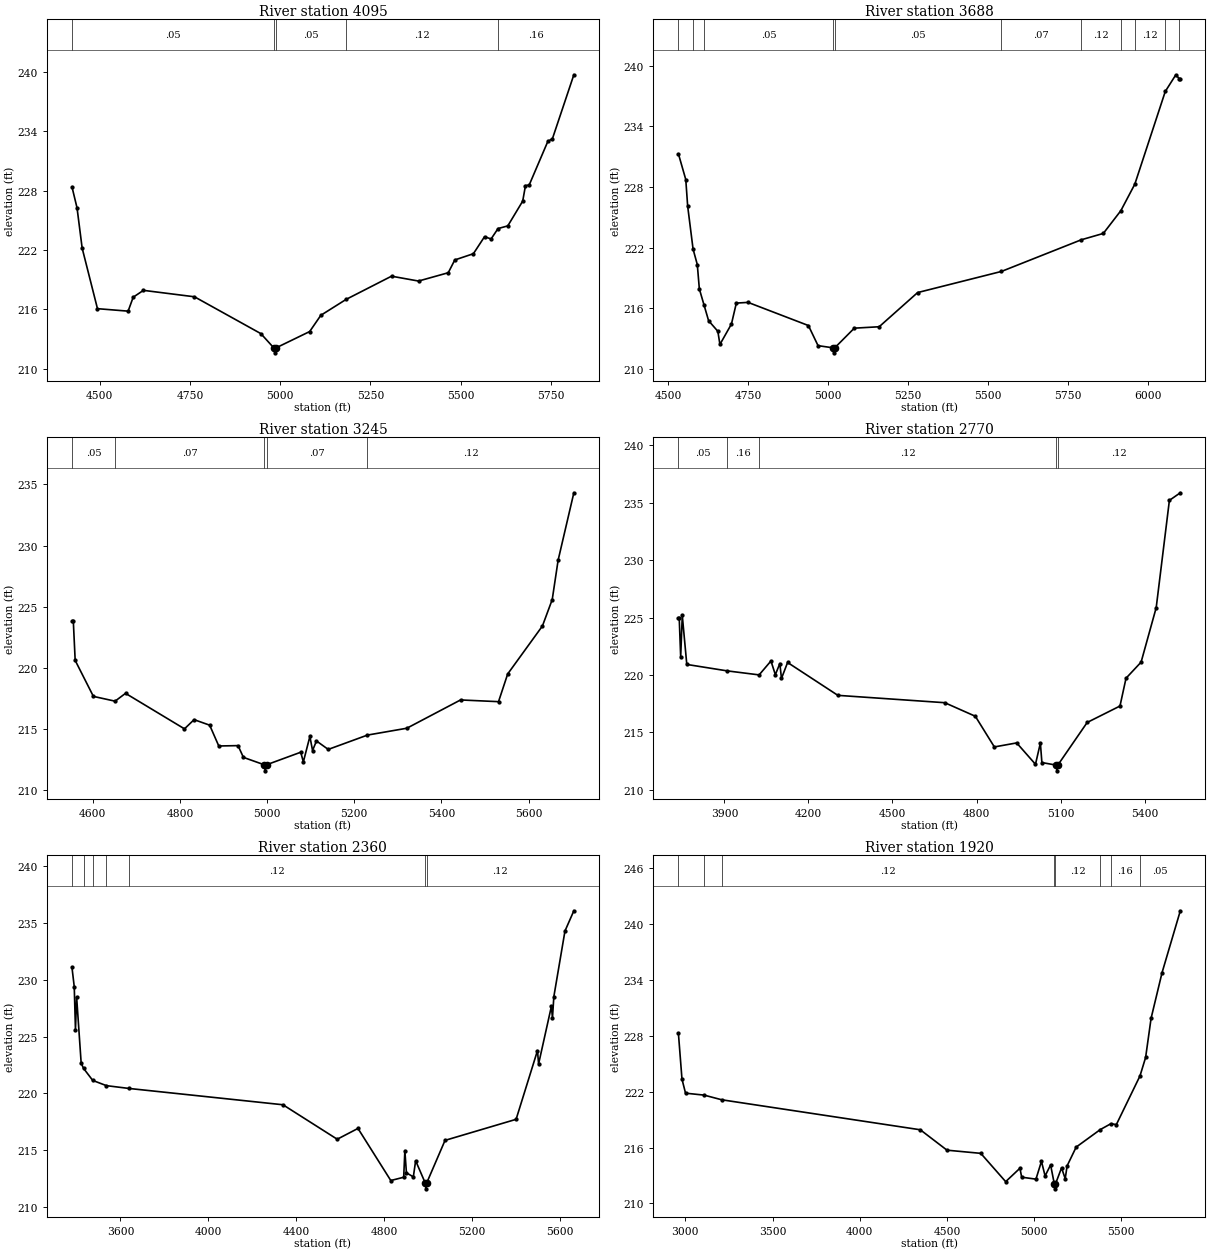
Type RM Length L Ch R = 1,4095,407,407,407
BEGIN DESCRIPTION:
UNT 0431 IN LACR 9.0
END DESCRIPTION:
XS GIS Cut Line= 3
      3679449.61     10614510.19      3679049.61     10614110.19
      3678249.62     10613910.19
#Sta/Elev= 30
  4423.1  228.39  4437.2  226.26  4451.4  222.19  4493.8  216.08  4578.7  215.83
  4592.8  217.24  4621.1  217.93  4762.5  217.28  4946.4  213.56  4982.3  212.12
  4985.0  211.62  4988.3  212.12  5081.6  213.77  5112.5  215.41  5182.7  217.02
  5308.3  219.36  5383.1  218.87  5465.5  219.71  5483.6  221.00  5535.1  221.63
  5566.0  223.35  5584.1  223.12  5603.4  224.17  5630.4  224.44  5671.7  226.94
  5679.4  228.51  5689.7  228.57  5741.3  232.97  5754.1  233.25  5813.4  239.70
#Mann=5,-1,0
  4423.1    0.05       0  4982.3    0.03       0  4988.3    0.05       0
  5182.7    0.12       0  5603.4    0.16       0
Bank Sta=4982.3,4988.3
Exp/Cntr=0.3,0.1

Type RM Length L Ch R = 1,3688,443,443,443
BEGIN DESCRIPTION:
UNT 0431 IN LACR 8.0
END DESCRIPTION:
XS GIS Cut Line= 3
      3679649.60     10614010.18      3679249.61     10613760.19
      3678499.59     10612960.17
#Sta/Elev= 30
  4532.6  231.28  4555.6  228.74  4561.5  226.11  4578.4  221.86  4591.6  220.33
  4598.0  217.92  4612.2  216.38  4626.9  214.78  4655.8  213.73  4662.3  212.43
  4698.3  214.45  4713.6  216.52  4750.2  216.59  4938.8  214.30  4968.9  212.31
  5015.2  212.10  5018.0  211.60  5021.2  212.10  5082.2  214.04  5159.9  214.18
  5280.0  217.56  5541.9  219.65  5791.4  222.78  5860.3  223.41  5915.1  225.66
  5958.7  228.28  6053.9  237.45  6086.9  239.10  6098.2  238.69  6100.9  238.69
#Mann=11,-1,0
  4532.6    0.05       0  4578.4    0.07       0  4612.2    0.05       0
  5015.2    0.03       0  5021.2    0.05       0  5541.9    0.07       0
  5791.4    0.12       0  5915.1    0.16       0  5958.7    0.12       0
  6053.9     0.1       0  6098.2    0.12       0
Bank Sta=5015.2,5021.2
Exp/Cntr=0.3,0.1

Type RM Length L Ch R = 1,3245,475,475,475
BEGIN DESCRIPTION:
UNT 0431 IN LACR 7.0
END DESCRIPTION:
XS GIS Cut Line= 3
      3679749.64     10613760.23      3679499.61     10613410.19
      3679099.59     10612810.17
#Sta/Elev= 30
  4552.4  223.85  4555.5  223.85  4559.8  220.62  4601.6  217.68  4651.3  217.29
  4675.3  217.93  4810.5  215.03  4832.6  215.78  4868.3  215.33  4889.2  213.63
  4933.4  213.66  4945.7  212.70  4993.1  212.10  4995.8  211.60  4999.1  212.10
  5077.2  213.12  5083.2  212.33  5098.2  214.41  5104.3  213.26  5113.3  214.04
  5140.3  213.35  5230.2  214.52  5320.6  215.08  5443.8  217.39  5530.9  217.25
  5551.9  219.51  5631.6  223.43  5654.1  225.59  5667.6  228.80  5703.7  234.31
#Mann=5,-1,0
  4552.4    0.05       0  4651.3    0.07       0  4993.1    0.07       0
  4999.1    0.07       0  5230.2    0.12       0
Bank Sta=4993.1,4999.1
Exp/Cntr=0.3,0.1

Type RM Length L Ch R = 1,2770,410,410,410
BEGIN DESCRIPTION:
UNT 0431 IN LACR 6.0
END DESCRIPTION:
XS GIS Cut Line= 3
      3680199.61     10614060.20      3679599.61     10612960.19
      3679099.63     10612760.20
#Sta/Elev= 30
  3735.9  224.97  3738.8  224.97  3744.0  221.57  3749.7  225.18  3765.8  220.92
  3909.9  220.36  4024.0  220.01  4066.2  221.22  4081.9  220.03  4098.0  221.00
  4103.7  219.70  4125.6  221.09  4305.0  218.23  4686.6  217.59  4795.7  216.41
  4863.6  213.74  4943.3  214.09  5010.4  212.23  5027.9  214.08  5033.3  212.38
  5084.2  212.16  5086.9  211.66  5090.2  212.16  5194.9  215.87  5312.0  217.30
  5333.6  219.72  5387.4  221.12  5441.3  225.86  5488.4  235.20  5527.4  235.86
#Mann=5,-1,0
  3735.9    0.05       0  3909.9    0.16       0  4024.0    0.12       0
  5084.2    0.07       0  5090.2    0.12       0
Bank Sta=5084.2,5090.2
Exp/Cntr=0.3,0.1

Type RM Length L Ch R = 1,2360,440,440,440
BEGIN DESCRIPTION:
UNT 0431 IN LACR 5.0
END DESCRIPTION:
XS GIS Cut Line= 3
      3680299.61     10614160.19      3679799.61     10612610.19
      3679149.61     10612710.19
#Sta/Elev= 30
  3379.0  231.10  3389.5  229.38  3395.0  225.61  3400.3  228.48  3421.0  222.67
  3431.7  222.21  3473.7  221.15  3536.0  220.69  3640.4  220.44  4340.2  219.01
  4587.4  215.98  4681.9  216.93  4831.4  212.35  4890.2  212.64  4895.5  214.98
  4902.6  213.03  4934.1  212.67  4944.6  214.09  4988.6  212.12  4991.4  211.62
  4994.6  212.12  5078.5  215.88  5402.2  217.73  5499.6  223.77  5504.7  222.60
  5562.9  227.65  5567.9  226.66  5574.2  228.52  5624.8  234.28  5665.3  236.06
#Mann=7,-1,0
  3379.0    0.05       0  3431.7    0.16       0  3473.7    0.05       0
  3536.0    0.16       0  3640.4    0.12       0  4988.6    0.07       0
  4994.6    0.12       0
Bank Sta=4988.6,4994.6
Exp/Cntr=0.3,0.1

Type RM Length L Ch R = 1,1920,515,515,515
BEGIN DESCRIPTION:
UNT 0431 IN LACR 4.0
END DESCRIPTION:
XS GIS Cut Line= 3
      3680449.60     10614260.15      3680049.61     10612260.19
      3679799.62     10611460.21
#Sta/Elev= 30
  2960.3  228.26  2980.7  223.35  3001.1  221.84  3107.9  221.63  3208.7  221.13
  4347.2  217.91  4500.2  215.72  4693.9  215.38  4836.7  212.34  4918.3  213.78
  4928.5  212.82  5010.3  212.61  5041.8  214.52  5062.7  212.95  5094.2  214.14
  5115.8  212.07  5118.5  211.57  5121.8  212.07  5157.0  213.82  5178.0  212.66
  5189.0  214.04  5240.8  216.05  5379.0  217.93  5439.8  218.56  5471.3  218.47
  5606.7  223.69  5639.0  225.67  5670.4  229.88  5733.3  234.78  5838.0  241.42
#Mann=8,-1,0
  2960.3    0.05       0  3107.9    0.16       0  3208.7    0.12       0
  5115.8    0.07       0  5121.8    0.12       0  5379.0    0.07       0
  5439.8    0.16       0  5606.7    0.05       0
Bank Sta=5115.8,5121.8
Exp/Cntr=0.3,0.1

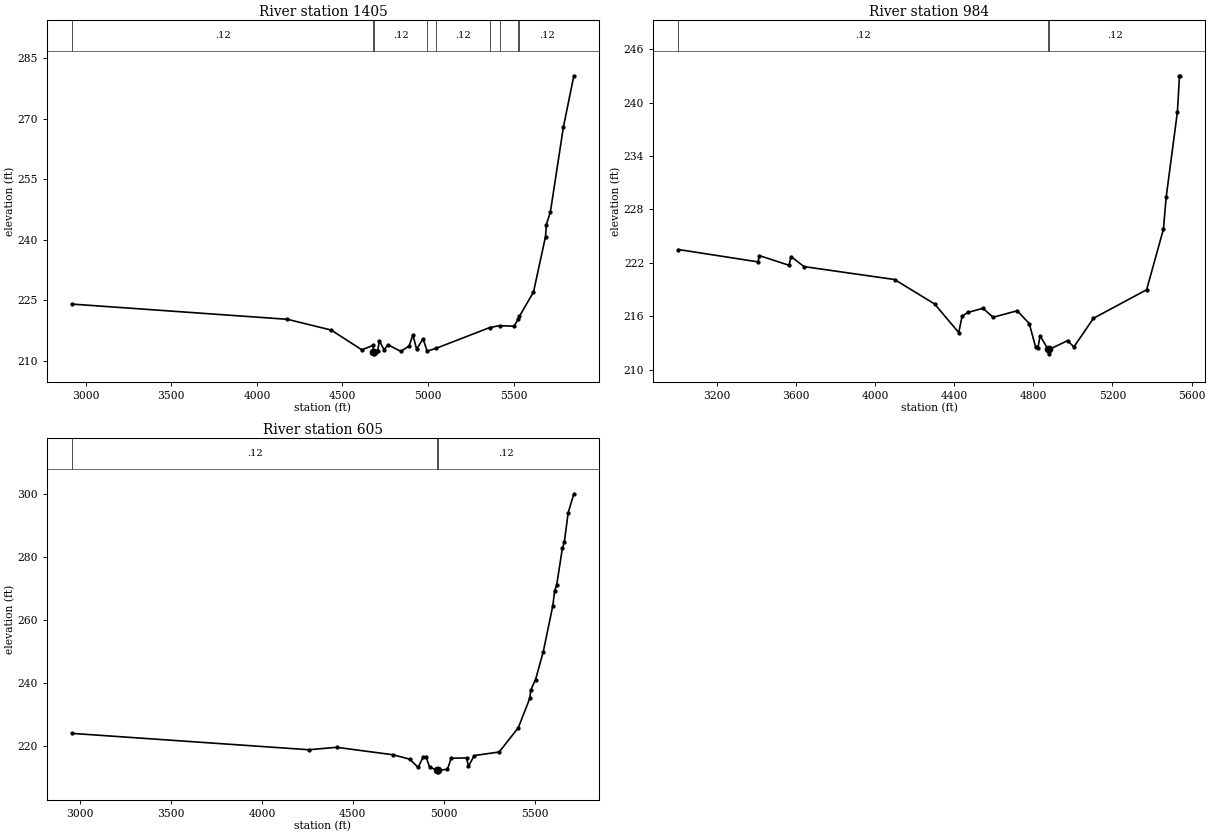
Type RM Length L Ch R = 1,1405,421,421,421
BEGIN DESCRIPTION:
UNT 0431 IN LACR 3.0
END DESCRIPTION:
XS GIS Cut Line= 3
      3681399.62     10613760.21      3680399.61     10611960.19
      3680049.59     10611160.15
#Sta/Elev= 30
  2919.7  224.03  4178.1  220.26  4434.3  217.58  4612.8  212.69  4678.0  213.77
  4680.7  212.19  4683.5  211.69  4686.7  212.19  4705.4  212.36  4715.7  214.95
  4743.2  212.63  4764.9  213.96  4840.4  212.31  4889.6  213.63  4911.4  216.41
  4933.1  212.83  4970.8  215.42  4994.8  212.37  5048.5  213.08  5360.5  218.21
  5418.0  218.68  5502.8  218.55  5526.9  220.31  5534.4  221.04  5616.2  227.02
  5686.4  240.76  5691.8  243.78  5715.2  246.98  5790.9  267.95  5852.1  280.68
#Mann=9,-1,0
  2919.7    0.12       0  4680.7    0.07       0  4686.7    0.12       0
  4994.8    0.07       0  5048.5    0.12       0  5360.5    0.16       0
  5418.0    0.12       0  5526.9    0.16       0  5534.4    0.12       0
Bank Sta=4680.7,4686.7
Exp/Cntr=0.3,0.1

Type RM Length L Ch R = 1,984,379,379,379
BEGIN DESCRIPTION:
UNT 0431 IN LACR 2.0
END DESCRIPTION:
XS GIS Cut Line= 3
      3681399.61     10613410.20      3680599.61     10611610.19
      3680199.59     10611210.17
#Sta/Elev= 30
  3006.8  223.50  3409.7  222.11  3415.1  222.82  3565.6  221.73  3575.9  222.71
  3641.5  221.58  4099.1  220.13  4301.5  217.38  4423.3  214.17  4440.4  216.03
  4469.8  216.43  4545.0  216.90  4597.0  215.89  4718.7  216.62  4779.6  215.18
  4811.8  212.54  4823.4  212.47  4834.3  213.80  4875.1  212.28  4877.8  211.78
  4881.1  212.28  4973.8  213.27  5004.9  212.55  5103.9  215.77  5372.6  218.98
  5457.4  225.78  5471.6  229.42  5528.1  238.95  5538.7  243.02  5542.3  243.02
#Mann=3,-1,0
  3006.8    0.12       0  4875.1    0.07       0  4881.1    0.12       0
Bank Sta=4875.1,4881.1
Exp/Cntr=0.3,0.1

Type RM Length L Ch R = 1,605,0,0,0
BEGIN DESCRIPTION:
UNT 0431 IN LACR 1.0
END DESCRIPTION:
XS GIS Cut Line= 3
      3681599.61     10613110.19      3680799.61     10611310.19
      3680049.65     10611060.20
#Sta/Elev= 30
  2955.4  224.09  4257.6  218.91  4410.8  219.68  4719.3  217.33  4812.3  215.94
  4858.8  213.32  4887.6  216.67  4903.3  216.49  4922.4  213.39  4964.3  212.41
  4967.1  211.91  4970.3  212.41  5020.0  212.70  5041.1  216.21  5125.4  216.32
  5136.0  213.67  5167.6  217.06  5304.6  218.19  5410.1  225.88  5473.3  235.21
  5478.6  237.84  5504.9  241.12  5547.1  249.89  5599.8  264.50  5610.3  269.32
  5620.9  270.99  5652.5  282.71  5663.0  284.58  5684.1  293.92  5715.7  299.99
#Mann=3,-1,0
  2955.4    0.12       0  4964.3    0.07       0  4970.3    0.12       0
Bank Sta=4964.3,4970.3
Exp/Cntr=0.3,0.1

Chan Stop Cuts=-1