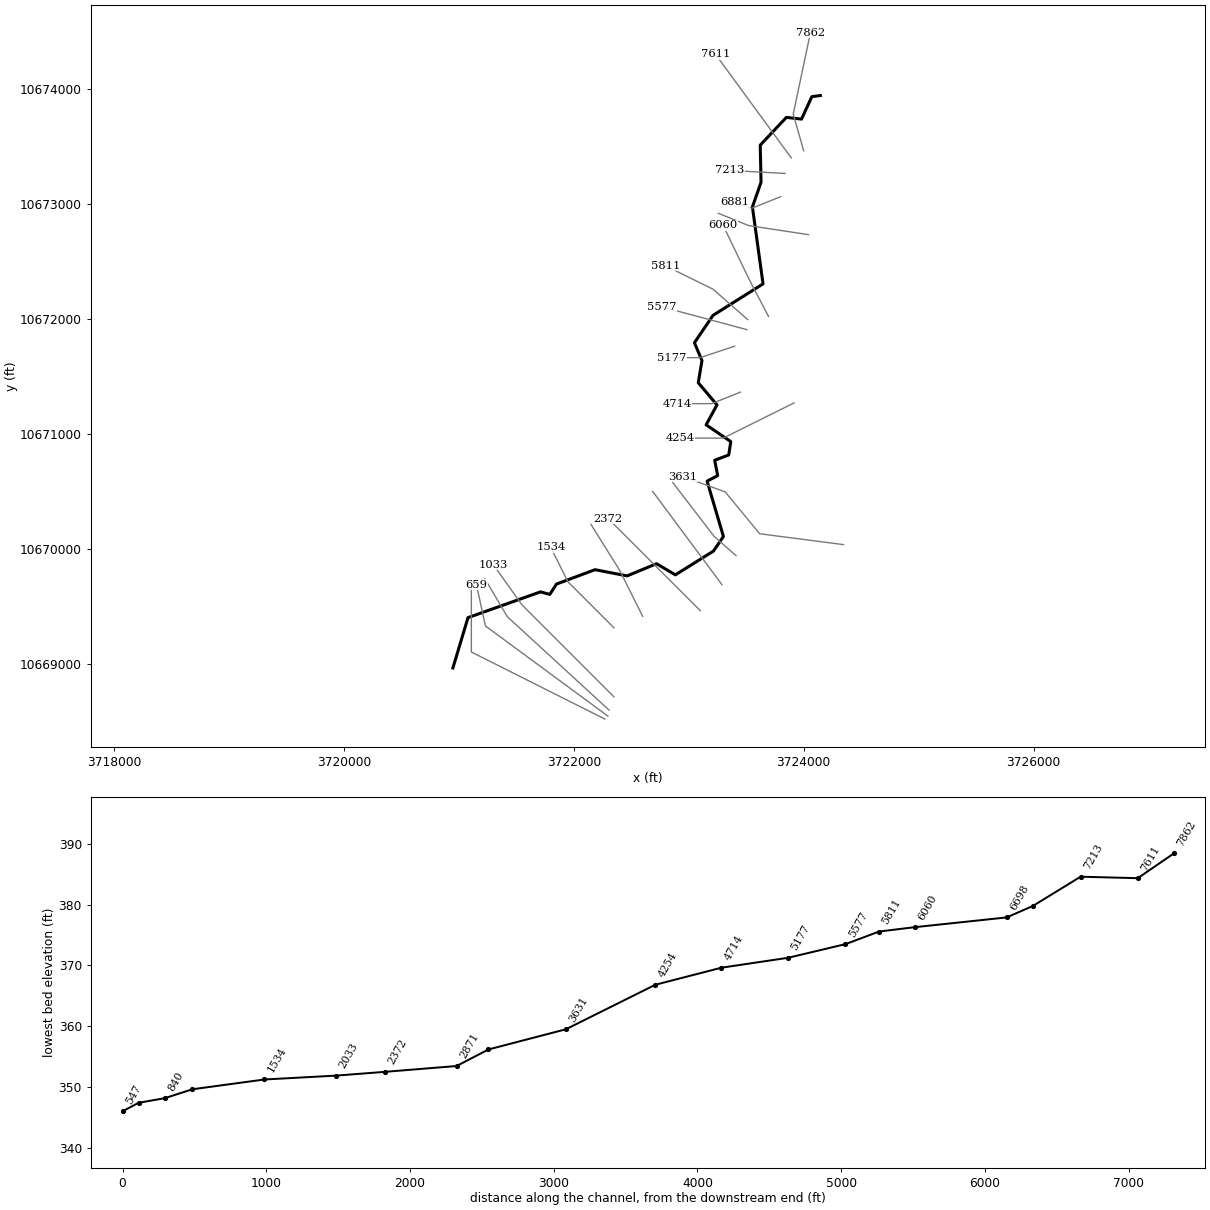
--- UNT 0476 IN LACR.prj (project) ---

Proj Title=UNT 0476 IN LACR Base Level Engineering
Current Plan=p01
Default Exp/Contr=0.3,0.1
English Units
Geom File=g01
Flow File=f01
Plan File=p01
Y Axis Title=Elevation
X Axis Title(PF)=Main Channel Distance
X Axis Title(XS)=Station
BEGIN DESCRIPTION:
UNT 0476 IN LACR
END DESCRIPTION:
DSS Export Rating Curves= 0
DSS Export Rating Curve Sorted= 0
DSS Export Volume Flow Curves= 0
DXF OffsetX= 0
DXF OffsetY= 0
DXF ScaleX= 1
DXF ScaleY= 10

--- UNT 0476 IN LACR.p01 (plan) ---

Plan Title=Multiple Run
Short Identifier=Multiple
Geom File=g01
Flow File=f01
Subcritical Flow
K Sum by GR= 0
Std Step Tol= 0.01
Critical Tol= 0.01
Num of Std Step Trials= 20
Max Error Tol= 0.3
Flow Tol Ratio= 0.001
Split Flow NTrial= 30
Split Flow Tol= 0.02
Split Flow Ratio= 0.02
Log Output Level= 0
Friction Slope Method= 1
Unsteady Friction Slope Method= 2
Unsteady Bridges Friction Slope Method= 1
Parabolic Critical Depth
Global Vel Dist=  1 , 1 , 1
Global Log Level= 0
CheckData=True
Encroach Param= -1, 0, 0, 0
BEGIN DESCRIPTION:
Multiple Run
END DESCRIPTION:

--- UNT 0476 IN LACR.f01 (steady flow) ---

Flow Title=Multiple
Program Version=4.10
Number of Profiles= 7
Profile Names=10-year,25-year,50-year,1pct_min,100-year,1pct_plu,500-year
River Rch & RM=UNT 0476 IN LACR,Reach-1         ,7862
     791    1105    1375    1258    1701    2300    2612
River Rch & RM=UNT 0476 IN LACR,Reach-1         ,3093
    1134    1612    2027    1873    2532    3425    3967
Boundary for River Rch & Prof#=UNT 0476 IN LACR,Reach-1         , 1
Up Type= 0
Dn Type= 3
Dn Slope=0.014
Boundary for River Rch & Prof#=UNT 0476 IN LACR,Reach-1         , 2
Up Type= 0
Dn Type= 3
Dn Slope=0.014
Boundary for River Rch & Prof#=UNT 0476 IN LACR,Reach-1         , 3
Up Type= 0
Dn Type= 3
Dn Slope=0.014
Boundary for River Rch & Prof#=UNT 0476 IN LACR,Reach-1         , 4
Up Type= 0
Dn Type= 3
Dn Slope=0.014
Boundary for River Rch & Prof#=UNT 0476 IN LACR,Reach-1         , 5
Up Type= 0
Dn Type= 3
Dn Slope=0.014
Boundary for River Rch & Prof#=UNT 0476 IN LACR,Reach-1         , 6
Up Type= 0
Dn Type= 3
Dn Slope=0.014
Boundary for River Rch & Prof#=UNT 0476 IN LACR,Reach-1         , 7
Up Type= 0
Dn Type= 3
Dn Slope=0.014
DSS Import GetInterval= 0
DSS Import GetPeak= 0
DSS Import FillOption= 0

--- UNT 0476 IN LACR.g01 (geometry) ---

Geom Title=Existing Conditions
Program Version=4.10

River Reach=UNT 0476 IN LACR,Reach-1
Reach XY= 30
      3724144.75       10673940.      3724070.75       10673930.
        3723981.       10673735.       3723849.5       10673750.
        3723622.       10673509.        3723629.       10673186.
        3723554.       10672971.      3723646.25       10672302.
      3723211.25       10672028.       3723049.5       10671790.
      3723115.25       10671635.        3723083.       10671442.
      3723245.75       10671249.      3723151.25       10671076.
      3723365.75       10670930.      3723347.86     10670813.48
      3723225.75       10670768.      3723251.75       10670634.
      3723159.75       10670586.      3723301.75       10670105.
       3723215.5       10669978.      3722883.75       10669771.
      3722719.75       10669868.      3722464.25       10669762.
      3722184.75       10669816.      3721849.75       10669691.
       3721791.5       10669601.      3721710.75       10669623.
      3721080.12     10669398.98      3720948.75       10668961.

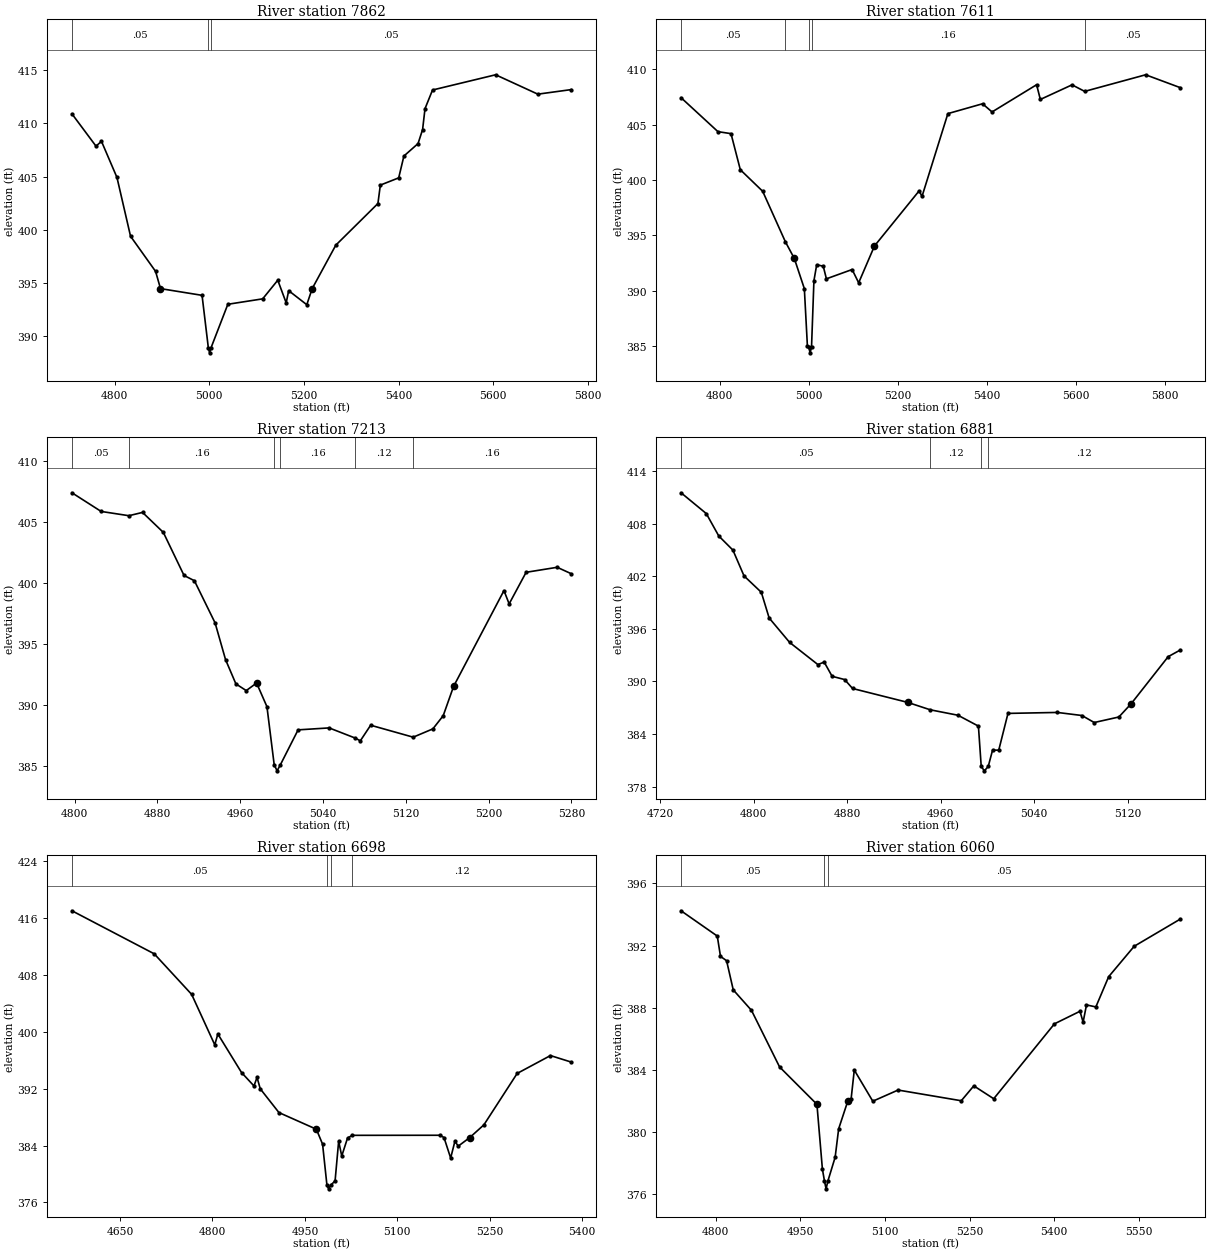
Type RM Length L Ch R = 1 ,7862    ,251,251,251
BEGIN DESCRIPTION:
UNT 0476 IN LACR 17.0
END DESCRIPTION:
XS GIS Cut Line= 3
      3723999.61     10673460.19      3723908.98     10673778.93
      3724058.69     10674487.11
#Sta/Elev= 30
    4710   410.9  4760.8  407.87  4772.4  408.32  4805.1  404.93  4833.8  399.41
  4886.7  396.11  4897.1  394.49  4984.9  393.86  4998.1  388.96  5000.8  388.46
  5004.1  388.96  5039.4  393.02    5113  393.53  5144.9  395.28  5162.7  393.15
  5167.9   394.3  5206.2  392.98  5217.6  394.49  5267.5  398.57  5356.5  402.48
  5361.6  404.21  5400.4  404.89  5411.4  406.94  5441.3  408.11  5450.9  409.43
    5456  411.39  5471.9  413.14  5605.2  414.57  5694.4  412.75  5765.2  413.18
#Mann= 3 ,-1 , 0
    4710     .05       0  4998.1     .03       0  5004.1     .05       0
Bank Sta=4897.1,5217.6
XS Rating Curve= 0 ,0
Exp/Cntr=0.3,0.1

Type RM Length L Ch R = 1 ,7611    ,398,398,398
BEGIN DESCRIPTION:
Mapping XS 725259c6
END DESCRIPTION:
XS GIS Cut Line= 2
      3723892.35     10673396.81      3723230.96     10674301.54
#Sta/Elev= 30
  4713.4  407.44  4796.2  404.37  4825.5  404.19  4846.4  400.93  4896.6  398.98
  4947.5  394.42  4967.6  392.91  4990.1  390.18    4997  384.96  5000.2  384.88
  5002.9  384.38  5006.2  384.88  5011.6   390.9  5017.8  392.34  5032.5  392.21
  5039.6  391.07  5097.3  391.91    5112  390.71  5147.5  394.04  5247.9  399.03
  5254.1  398.51  5312.2     406    5390  406.89  5411.3  406.15  5511.3  408.61
  5519.7  407.28  5590.8   408.6  5619.2  408.01    5756  409.51  5834.1  408.34
#Mann= 5 ,-1 , 0
  4713.4     .05       0  4947.5     .16       0  5000.2     .07       0
  5006.2     .16       0  5619.2     .05       0
Bank Sta=4967.6,5147.5
XS Rating Curve= 0 ,0
Exp/Cntr=0.3,0.1

Type RM Length L Ch R = 1 ,7213    ,332,332,332
BEGIN DESCRIPTION:
UNT 0476 IN LACR 16.0
END DESCRIPTION:
XS GIS Cut Line= 2
      3723837.75     10673262.47      3723355.96     10673288.51
#Sta/Elev= 30
  4797.5  407.42  4825.7  405.89  4852.5  405.54  4865.7  405.81  4885.8  404.17
  4905.8  400.64  4915.8  400.21  4935.8  396.75  4945.9  393.74  4955.9  391.75
  4965.9   391.2  4975.9  391.82  4985.9  389.88  4992.9  385.12  4995.7  384.62
  4998.9  385.12    5016  387.98    5046  388.14  5071.4   387.3  5076.1  387.08
  5086.1  388.36  5127.2  387.38  5146.2  388.06  5156.2  389.14  5166.2  391.54
  5214.9   399.4  5219.9  398.31  5236.3   400.9  5266.3  401.31    5280  400.78
#Mann= 6 ,-1 , 0
  4797.5     .05       0  4852.5     .16       0  4992.9     .07       0
  4998.9     .16       0  5071.4     .12       0  5127.2     .16       0
Bank Sta=4975.9,5166.2
XS Rating Curve= 0 ,0
Exp/Cntr=0.3,0.1

Type RM Length L Ch R = 1 ,6881    ,183,183,183
BEGIN DESCRIPTION:
UNT 0476 IN LACR 15.0
END DESCRIPTION:
XS GIS Cut Line= 3
      3723799.63      10673060.2      3723549.61     10672960.19
       3723399.6     10673010.19
#Sta/Elev= 30
  4737.7  411.51  4759.3  409.14    4770  406.58  4782.1  404.97  4791.6  402.03
  4806.4  400.16  4813.1  397.23  4830.6  394.45  4854.8  391.92  4860.2   392.2
    4867  390.58  4877.7  390.21  4884.5  389.19  4931.6  387.61    4951  386.76
  4974.7  386.14  4992.2   384.9  4994.6   380.3  4997.3   379.8  5000.6   380.3
  5004.3  382.16  5009.6  382.16  5017.5  386.35  5059.7  386.46  5080.8  386.11
  5091.3  385.31  5112.4  385.94  5122.9  387.45  5154.6  392.82  5165.1  393.59
#Mann= 4 ,-1 , 0
  4737.7     .05       0    4951     .12       0  4994.6     .07       0
  5000.6     .12       0
Bank Sta=4931.6,5122.9
XS Rating Curve= 0 ,0
Exp/Cntr=0.3,0.1

Type RM Length L Ch R = 1 ,6698    ,638,638,638
BEGIN DESCRIPTION:
UNT 0476 IN LACR 14.0
END DESCRIPTION:
XS GIS Cut Line= 3
      3724041.63     10672730.08      3723520.03     10672809.34
      3723258.17     10672915.64
#Sta/Elev= 30
  4572.1  416.99  4705.6  410.94  4766.3  405.24  4803.8  398.15  4808.8  399.67
  4847.2  394.26  4867.4  392.37  4872.4  393.57  4877.6  391.97  4907.9  388.63
  4968.6  386.29  4978.7  384.19  4985.8  378.41  4988.6  377.91  4991.8  378.41
    4999  379.03  5004.8  384.61  5009.8  382.52  5019.2  385.05  5026.8  385.43
  5169.3  385.44  5175.7  385.12  5186.5  382.24  5193.4   384.6  5198.8  383.91
  5217.5  385.12  5240.4   386.9  5294.4  394.13  5348.4  396.64  5382.3  395.72
#Mann= 4 ,-1 , 0
  4572.1     .05       0  4985.8     .03       0  4991.8     .05       0
  5026.8     .12       0
Bank Sta=4968.6,5217.5
XS Rating Curve= 0 ,0
Exp/Cntr=0.3,0.1

Type RM Length L Ch R = 1 ,6060    ,249,249,249
BEGIN DESCRIPTION:
UNT 0476 IN LACR 13.0
END DESCRIPTION:
XS GIS Cut Line= 3
       3723694.4     10672018.26      3723525.12     10672341.63
      3723299.61     10672810.19
#Sta/Elev= 30
  4738.8  394.24    4803  392.61  4808.7   391.3  4819.5  391.02  4831.3  389.14
  4863.6  387.82  4913.4  384.17  4979.6  381.76  4989.3  377.58    4993  376.81
  4995.8  376.31    4999  376.81  5011.9  378.35  5018.1  380.18  5034.4  381.98
  5040.1  382.08  5045.8  383.97  5078.6  381.96  5123.4  382.68  5235.4  381.99
  5257.6  382.95  5292.9  382.12  5400.5  386.95  5445.8  387.76  5451.3  387.06
  5457.3  388.17  5473.9  388.04  5496.6  389.99  5541.8  391.95  5623.8  393.71
#Mann= 3 ,-1 , 0
  4738.8     .05       0    4993     .03       0    4999     .05       0
Bank Sta=4979.6,5034.4
XS Rating Curve= 0 ,0
Exp/Cntr=0.3,0.1

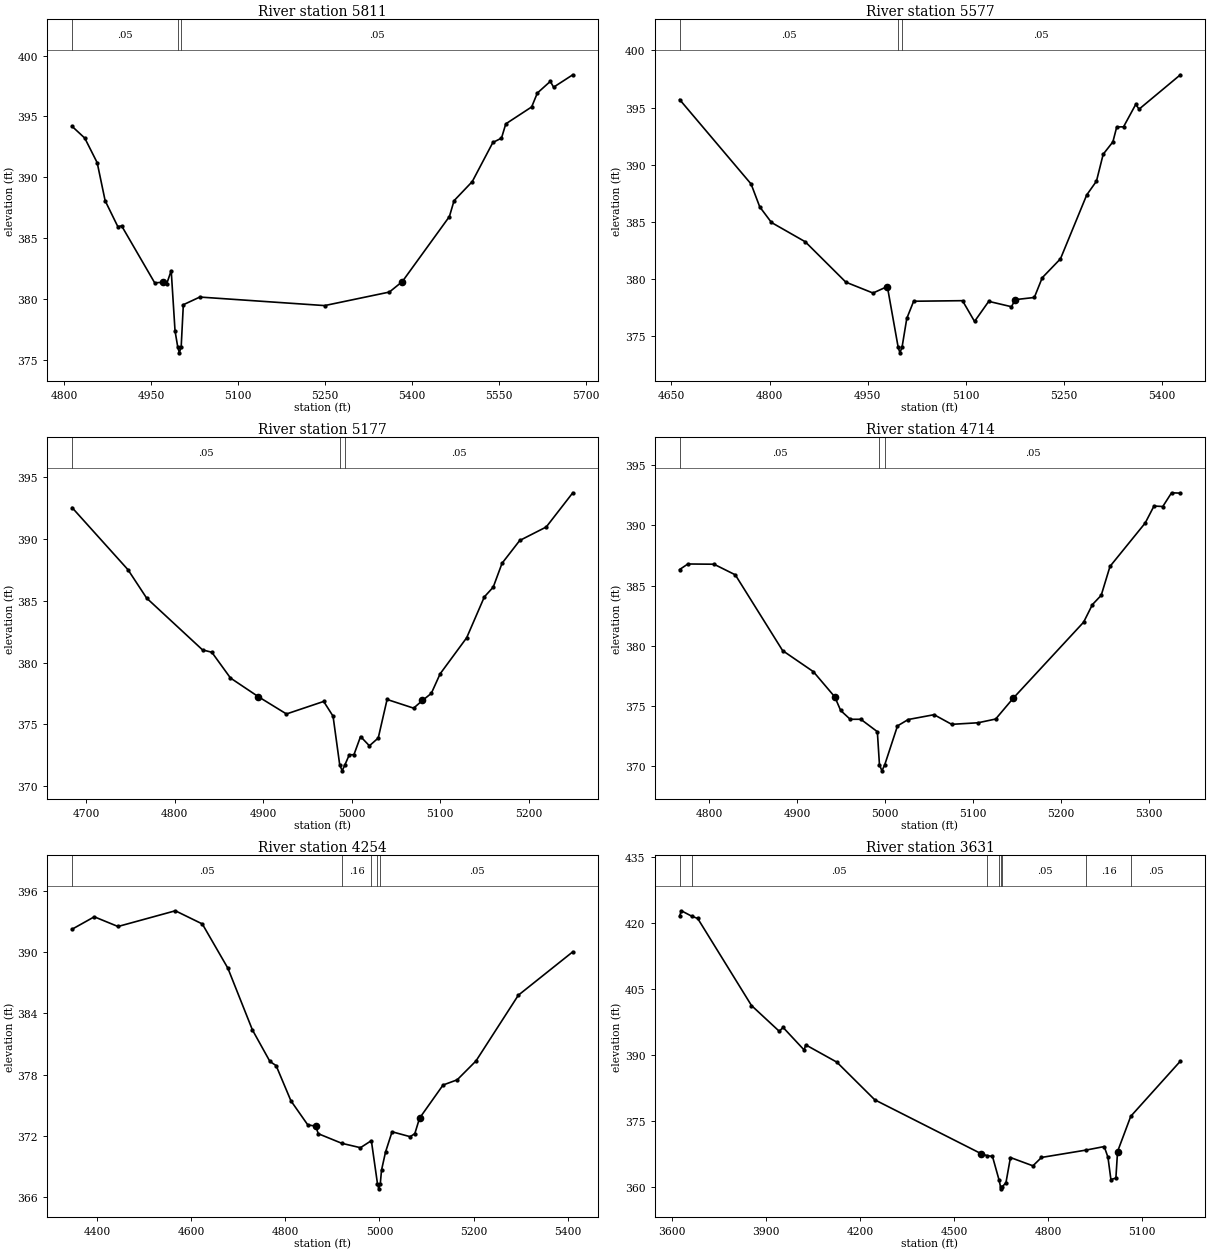
Type RM Length L Ch R = 1 ,5811    ,234,234,234
BEGIN DESCRIPTION:
Mapping XS 58dbd9ce
END DESCRIPTION:
XS GIS Cut Line= 3
      3723512.23     10671991.63      3723212.74     10672254.65
      3722796.06     10672460.39
#Sta/Elev= 30
  4813.4  394.19  4835.4  393.22  4856.8   391.2  4870.5  388.08  4892.3  385.96
    4899  386.01  4955.9  381.34  4970.1  381.38  4976.8  381.28  4984.4  382.34
    4991  377.39  4995.6  376.09  4998.4  375.59  5001.6  376.09  5005.3  379.54
  5033.7  380.17  5248.9  379.47  5360.5  380.58  5382.8  381.44    5464  386.78
    5472  388.08  5503.4  389.65  5538.9  392.86  5553.8  393.22  5561.2  394.39
  5605.8  395.78  5615.6  396.92    5638  397.88  5643.6   397.4  5676.7  398.42
#Mann= 3 ,-1 , 0
  4813.4     .05       0  4995.6     .03       0  5001.6     .05       0
Bank Sta=4970.1,5382.8
XS Rating Curve= 0 ,0
Exp/Cntr=0.3,0.1

Type RM Length L Ch R = 1 ,5577    ,400,400,400
BEGIN DESCRIPTION:
UNT 0476 IN LACR 12.0
END DESCRIPTION:
XS GIS Cut Line= 2
      3723505.21     10671904.12      3722765.63     10672102.04
#Sta/Elev= 30
  4662.5   395.7  4771.8   388.3    4785   386.3  4802.9  384.93  4854.6  383.24
  4916.7   379.7  4958.2  378.75  4980.1  379.32  4996.6  374.01  4999.3  373.51
  5002.6  374.01  5009.8  376.52  5020.3  378.03    5095  378.08  5113.4  376.26
  5135.1  378.02  5169.9  377.55  5175.5  378.17  5204.8  378.36  5216.9  380.09
  5244.8  381.75  5284.9  387.34  5299.8  388.55  5310.1  390.91  5324.9  391.99
  5330.8   393.3  5341.2  393.31  5359.8  395.27    5365  394.86  5428.1  397.87
#Mann= 3 ,-1 , 0
  4662.5     .05       0  4996.6     .03       0  5002.6     .05       0
Bank Sta=4980.1,5175.5
XS Rating Curve= 0 ,0
Exp/Cntr=0.3,0.1

Type RM Length L Ch R = 1 ,5177    ,463,463,463
BEGIN DESCRIPTION:
UNT 0476 IN LACR 11.0
END DESCRIPTION:
XS GIS Cut Line= 3
      3723399.63      10671760.2      3723099.61     10671660.19
      3722849.56     10671660.19
#Sta/Elev= 30
  4683.7  392.51    4747  387.49  4768.1   385.2  4831.3  381.02  4841.8  380.83
  4862.9  378.75  4894.5  377.24  4926.2  375.85  4968.3  376.86  4978.9  375.67
  4986.4  371.76  4989.2  371.26  4992.4  371.76  4997.3  372.56  5002.5  372.56
    5010  374.03    5020  373.28    5030  373.91    5040  377.02    5070  376.32
    5080  376.94    5090  377.51    5100  379.09    5130     382    5150   385.3
    5160  386.08    5170  388.01    5190  389.85    5220  390.94    5250   393.7
#Mann= 3 ,-1 , 0
  4683.7     .05       0  4986.4     .03       0  4992.4     .05       0
Bank Sta=4894.5,5080
XS Rating Curve= 0 ,0
Exp/Cntr=0.3,0.1

Type RM Length L Ch R = 1 ,4714    ,460,460,460
BEGIN DESCRIPTION:
UNT 0476 IN LACR 10.0
END DESCRIPTION:
XS GIS Cut Line= 3
      3723449.63      10671360.2      3723199.61     10671260.19
      3722899.59     10671260.19
#Sta/Elev= 30
  4766.6  386.34    4776   386.8  4805.7  386.78  4829.9   385.9  4883.7  379.61
  4918.7  377.86    4943  375.77  4949.7  374.64  4960.5  373.91  4972.6  373.91
  4991.4  372.88  4993.8  370.13  4996.6  369.63  4999.8  370.13  5014.3  373.36
  5026.5  373.89  5055.9  374.29  5075.9  373.49  5105.9  373.62  5125.9  373.93
  5145.9  375.66  5225.9  381.97  5235.9  383.43  5245.9   384.2  5255.9   386.6
  5295.9   390.2  5305.9  391.61  5315.9  391.57  5325.9  392.71  5335.9  392.68
#Mann= 3 ,-1 , 0
  4766.6     .05       0  4993.8     .03       0  4999.8     .05       0
Bank Sta=4943,5145.9
XS Rating Curve= 0 ,0
Exp/Cntr=0.3,0.1

Type RM Length L Ch R = 1 ,4254    ,623,623,623
BEGIN DESCRIPTION:
UNT 0476 IN LACR 9.0
END DESCRIPTION:
XS GIS Cut Line= 3
      3723916.26     10671266.62      3723299.61     10670960.19
       3722923.9     10670961.08
#Sta/Elev= 30
  4346.7  392.25    4394  393.47  4444.4  392.52  4566.3  394.06  4623.6  392.77
    4678  388.43  4730.1  382.39  4767.3   379.3  4780.5  378.89    4812  375.44
  4847.7  373.09  4864.5  372.96  4870.1  372.22  4920.1  371.28  4959.7  370.85
  4982.9  371.54  4995.9  367.32  4998.6  366.82  5001.9  367.32  5004.5  368.65
    5013  370.42  5026.9  372.41  5065.3  371.93  5075.3  372.23  5085.3  373.74
  5135.3  376.99  5165.3   377.5  5205.3  379.35  5295.3  385.79    5411  390.04
#Mann= 5 ,-1 , 0
  4346.7     .05       0  4920.1     .16       0  4982.9     .05       0
  4995.9     .03       0  5001.9     .05       0
Bank Sta=4864.5,5085.3
XS Rating Curve= 0 ,0
Exp/Cntr=0.3,0.1

Type RM Length L Ch R = 1 ,3631    ,538,538,538
BEGIN DESCRIPTION:
UNT 0476 IN LACR 8.0
END DESCRIPTION:
XS GIS Cut Line= 4
       3724346.8       10670034.      3723617.19      10670128.5
      3723317.68     10670492.18      3722951.45     10670625.56
#Sta/Elev= 30
  3624.9  421.61  3630.6   422.8  3663.4  421.57  3682.6  421.05    3854  401.23
  3942.6  395.36  3954.8  396.24  4021.9   391.1  4026.9  392.27  4126.2  388.33
  4247.2  379.75  4587.2  367.45  4604.5  367.06  4622.4  366.86  4643.3  361.52
    4648  359.98  4650.8  359.48    4654  359.98  4665.4  360.88  4679.7  366.61
  4751.4  364.72  4778.7  366.63    4922  368.32  4978.7  369.11  4990.6  366.67
    5000   361.6  5015.9  361.93  5021.2  367.97  5063.3     376  5221.5  388.56
#Mann= 8 ,-1 , 0
  3624.9     .08       0  3663.4     .05       0  4604.5     .16       0
  4643.3     .05       0    4648     .07       0    4654     .05       0
    4922     .16       0  5063.3     .05       0
Bank Sta=4587.2,5021.2
XS Rating Curve= 0 ,0
Exp/Cntr=0.3,0.1

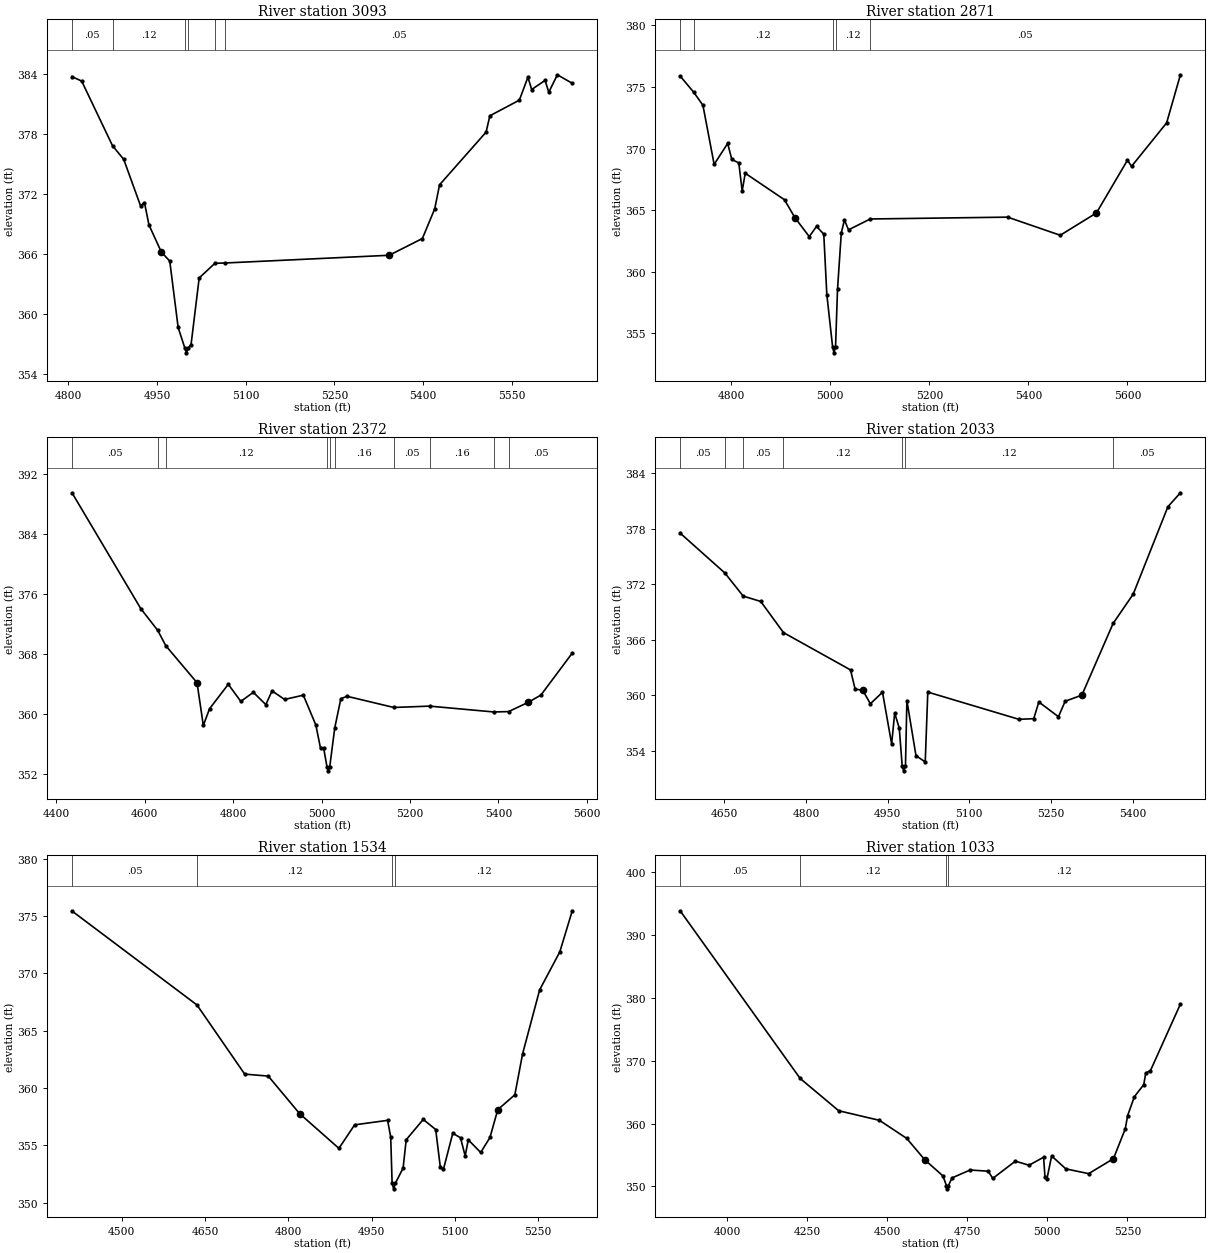
Type RM Length L Ch R = 1 ,3093    ,222,222,222
BEGIN DESCRIPTION:
UNT 0476 IN LACR 7.0
END DESCRIPTION:
XS GIS Cut Line= 3
      3723411.46     10669938.39      3723221.36     10670105.06
      3722859.82     10670575.84
#Sta/Elev= 30
  4806.1   383.7  4822.5  383.26  4874.7  376.81  4893.6  375.46  4922.1  370.82
  4928.7  371.15  4936.3  368.92  4957.2  366.22  4971.5  365.31  4985.7  358.69
  4996.9  356.66  4999.7  356.16  5002.9  356.66  5007.5  356.96  5021.3  363.63
  5047.9  365.09  5065.3  365.12  5342.8  365.89  5398.9  367.56  5419.8  370.52
    5428  372.92  5506.7  378.17  5513.1   379.8    5563  381.36  5577.5  383.65
  5583.8  382.42  5606.5  383.33  5612.8  382.15  5627.3  383.89  5652.5  383.04
#Mann= 6 ,-1 , 0
  4806.1     .05       0  4874.7     .12       0  4996.9     .07       0
  5002.9     .12       0  5047.9     .16       0  5065.3     .05       0
Bank Sta=4957.2,5342.8
XS Rating Curve= 0 ,0
Exp/Cntr=0.3,0.1

Type RM Length L Ch R = 1 ,2871    ,499,499,499
BEGIN DESCRIPTION:
UNT 0476 IN LACR 6.0
END DESCRIPTION:
XS GIS Cut Line= 2
      3723289.64     10669685.06      3722686.88     10670495.98
#Sta/Elev= 30
  4696.7  375.89  4724.4  374.56  4742.7  373.52  4765.4  368.72  4792.7  370.42
  4801.1  369.12  4815.2  368.84    4822  366.56  4828.2     368  4907.5  365.85
  4928.3  364.41  4957.5  362.86  4972.2  363.69  4986.8  363.06    4993  358.15
  5004.6  353.93  5007.4  353.43  5010.6  353.93  5014.6   358.6  5022.2  363.16
  5028.5  364.21  5036.8  363.41  5080.6  364.29  5358.1  364.44  5464.4  362.97
  5537.5  364.78  5600.2  369.06  5608.4  368.56  5679.3  372.09  5707.1  375.99
#Mann= 5 ,-1 , 0
  4696.7     .16       0  4724.4     .12       0  5004.6     .07       0
  5010.6     .12       0  5080.6     .05       0
Bank Sta=4928.3,5537.5
XS Rating Curve= 0 ,0
Exp/Cntr=0.3,0.1

Type RM Length L Ch R = 1 ,2372    ,339,339,339
BEGIN DESCRIPTION:
UNT 0476 IN LACR 5.0
END DESCRIPTION:
XS GIS Cut Line= 3
       3723099.6      10669460.2      3722699.61     10669860.19
      3722299.58     10670260.22
#Sta/Elev= 30
  4435.6  389.55  4591.2   374.1  4629.4  371.21  4647.7  369.16  4718.4  364.22
  4732.6  358.52  4746.7  360.75  4789.1  364.01  4817.4  361.73  4845.7  362.94
    4874   361.3  4888.1  363.13  4916.4  361.99  4958.8  362.56  4987.1  358.58
  4997.7  355.48  5004.8  355.48  5012.4  352.97  5015.2  352.47  5018.4  352.97
  5029.9  358.21  5043.7   362.1  5057.8  362.41  5163.4  360.92  5244.2   361.1
  5389.7  360.32    5423  360.37    5468  361.62  5496.2  362.58    5567  368.17
#Mann= 10 ,-1 , 0
  4435.6     .05       0  4629.4     .16       0  4647.7     .12       0
  5012.4     .07       0  5018.4     .12       0  5029.9     .16       0
  5163.4     .05       0  5244.2     .16       0  5389.7     .12       0
    5423     .05       0
Bank Sta=4718.4,5468
XS Rating Curve= 0 ,0
Exp/Cntr=0.3,0.1

Type RM Length L Ch R = 1 ,2033    ,499,499,499
BEGIN DESCRIPTION:
UNT 0476 IN LACR 4.0
END DESCRIPTION:
XS GIS Cut Line= 3
      3722599.61     10669410.19      3722399.61     10669810.19
      3722149.61     10670210.18
#Sta/Elev= 30
  4568.8  377.51    4651   373.2  4684.6  370.71  4716.9  370.13  4758.6  366.77
  4881.8  362.74  4890.2  360.67  4904.2  360.55  4918.2  359.09  4940.5  360.33
  4957.3  354.75  4962.9  358.08  4971.3  356.47  4976.7  352.35  4979.4  351.85
  4982.7  352.35  4985.3  359.44    5002  353.49    5019  352.81  5023.7  360.35
  5191.1  357.41  5218.3  357.48  5227.7  359.28  5263.7  357.69    5276  359.36
  5306.7  360.02  5364.1  367.76    5401  370.92  5464.7  380.35  5487.7  381.86
#Mann= 7 ,-1 , 0
  4568.8     .05       0    4651     .16       0  4684.6     .05       0
  4758.6     .12       0  4976.7     .07       0  4982.7     .12       0
  5364.1     .05       0
Bank Sta=4904.2,5306.7
XS Rating Curve= 0 ,0
Exp/Cntr=0.3,0.1

Type RM Length L Ch R = 1 ,1534    ,501,501,501
BEGIN DESCRIPTION:
UNT 0476 IN LACR 3.0
END DESCRIPTION:
XS GIS Cut Line= 3
       3722349.6      10669310.2      3721949.61     10669710.19
       3721799.6     10670010.21
#Sta/Elev= 30
  4410.3  375.43  4635.4  367.24  4721.4  361.21  4763.8  361.04  4820.4  357.76
  4891.1  354.74  4919.4  356.79  4978.8  357.18  4984.4  355.71  4986.9  351.71
  4989.7  351.21  4992.9  351.71  5006.7  353.02  5012.3  355.49    5043  357.26
  5065.4  356.38  5073.8  353.08  5079.4  352.92  5096.2  356.06  5110.1  355.66
  5118.5  354.08  5124.1  355.48  5146.5  354.38  5163.2  355.69  5177.2  358.11
    5208  359.41  5221.9  362.97  5252.7  368.56    5289  371.87  5311.4  375.45
#Mann= 4 ,-1 , 0
  4410.3     .05       0  4635.4     .12       0  4986.9     .07       0
  4992.9     .12       0
Bank Sta=4820.4,5177.2
XS Rating Curve= 0 ,0
Exp/Cntr=0.3,0.1

Type RM Length L Ch R = 1 ,1033    ,193,193,193
BEGIN DESCRIPTION:
UNT 0476 IN LACR 2.0
END DESCRIPTION:
XS GIS Cut Line= 3
      3722349.59     10668710.21      3721549.61     10669510.19
      3721299.59     10669860.22
#Sta/Elev= 30
  3853.8  393.89  4228.3  367.19  4348.7  362.04    4476  360.51  4560.9  357.64
  4617.4  354.23    4674  351.66  4685.2   350.1  4687.9   349.6  4691.2   350.1
  4702.3  351.34  4758.9   352.6  4815.4  352.41  4829.6  351.26  4900.3  354.01
  4942.7  353.36  4988.2  354.63  4992.5  351.56  4998.7  351.18  5013.4  354.84
  5057.7  352.78  5128.9  352.02  5206.3   354.4  5243.2  359.16  5250.6  361.27
  5271.5  364.26    5301  366.21  5307.1  368.04  5321.9  368.44  5415.3  379.03
#Mann= 4 ,-1 , 0
  3853.8     .05       0  4228.3     .12       0  4685.2     .07       0
  4691.2     .12       0
Bank Sta=4617.4,5206.3
XS Rating Curve= 0 ,0
Exp/Cntr=0.3,0.1

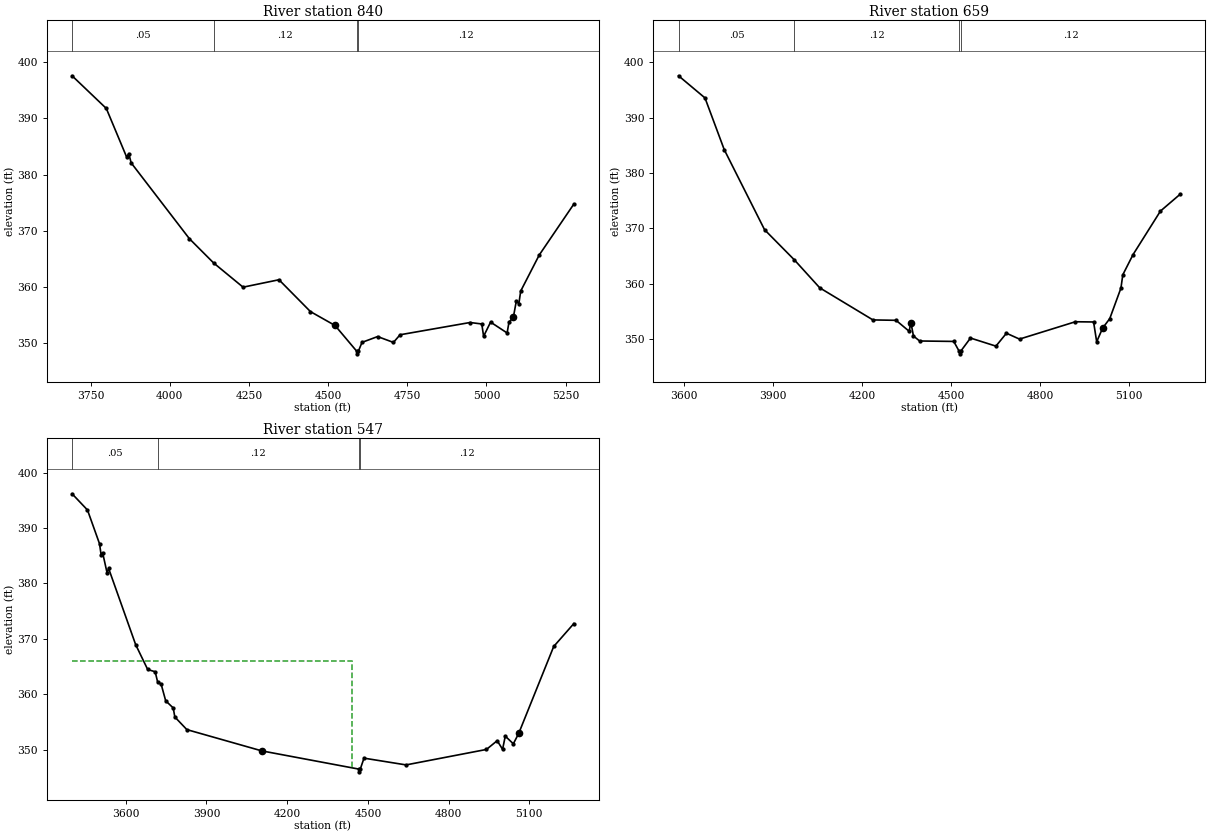
Type RM Length L Ch R = 1 ,840     ,181,181,181
BEGIN DESCRIPTION:
Mapping XS 44d89ef4
END DESCRIPTION:
XS GIS Cut Line= 3
      3722307.29     10668594.81      3721421.87     10669407.31
      3721227.43     10669736.57
#Sta/Elev= 30
  3691.8  397.56  3799.9  391.75  3864.1  383.11  3870.9  383.73  3878.2  382.09
    4062  368.61  4138.8  364.28  4231.6  359.98    4345   361.3  4444.3  355.64
    4522  353.17  4589.9  348.63  4592.6  348.13  4595.9  348.63  4607.1  350.17
  4656.4   351.2  4706.3  350.16  4727.3  351.52  4948.1   353.7  4985.2  353.44
    4991  351.25    5013  353.77  5065.2  351.84  5071.1  353.76  5084.8  354.61
  5094.3  357.52  5102.3  357.06  5108.1  359.29  5166.6   365.7  5275.9  374.76
#Mann= 4 ,-1 , 0
  3691.8     .05       0  4138.8     .12       0  4589.9     .07       0
  4595.9     .12       0
Bank Sta=4522,5084.8
XS Rating Curve= 0 ,0
Exp/Cntr=0.3,0.1

Type RM Length L Ch R = 1 ,659     ,112,112,112
BEGIN DESCRIPTION:
Mapping XS 2f76966d
END DESCRIPTION:
XS GIS Cut Line= 3
       3722296.9     10668542.71      3721231.77     10669326.58
      3721153.72     10669685.61
#Sta/Elev= 30
  3582.4  397.55  3671.5  393.55  3736.3  384.22  3872.1  369.77  3972.6  364.32
    4058  359.28  4237.1  353.49  4314.9  353.42  4358.9  351.45  4365.1  352.99
  4373.5  350.59  4394.3  349.69  4509.3  349.61  4527.1  347.87  4529.9  347.37
  4533.1  347.87  4565.6  350.22  4651.3  348.76  4686.7  351.09  4730.7  350.03
  4918.8  353.16  4980.2  353.12  4990.6  349.55  5010.9  352.04  5034.6  353.72
  5072.3  359.24  5078.6  361.64  5113.2  365.29  5205.3  373.13  5272.3   376.2
#Mann= 4 ,-1 , 0
  3582.4     .05       0  3972.6     .12       0  4527.1     .07       0
  4533.1     .12       0
Bank Sta=4365.1,5010.9
XS Rating Curve= 0 ,0
Exp/Cntr=0.3,0.1

Type RM Length L Ch R = 1 ,547     ,0,0,0
BEGIN DESCRIPTION:
UNT 0476 IN LACR 1.0
END DESCRIPTION:
XS GIS Cut Line= 3
      3722270.86     10668516.67      3721109.37     10669100.02
      3721109.37     10669665.07
#Sta/Elev= 30
  3400.6  396.16  3457.9  393.23  3502.7  387.13  3508.5  385.15  3514.1  385.54
  3530.8  381.86  3536.4  382.69  3636.9  368.94  3681.6  364.45  3709.5  364.04
  3718.1  362.28  3731.8  361.77  3748.5   358.8  3776.5  357.51  3782.5  355.88
  3827.2   353.6  4105.8  349.76  4465.7  346.48  4468.5  345.98  4471.7  346.48
  4485.5  348.45  4641.8  347.23  4940.5  350.02  4980.5   351.6  5000.5  350.04
  5010.5  352.42  5040.5  351.04  5060.5  352.92  5190.5   368.6  5265.4  372.74
#Mann= 4 ,-1 , 0
  3400.6     .05       0  3718.1     .12       0  4465.7     .07       0
  4471.7     .12       0
#XS Ineff= 2 , 0
         4442.65  365.92
Permanent Ineff=
       F       F
Bank Sta=4105.8,5060.5
XS Rating Curve= 0 ,0
Exp/Cntr=0.3,0.1
Stream Node=UNT 0476 IN LACR,Reach-1         , 0 , 0 ,Upstream end
Stream Node=UNT 0476 IN LACR,Reach-1         , 0 , 1 ,Downstream end

Chan Stop Cuts=-1
Use User Specified Reach Order=0
Composite Channel Slope=5