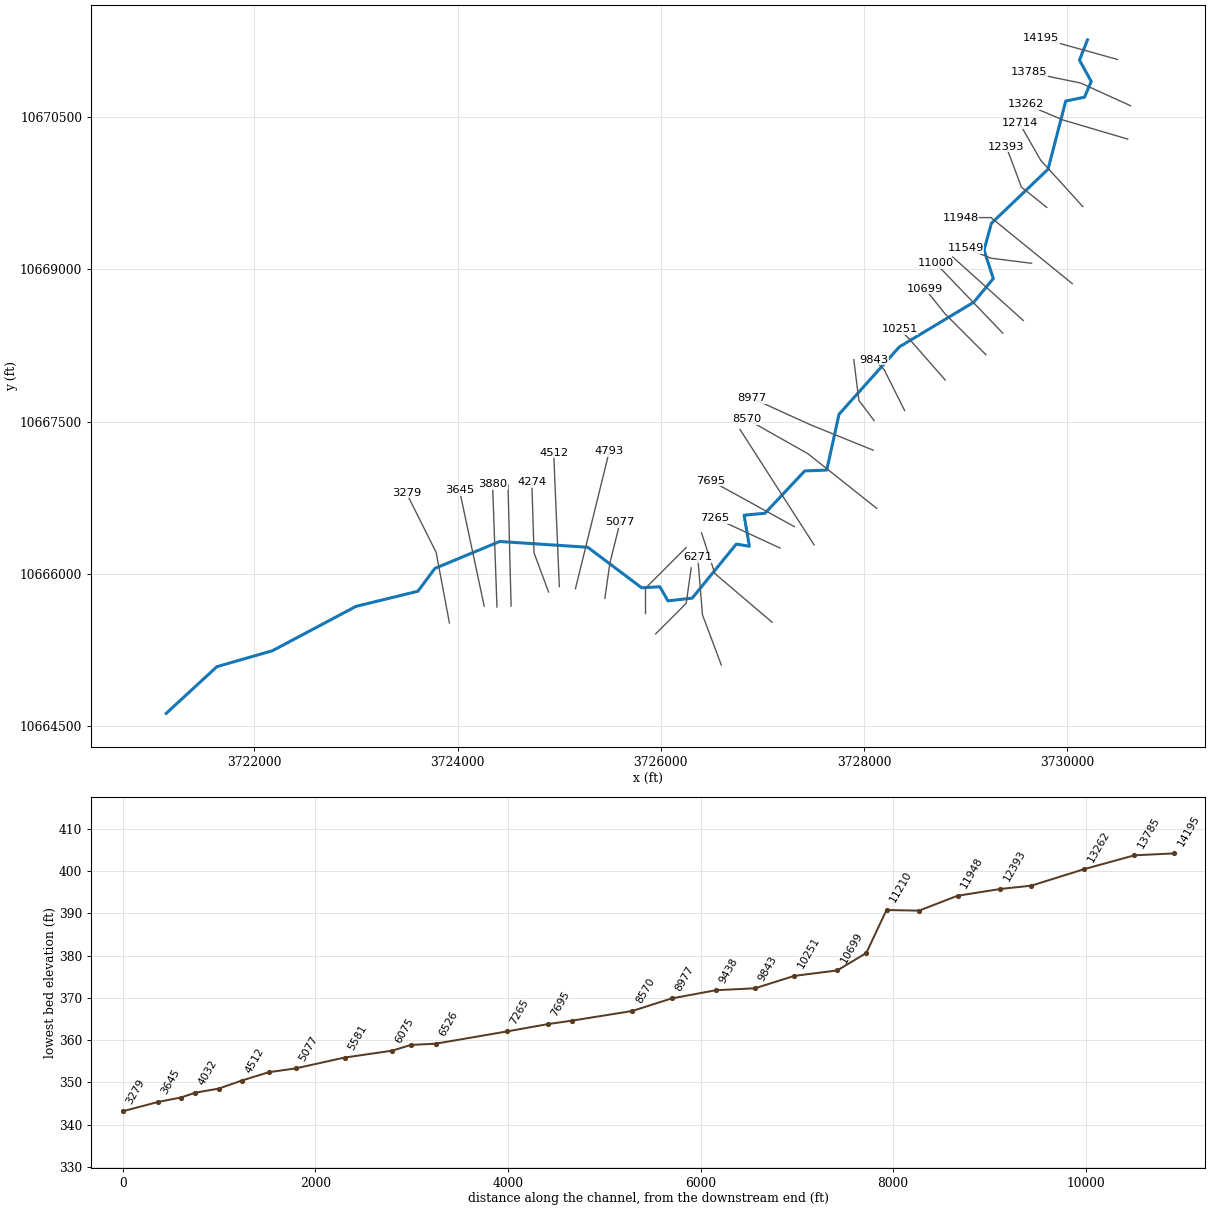
--- UNT 0477 IN LACR.prj (project) ---

Proj Title=UNT 0477 IN LACR Base Level Engineering
Current Plan=p01
Default Exp/Contr=0.3,0.1
English Units
Geom File=g01
Flow File=f01
Plan File=p01
Y Axis Title=Elevation
X Axis Title(PF)=Main Channel Distance
X Axis Title(XS)=Station
BEGIN DESCRIPTION:
UNT 0477 IN LACR
END DESCRIPTION:
DSS Export Rating Curves= 0
DSS Export Rating Curve Sorted= 0
DSS Export Volume Flow Curves= 0
DXF OffsetX= 0
DXF OffsetY= 0
DXF ScaleX= 1
DXF ScaleY= 10

--- UNT 0477 IN LACR.p01 (plan) ---

Plan Title=Multiple Run
Short Identifier=Multiple
Geom File=g01
Flow File=f01
Subcritical Flow
K Sum by GR= 0
Std Step Tol= 0.01
Critical Tol= 0.01
Num of Std Step Trials= 20
Max Error Tol= 0.3
Flow Tol Ratio= 0.001
Split Flow NTrial= 30
Split Flow Tol= 0.02
Split Flow Ratio= 0.02
Log Output Level= 0
Friction Slope Method= 1
Unsteady Friction Slope Method= 2
Unsteady Bridges Friction Slope Method= 1
Parabolic Critical Depth
Global Vel Dist=  1 , 1 , 1
Global Log Level= 0
CheckData=True
Encroach Param= -1, 0, 0, 0
BEGIN DESCRIPTION:
Multiple Run
END DESCRIPTION:

--- UNT 0477 IN LACR.f01 (steady flow) ---

Flow Title=Multiple
Program Version=4.10
Number of Profiles= 7
Profile Names=10-year,25-year,50-year,1pct_min,100-year,1pct_plu,500-year
River Rch & RM=UNT 0477 IN LACR,Reach-1         ,14195
     755    1051    1302    1187    1606    2172    2451
River Rch & RM=UNT 0477 IN LACR,Reach-1         ,11000
    1095    1544    1931    1773    2397    3242    3710
Boundary for River Rch & Prof#=UNT 0477 IN LACR,Reach-1         , 1
Up Type= 0
Dn Type= 3
Dn Slope=0.003
Boundary for River Rch & Prof#=UNT 0477 IN LACR,Reach-1         , 2
Up Type= 0
Dn Type= 3
Dn Slope=0.003
Boundary for River Rch & Prof#=UNT 0477 IN LACR,Reach-1         , 3
Up Type= 0
Dn Type= 3
Dn Slope=0.003
Boundary for River Rch & Prof#=UNT 0477 IN LACR,Reach-1         , 4
Up Type= 0
Dn Type= 3
Dn Slope=0.003
Boundary for River Rch & Prof#=UNT 0477 IN LACR,Reach-1         , 5
Up Type= 0
Dn Type= 3
Dn Slope=0.003
Boundary for River Rch & Prof#=UNT 0477 IN LACR,Reach-1         , 6
Up Type= 0
Dn Type= 3
Dn Slope=0.003
Boundary for River Rch & Prof#=UNT 0477 IN LACR,Reach-1         , 7
Up Type= 0
Dn Type= 3
Dn Slope=0.003
DSS Import GetInterval= 0
DSS Import GetPeak= 0
DSS Import FillOption= 0

--- UNT 0477 IN LACR.g01 (geometry) ---

Geom Title=Existing Conditions
Program Version=4.10

River Reach=UNT 0477 IN LACR,Reach-1
Reach XY= 30
       3730199.5       10671260.        3730121.       10671061.
       3730236.5       10670851.      3730170.25       10670696.
       3729985.5       10670658.      3729811.75       10669987.
      3729253.75       10669453.      3729181.75       10669190.
      3729272.75       10668910.        3729081.       10668677.
      3728347.25       10668236.      3727754.25       10667573.
      3727633.25       10667023.        3727417.       10667015.
       3727025.5       10666598.        3726820.       10666579.
       3726871.5       10666273.        3726743.       10666294.
        3726309.       10665762.       3726070.5       10665735.
      3725990.75       10665874.      3725811.75       10665864.
        3725281.       10666263.      3724414.25       10666320.
        3723777.       10666055.       3723609.5       10665830.
       3723000.5       10665681.        3722178.       10665244.
        3721631.       10665087.      3721132.25       10664627.

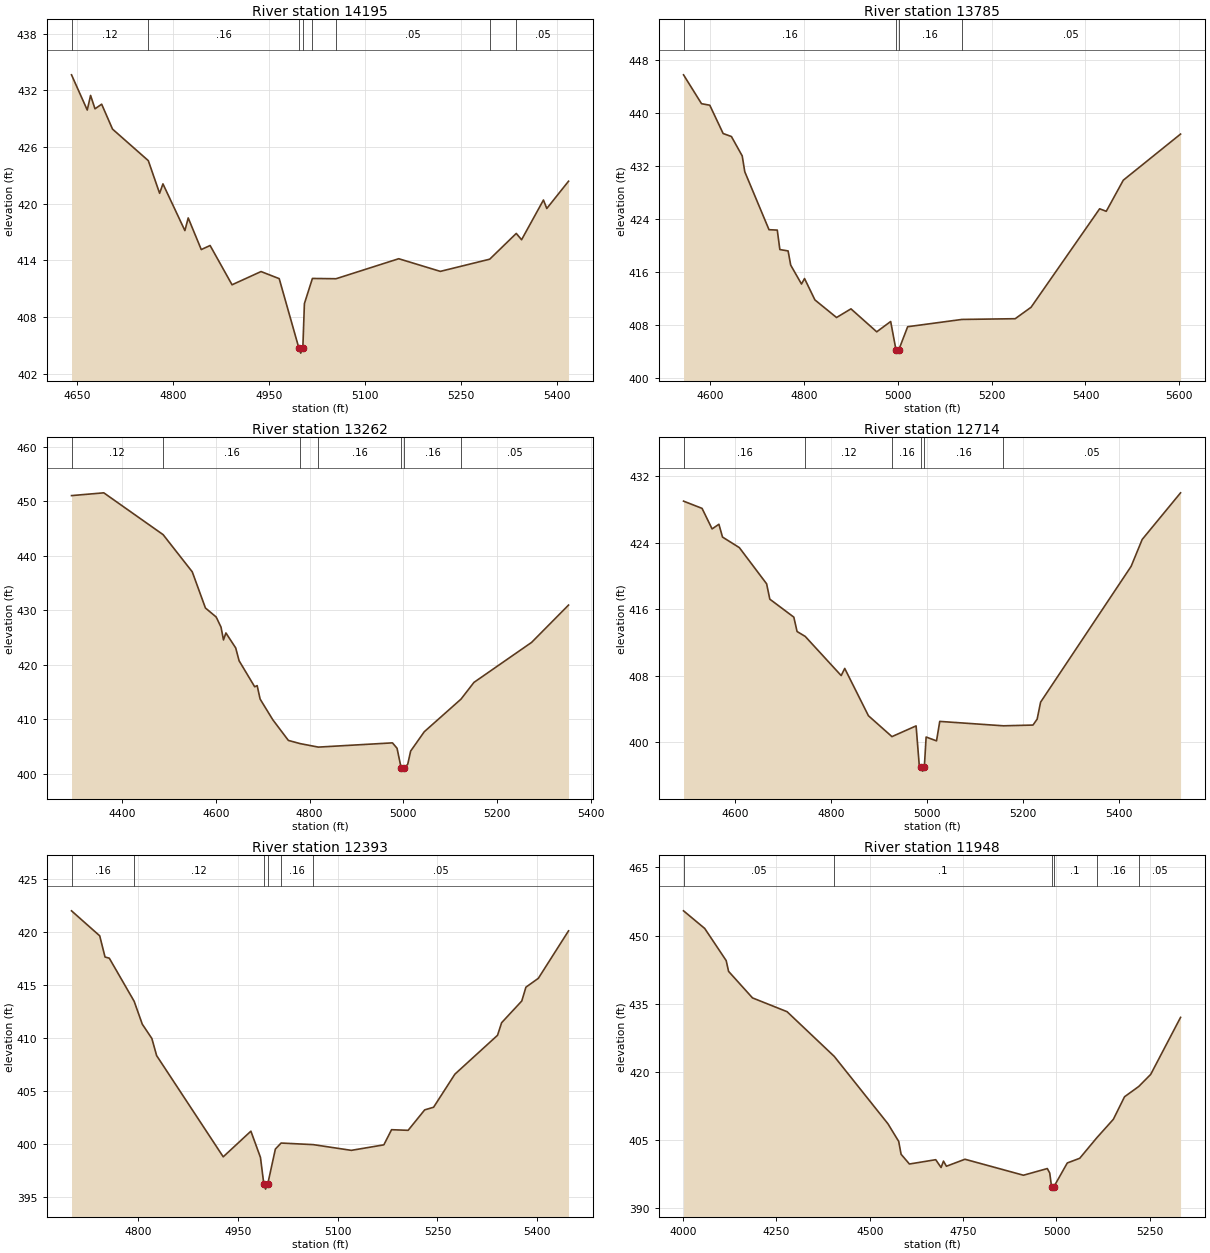
Type RM Length L Ch R = 1 ,14195   ,410,410,410
BEGIN DESCRIPTION:
UNT 0477 IN LACR 30.0
END DESCRIPTION:
XS GIS Cut Line= 2
        3730495.     10671067.67      3729746.54     10671275.58
#Sta/Elev= 30
  4641.5  433.65  4666.1  429.92  4671.3  431.47  4678.2  430.05  4688.6  430.54
  4705.6   427.9  4761.5  424.56  4779.2   421.1  4784.4   422.1  4818.7  417.15
  4823.9  418.49  4844.3  415.14  4858.1  415.57  4892.4  411.41  4937.7  412.81
  4966.1  412.06    4997  404.67  4999.7  404.17    5003  404.67  5005.5  409.42
    5018  412.08  5054.9  412.05  5152.9  414.17  5217.9  412.83  5295.1  414.12
  5336.6  416.85  5344.9  416.18  5379.1  420.39  5384.3  419.49  5418.3  422.38
#Mann= 8 ,-1 , 0
  4641.5     .12       0  4761.5     .16       0    4997     .07       0
    5003     .16       0    5018     .12       0  5054.9     .05       0
  5295.1     .12       0  5336.6     .05       0
Bank Sta=4997,5003
XS Rating Curve= 0 ,0
Exp/Cntr=0.3,0.1

Type RM Length L Ch R = 1 ,13785   ,523,523,523
BEGIN DESCRIPTION:
UNT 0477 IN LACR 29.0
END DESCRIPTION:
XS GIS Cut Line= 3
      3730624.27     10670611.52      3730132.13     10670835.46
       3729624.5     10670939.59
#Sta/Elev= 30
  4543.7  445.77    4582  441.41  4599.6  441.18  4628.1   436.9  4645.7  436.45
  4668.7  433.52  4674.2  431.12  4725.8  422.37  4743.4  422.31  4748.9  419.37
  4766.5  419.16    4772  417.02    4795  414.16  4801.5  414.99  4823.6  411.76
  4869.7   409.1  4900.4  410.41  4955.3  406.94    4985   408.5  4996.3  404.22
    4999  403.72  5002.3  404.22  5021.2  407.71  5136.7  408.81  5250.3  408.92
  5284.1  410.65  5430.2  425.53  5444.3  425.15  5480.6  429.85  5602.6  436.82
#Mann= 4 ,-1 , 0
  4543.7     .16       0  4996.3     .07       0  5002.3     .16       0
  5136.7     .05       0
Bank Sta=4996.3,5002.3
XS Rating Curve= 0 ,0
Exp/Cntr=0.3,0.1

Type RM Length L Ch R = 1 ,13262   ,548,548,548
BEGIN DESCRIPTION:
UNT 0477 IN LACR 28.0
END DESCRIPTION:
XS GIS Cut Line= 3
      3730595.65     10670283.39      3729960.25     10670470.88
      3729593.83     10670626.81
#Sta/Elev= 30
  4291.9  451.03  4360.8  451.54  4487.4  443.86  4549.6  437.03  4577.7  430.39
  4600.6  428.74    4611  426.87  4616.2  424.53  4621.4  425.81  4642.3  423.06
  4649.5  420.71  4682.8  415.93  4688.1  416.14  4694.4  413.67  4721.4  409.88
  4754.7  406.08  4779.9  405.49  4818.7  404.85  4976.8  405.63  4986.6  404.64
  4995.6  400.94  4998.3  400.44  5001.6  400.94  5009.4  401.71  5015.7  404.13
  5044.7  407.67  5123.1  413.66  5150.7  416.73  5273.8  424.08  5352.6  430.93
#Mann= 7 ,-1 , 0
  4291.9     .12       0  4487.4     .16       0  4779.9     .12       0
  4818.7     .16       0  4995.6     .07       0  5001.6     .16       0
  5123.1     .05       0
Bank Sta=4995.6,5001.6
XS Rating Curve= 0 ,0
Exp/Cntr=0.3,0.1

Type RM Length L Ch R = 1 ,12714   ,321,321,321
BEGIN DESCRIPTION:
UNT 0477 IN LACR 27.0
END DESCRIPTION:
XS GIS Cut Line= 3
      3730152.99     10669619.29       3729738.9     10670075.05
      3729530.56     10670439.64
#Sta/Elev= 30
    4493  429.01  4531.6  428.14  4552.5  425.67  4566.7  426.23  4574.2  424.69
  4609.3  423.42  4666.1  419.07  4672.8  417.22  4722.8  415.06  4729.6  413.33
  4746.6  412.74  4821.5  408.03  4828.9  408.89  4878.3   403.2  4927.3  400.69
  4977.6  401.98  4984.3  397.15  4988.8  397.04  4991.5  396.54  4994.8  397.04
  4998.5  400.64  5020.2  400.18  5026.9  402.52  5159.5  401.99  5221.2  402.08
  5229.9   402.8    5237  404.83  5425.7  421.17  5448.7   424.4  5528.7  430.01
#Mann= 6 ,-1 , 0
    4493     .16       0  4746.6     .12       0  4927.3     .16       0
  4988.8     .07       0  4994.8     .16       0  5159.5     .05       0
Bank Sta=4988.8,4994.8
XS Rating Curve= 0 ,0
Exp/Cntr=0.3,0.1

Type RM Length L Ch R = 1 ,12393   ,445,445,445
BEGIN DESCRIPTION:
UNT 0477 IN LACR 26.0
END DESCRIPTION:
XS GIS Cut Line= 3
      3729799.57     10669610.22      3729549.61     10669810.19
      3729399.61     10670210.18
#Sta/Elev= 30
  4699.8  422.03  4742.2  419.67  4750.2  417.67  4756.6  417.56    4794  413.49
  4806.2  411.33  4820.6  409.98  4827.8  408.36  4927.9  398.81  4969.5  401.23
  4983.9  398.75  4988.9  396.26  4991.6  395.76  4994.9  396.26  5006.3  399.54
  5014.9  400.11  5063.3  399.96  5120.5  399.42  5169.4  399.94    5181  401.37
  5205.9  401.31  5230.8  403.24  5244.2  403.49  5276.2  406.61  5340.3  410.28
  5346.5  411.47  5376.8  413.52    5383  414.82  5401.7  415.66  5447.1  420.14
#Mann= 6 ,-1 , 0
  4699.8     .16       0    4794     .12       0  4988.9     .07       0
  4994.9     .12       0  5014.9     .16       0  5063.3     .05       0
Bank Sta=4988.9,4994.9
XS Rating Curve= 0 ,0
Exp/Cntr=0.3,0.1

Type RM Length L Ch R = 1 ,11948   ,399,399,399
BEGIN DESCRIPTION:
UNT 0477 IN LACR 25.0
END DESCRIPTION:
XS GIS Cut Line= 3
      3730049.59      10668860.2      3729249.61     10669510.19
      3728949.57     10669510.19
#Sta/Elev= 30
  4001.4  455.44  4058.1  451.56  4115.6  444.48    4122  442.11    4186  436.27
  4278.6  433.23  4404.8   423.4  4548.7  408.55  4577.5  404.67  4583.9  401.84
  4606.2  399.69  4676.6  400.64    4691  398.92  4697.4  400.33  4705.3   399.2
  4754.9  400.74  4911.5  397.22  4975.4  398.69  4981.9  397.71  4986.8  394.66
  4989.5  394.16  4992.8  394.66  5028.9  399.92  5062.2  400.95  5107.4  405.42
  5152.2  409.53  5182.2   414.5  5220.2  416.76  5252.2  419.42  5332.2  431.98
#Mann= 6 ,-1 , 0
  4001.4     .05       0  4404.8      .1       0  4986.8     .07       0
  4992.8      .1       0  5107.4     .16       0  5220.2     .05       0
Bank Sta=4986.8,4992.8
XS Rating Curve= 0 ,0
Exp/Cntr=0.3,0.1

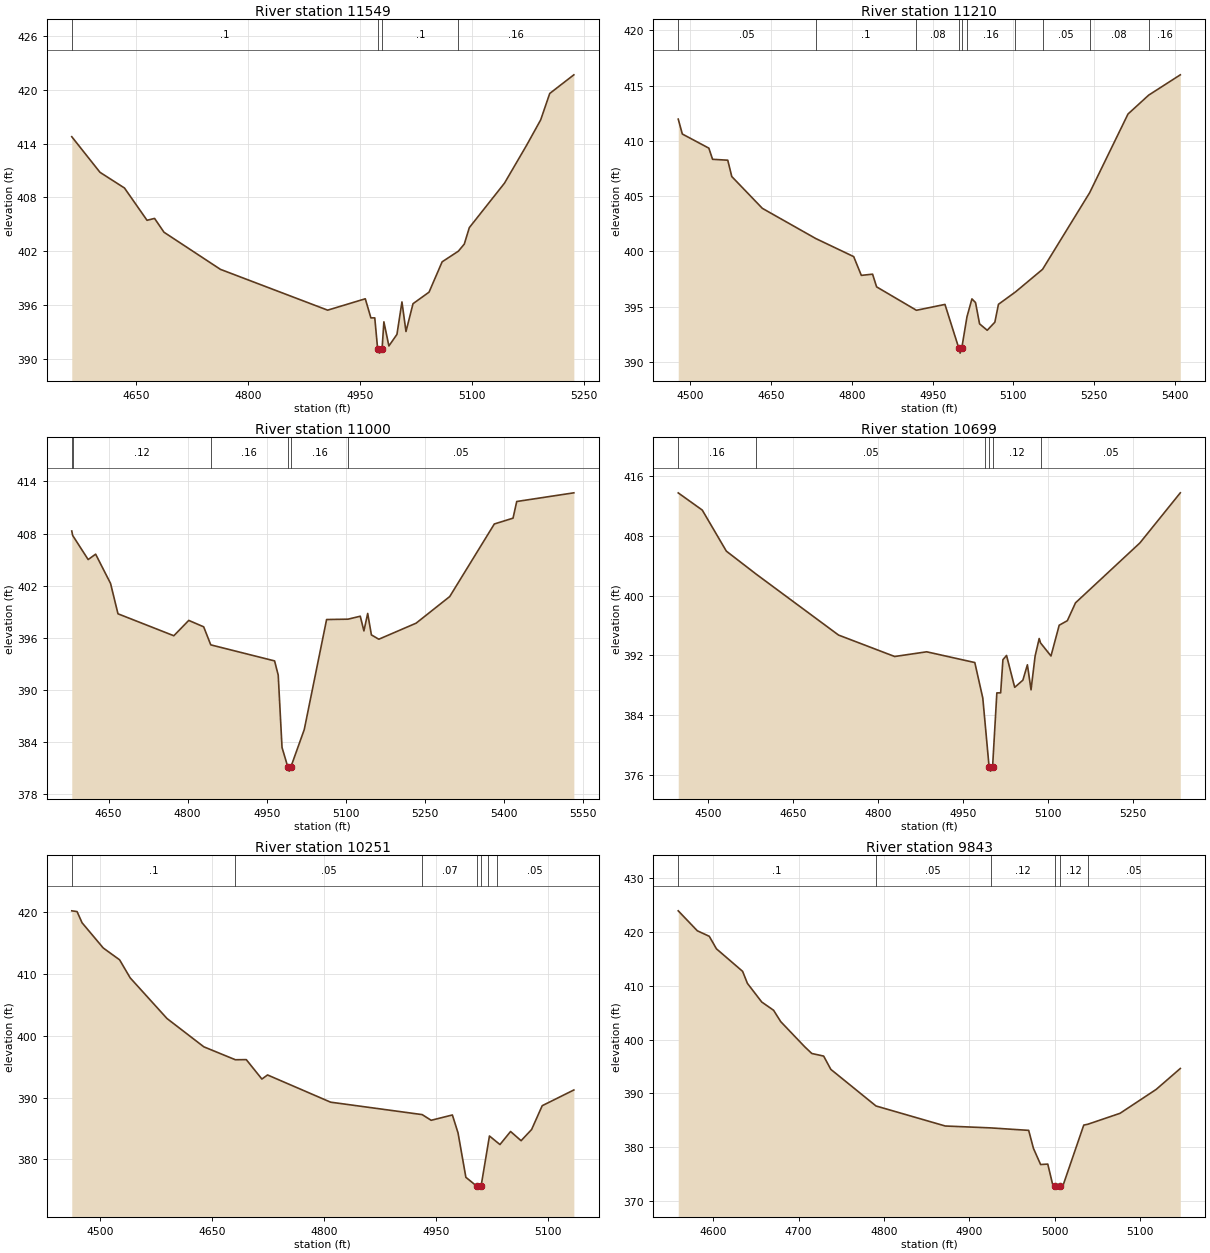
Type RM Length L Ch R = 1 ,11549   ,339,339,339
BEGIN DESCRIPTION:
UNT 0477 IN LACR 24.0
END DESCRIPTION:
XS GIS Cut Line= 3
      3729649.64     10669060.18      3729249.61     10669110.19
      3728999.61     10669210.19
#Sta/Elev= 30
  4564.3  414.77  4602.1   410.8  4634.9  409.05  4665.1  405.45  4675.2  405.66
  4687.8  404.12  4763.4  399.98    4907  395.43  4957.4   396.7  4964.9  394.57
  4970.1  394.57  4973.9  391.14  4976.6  390.64  4979.9  391.14  4982.3  394.13
    4989  391.44  4999.8  392.73  5006.5  396.35  5011.9  393.05  5021.3  396.15
  5042.8  397.44  5060.3  400.82  5082.1  402.01    5090   402.8  5096.7  404.63
  5143.8  409.59  5173.4  413.81  5192.3  416.65  5204.4  419.59  5236.7  421.67
#Mann= 4 ,-1 , 0
  4564.3      .1       0  4973.9     .07       0  4979.9      .1       0
  5082.1     .16       0
Bank Sta=4973.9,4979.9
XS Rating Curve= 0 ,0
Exp/Cntr=0.3,0.1

Type RM Length L Ch R = 1 ,11210   ,210,210,210
BEGIN DESCRIPTION:
UNT 0477 IN LACR 23.0
END DESCRIPTION:
XS GIS Cut Line= 2
      3729567.04     10668497.25      3728873.62     10669121.33
#Sta/Elev= 30
  4477.3  411.97  4484.9  410.62  4534.2  409.34  4541.1  408.33  4569.3  408.25
  4576.8  406.77  4633.6  403.89  4732.7  401.16  4803.3  399.52  4817.5  397.82
  4838.4  397.93  4845.9  396.78  4919.9  394.66  4972.9  395.19  4998.3  391.28
  5001.1  390.78  5004.3  391.28  5013.8  394.07    5023  395.69  5029.7  395.36
  5037.2  393.43  5051.4  392.85  5065.6  393.58  5072.3   395.2  5103.9  396.32
  5154.3  398.37  5241.8  405.31    5313  412.43  5351.4  414.14  5410.2  415.98
#Mann= 10 ,-1 , 0
  4477.3     .05       0  4732.7      .1       0  4919.9     .08       0
  4998.3     .07       0  5004.3     .08       0  5013.8     .16       0
  5103.9     .08       0  5154.3     .05       0  5241.8     .08       0
  5351.4     .16       0
Bank Sta=4998.3,5004.3
XS Rating Curve= 0 ,0
Exp/Cntr=0.3,0.1

Type RM Length L Ch R = 1 ,11000   ,301,301,301
BEGIN DESCRIPTION:
Mapping XS 0c9eba7e
END DESCRIPTION:
XS GIS Cut Line= 2
      3729365.66     10668372.24      3728705.96     10669059.72
#Sta/Elev= 30
  4580.1  408.29  4581.8  407.78  4611.2     405  4625.4  405.62  4653.7  402.25
  4667.8  398.75  4773.8  396.22  4802.1  397.99  4830.4  397.25  4843.9  395.17
    4965  393.32  4971.9  391.68  4979.1  383.35    4990  381.12  4992.8  380.62
    4996  381.12  5021.3  385.41  5063.7  398.09  5104.3  398.13  5127.6  398.47
  5134.5  396.78  5141.7  398.79  5148.7  396.32  5162.8  395.82  5233.6  397.67
  5297.4  400.74    5382   409.1  5417.5  409.77  5424.5  411.69  5532.9  412.69
#Mann= 6 ,-1 , 0
  4580.1     .16       0  4581.8     .12       0  4843.9     .16       0
    4990     .07       0    4996     .16       0  5104.3     .05       0
Bank Sta=4990,4996
XS Rating Curve= 0 ,0
Exp/Cntr=0.3,0.1

Type RM Length L Ch R = 1 ,10699   ,448,448,448
BEGIN DESCRIPTION:
UNT 0477 IN LACR 22.0
END DESCRIPTION:
XS GIS Cut Line= 3
      3729199.62     10668160.17      3728799.61     10668560.19
      3728599.58     10668810.22
#Sta/Elev= 30
  4447.5  413.76  4489.9  411.46  4532.4  405.96  4585.2  402.87  4730.4  394.72
  4829.4  391.85  4885.9  392.48  4970.8  391.04  4984.9  386.28    4989  382.88
  4996.1     377  4998.8   376.5  5002.1     377  5009.7  386.98  5016.4  386.98
  5020.4  391.42  5026.8  391.99  5041.2  387.72  5055.6  388.68  5063.6  390.74
    5070  387.39  5077.2  391.91  5084.4  394.26  5086.8  393.67  5105.2  391.92
  5119.7  396.04  5134.1  396.65  5148.5  399.04  5262.1  407.06  5333.4  413.77
#Mann= 6 ,-1 , 0
  4447.5     .16       0  4585.2     .05       0    4989     .12       0
  4996.1     .07       0  5002.1     .12       0  5086.8     .05       0
Bank Sta=4996.1,5002.1
XS Rating Curve= 0 ,0
Exp/Cntr=0.3,0.1

Type RM Length L Ch R = 1 ,10251   ,408,408,408
BEGIN DESCRIPTION:
UNT 0477 IN LACR 21.0
END DESCRIPTION:
XS GIS Cut Line= 3
       3728799.6      10667910.2      3728449.61     10668310.19
      3728349.62     10668410.18
#Sta/Elev= 30
  4462.2   420.2  4469.3  420.08    4476  418.27  4504.4  414.19  4526.3  412.28
  4540.5  409.36  4589.8  402.79  4639.2  398.21  4681.5  396.12  4696.1  396.14
    4717     393  4724.6  393.66  4809.1  389.26  4931.8  387.25  4943.9  386.33
  4972.3  387.19  4979.9  384.29  4990.4  377.11  5004.8   375.7  5007.6   375.2
  5010.8   375.7  5019.5  381.98    5022  383.79  5031.8  382.83  5036.1  382.41
  5050.3  384.52  5064.4  383.03  5078.5  384.84  5092.7  388.69  5135.1  391.23
#Mann= 7 ,-1 , 0
  4462.2      .1       0  4681.5     .05       0  4931.8     .07       0
  5004.8     .07       0  5010.8     .07       0  5019.5     .12       0
  5031.8     .05       0
Bank Sta=5004.8,5010.8
XS Rating Curve= 0 ,0
Exp/Cntr=0.3,0.1

Type RM Length L Ch R = 1 ,9843    ,405,405,405
BEGIN DESCRIPTION:
UNT 0477 IN LACR 20.0
END DESCRIPTION:
XS GIS Cut Line= 3
      3728399.62     10667610.16      3728199.61     10668010.19
      3728099.59     10668110.21
#Sta/Elev= 30
  4558.8  423.85  4581.2  420.15  4595.2  419.13  4603.6  416.81  4634.3  412.63
  4639.9  410.41  4656.7  406.95  4670.6  405.42    4679  403.31    4707  398.67
  4715.4  397.41  4729.3  396.93  4737.7  394.47  4790.7  387.68  4871.9  383.97
    4925  383.62  4969.7  383.16  4975.3  379.82  4983.7  376.83  4992.1  376.91
  4997.7  373.21  5000.3  372.77    5003  372.27  5006.3  372.77  5009.6  372.77
  5034.3  384.14    5039  384.29  5076.8  386.32  5119.2  390.75  5147.5  394.63
#Mann= 6 ,-1 , 0
  4558.8      .1       0  4790.7     .05       0    4925     .12       0
  5000.3     .07       0  5006.3     .12       0    5039     .05       0
Bank Sta=5000.3,5006.3
XS Rating Curve= 0 ,0
Exp/Cntr=0.3,0.1

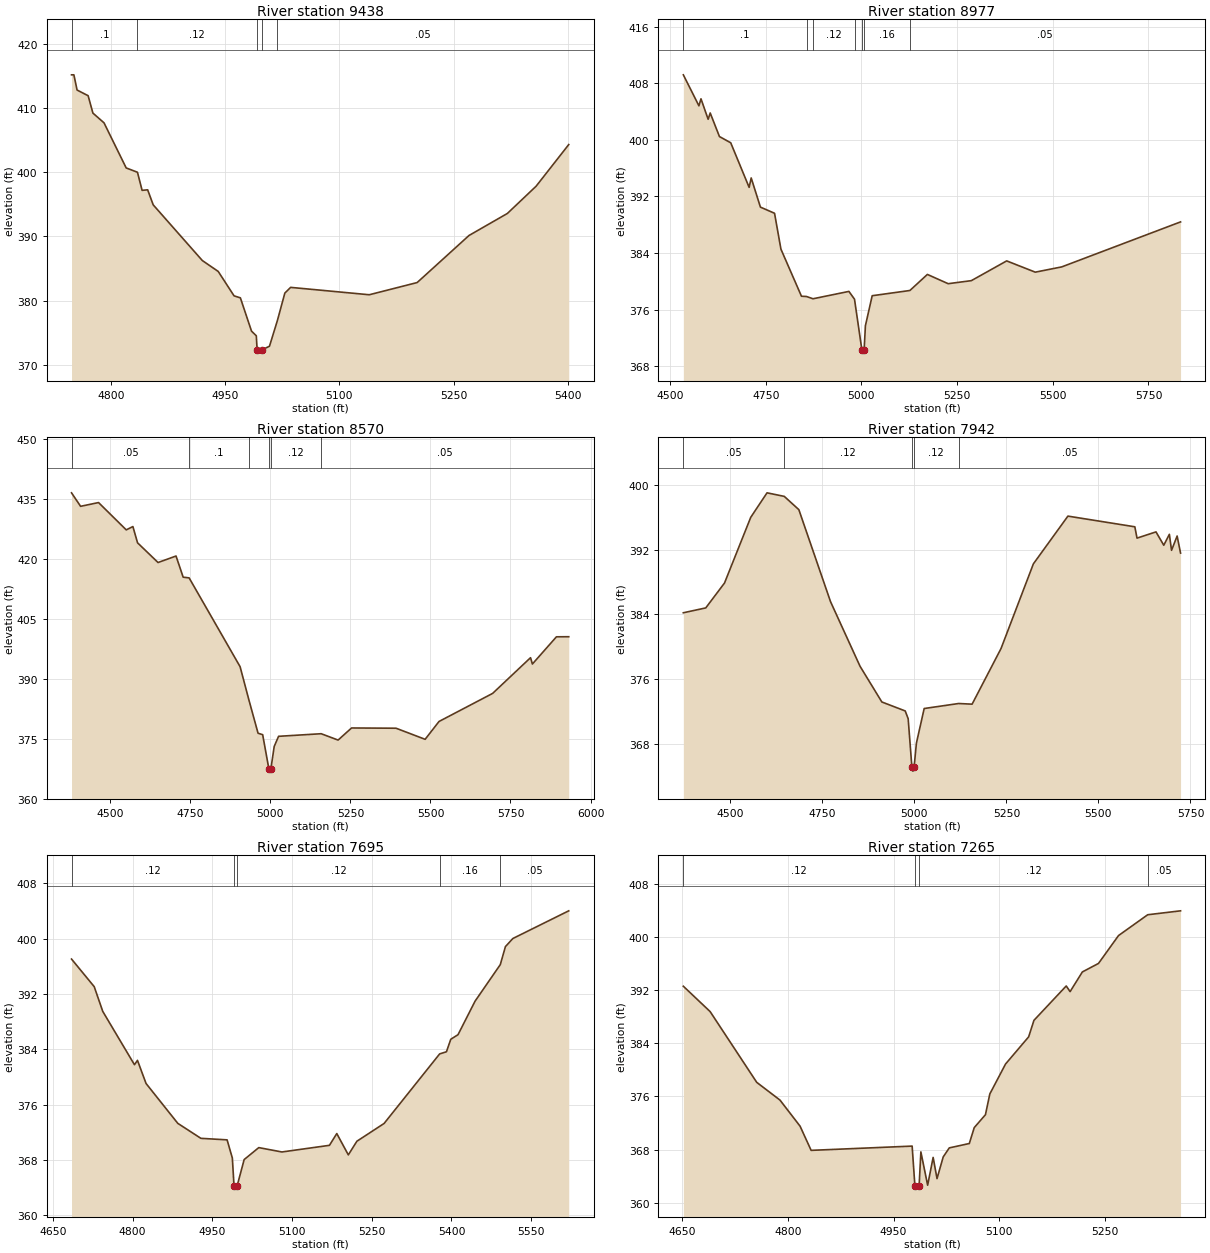
Type RM Length L Ch R = 1 ,9438    ,461,461,461
BEGIN DESCRIPTION:
UNT 0477 IN LACR 19.0
END DESCRIPTION:
XS GIS Cut Line= 3
      3728099.59     10667510.21      3727949.61     10667710.19
      3727899.61      10668110.2
#Sta/Elev= 30
  4748.2  415.16  4751.3  415.16  4755.5  412.79    4770  411.91  4776.3   409.2
  4790.9  407.68    4820  400.66  4834.8  399.99  4840.9  397.17  4848.2  397.25
  4855.5  394.91    4920  386.24  4940.9  384.54  4961.7  380.74    4970  380.43
  4984.6  375.25  4990.9  374.52    4992  372.32  4994.8  371.82    4998  372.32
  5008.2  372.89  5018.6  376.89  5028.4  381.17    5036  382.06  5139.3  380.91
  5202.2  382.81  5270.3  390.14  5320.7  393.57  5358.5  397.82  5401.3   404.3
#Mann= 5 ,-1 , 0
  4748.2      .1       0  4834.8     .12       0    4992     .07       0
    4998     .12       0  5018.6     .05       0
Bank Sta=4992,4998
XS Rating Curve= 0 ,0
Exp/Cntr=0.3,0.1

Type RM Length L Ch R = 1 ,8977    ,407,407,407
BEGIN DESCRIPTION:
UNT 0477 IN LACR 18.0
END DESCRIPTION:
XS GIS Cut Line= 3
      3728090.46     10667219.15       3727469.8     10667470.88
      3726896.88      10667731.3
#Sta/Elev= 30
  4534.7  409.19  4575.4  404.81  4580.8   405.8  4599.5  402.91  4604.9   403.8
    4629  400.47  4658.5  399.59  4706.6  393.29    4712  394.62  4736.1   390.5
    4773  389.63  4789.7  384.56  4843.3  377.91  4856.5  377.87  4873.5  377.55
  4967.3  378.59  4981.9  377.49  5001.1  370.37  5003.8  369.87  5007.1  370.37
  5010.4  373.74  5028.1  377.98  5126.7  378.72  5172.3  380.99  5226.6  379.68
  5287.2  380.11  5379.5   382.9  5454.2  381.31  5523.2  382.05  5833.8  388.41
#Mann= 7 ,-1 , 0
  4534.7      .1       0  4856.5     .05       0  4873.5     .12       0
  4981.9     .16       0  5001.1     .07       0  5007.1     .16       0
  5126.7     .05       0
Bank Sta=5001.1,5007.1
XS Rating Curve= 0 ,0
Exp/Cntr=0.3,0.1

Type RM Length L Ch R = 1 ,8570    ,628,628,628
BEGIN DESCRIPTION:
UNT 0477 IN LACR 17.0
END DESCRIPTION:
XS GIS Cut Line= 3
      3728125.16     10666646.25       3727448.1     10667184.42
      3726849.15     10667522.96
#Sta/Elev= 30
    4379  436.63  4407.3  433.25  4463.4  434.19  4549.9  427.35  4570.7  428.18
  4585.2  424.11  4649.2  419.17  4705.4   420.8  4727.7   415.5  4746.3  415.32
  4905.5  393.07  4933.2  384.68  4961.6   376.4    4976  376.04  4995.5  367.41
  4998.2  366.91  5001.5  367.41    5012  373.09  5025.7  375.63  5158.7  376.28
  5211.5  374.69  5253.6  377.72  5392.5  377.66  5483.4  374.88  5526.8  379.35
  5694.2  386.38  5812.6  395.33  5818.4  393.74  5893.5  400.56  5931.9  400.58
#Mann= 6 ,-1 , 0
    4379     .05       0  4746.3      .1       0  4933.2     .12       0
  4995.5     .07       0  5001.5     .12       0  5158.7     .05       0
Bank Sta=4995.5,5001.5
XS Rating Curve= 0 ,0
Exp/Cntr=0.3,0.1

Type RM Length L Ch R = 1 ,7942    ,247,247,247
BEGIN DESCRIPTION:
UNT 0477 IN LACR 16.0
END DESCRIPTION:
XS GIS Cut Line= 2
      3727508.84     10666286.02      3726779.71     10667423.13
#Sta/Elev= 30
  4372.3   384.2  4433.2   384.8  4484.2  387.88  4555.4     396  4599.7  399.03
  4646.5  398.59  4686.1  396.95  4772.2  385.57  4852.4  377.58  4911.6  373.17
  4975.1  372.06  4983.1   371.1  4993.2  365.12    4996  364.62  4999.2  365.12
  5005.5  368.08  5026.6  372.36  5120.2  372.98  5156.8   372.9  5235.4  379.78
  5323.3  390.25  5417.1  396.15  5598.9  394.83  5604.8  393.43  5656.4   394.2
  5677.5  392.55  5692.7   393.9  5698.6  391.92  5713.8  393.69  5723.1  391.58
#Mann= 5 ,-1 , 0
  4372.3     .05       0  4646.5     .12       0  4993.2     .07       0
  4999.2     .12       0  5120.2     .05       0
Bank Sta=4993.2,4999.2
XS Rating Curve= 0 ,0
Exp/Cntr=0.3,0.1

Type RM Length L Ch R = 1 ,7695    ,430,430,430
BEGIN DESCRIPTION:
UNT 0477 IN LACR 15.0
END DESCRIPTION:
XS GIS Cut Line= 2
      3727314.69     10666466.03      3726495.29      10666917.4
#Sta/Elev= 30
  4685.2  397.06  4727.9  393.07    4744  389.49  4803.6  381.79  4809.3  382.42
  4825.4  379.08  4885.1  373.32  4928.6  371.15  4977.9  370.93  4987.8   368.3
  4990.9  364.31  4993.7  363.81  4996.9  364.31    5010  368.08  5037.5  369.81
  5081.1  369.18  5170.5  370.14  5184.3  371.84    5206  368.76  5222.1  370.73
  5273.3   373.3  5377.8  383.35  5390.6  383.66  5398.8  385.47  5412.4  386.13
  5444.5  390.98  5491.9  396.25  5501.6  398.86  5515.6  400.03  5620.7  404.03
#Mann= 5 ,-1 , 0
  4685.2     .12       0  4990.9     .07       0  4996.9     .12       0
  5377.8     .16       0  5491.9     .05       0
Bank Sta=4990.9,4996.9
XS Rating Curve= 0 ,0
Exp/Cntr=0.3,0.1

Type RM Length L Ch R = 1 ,7265    ,739,739,739
BEGIN DESCRIPTION:
UNT 0477 IN LACR 14.0
END DESCRIPTION:
XS GIS Cut Line= 2
       3727174.1     10666255.24      3726534.08     10666551.83
#Sta/Elev= 30
  4651.7  392.57  4689.7  388.76  4755.8  378.12  4788.8  375.45  4817.3  371.53
    4833  367.89  4976.3  368.53  4980.2  362.56  4982.9  362.06  4986.2  362.56
  4988.7  367.66  4998.3  362.65  5006.1  366.83  5011.6  363.64  5020.4  366.91
    5029  368.26  5057.4  368.92  5064.4  371.31  5080.3  373.25  5086.5  376.37
  5108.8  380.87  5141.6  384.96  5149.1  387.44  5194.9  392.61  5200.4  391.76
  5217.8  394.72  5240.7     396  5269.1  400.19  5310.5  403.32  5357.1  403.91
#Mann= 4 ,-1 , 0
  4651.7     .12       0  4980.2     .07       0  4986.2     .12       0
  5310.5     .05       0
Bank Sta=4980.2,4986.2
XS Rating Curve= 0 ,0
Exp/Cntr=0.3,0.1

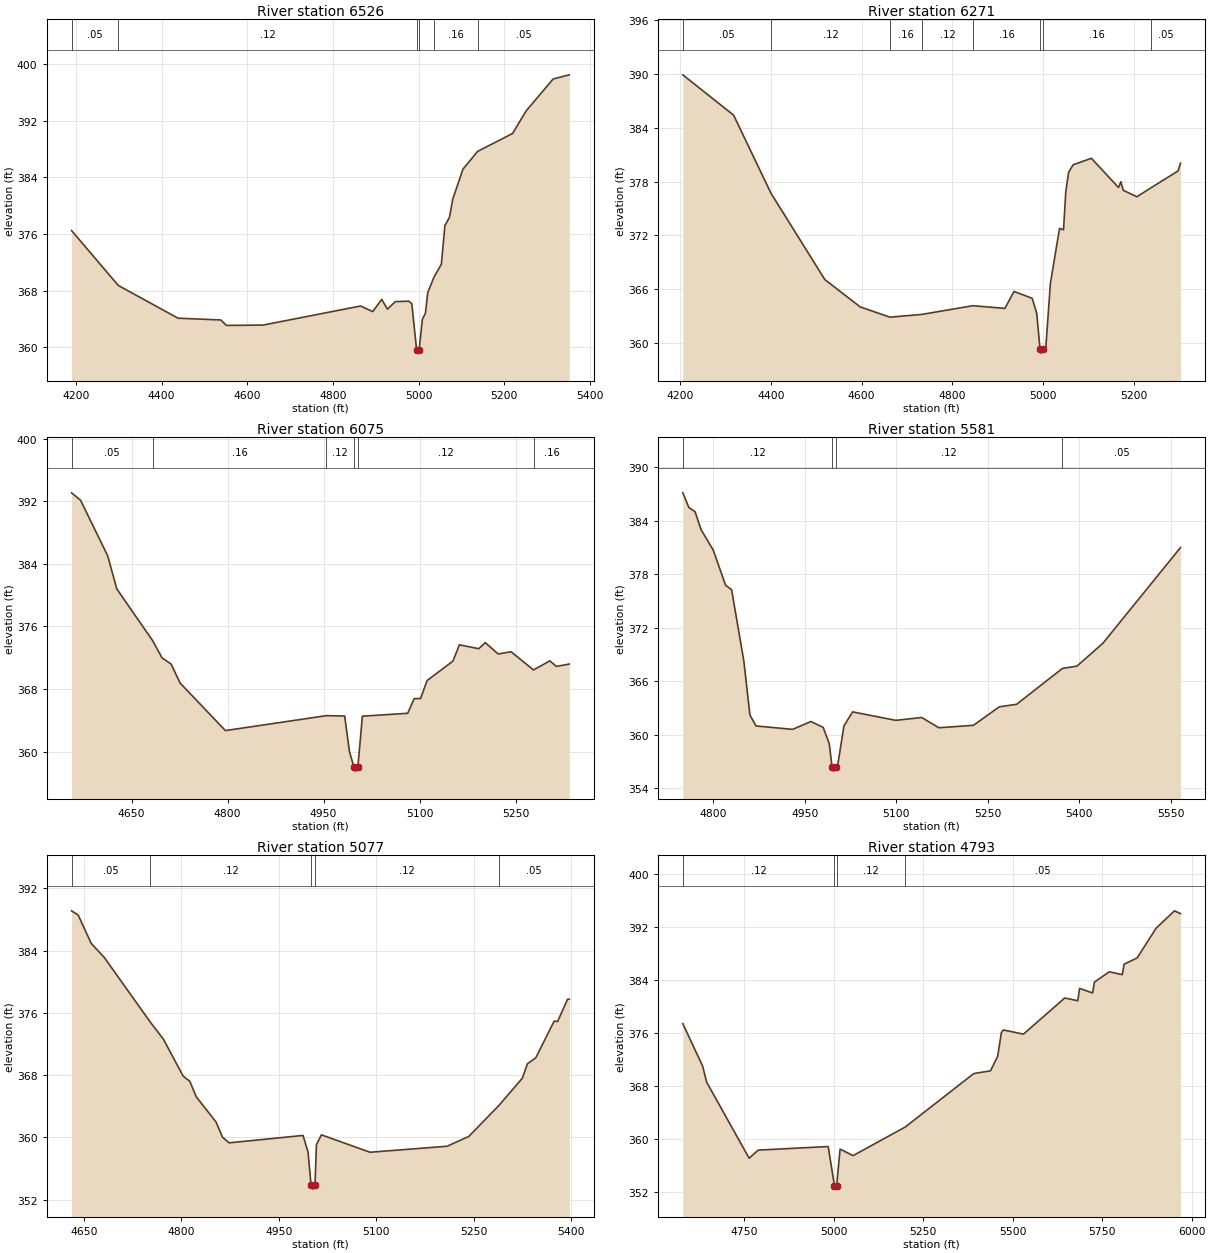
Type RM Length L Ch R = 1 ,6526    ,255,255,255
BEGIN DESCRIPTION:
UNT 0477 IN LACR 13.0
END DESCRIPTION:
XS GIS Cut Line= 3
      3727094.84     10665525.01      3726532.33     10666004.18
      3726400.69     10666406.03
#Sta/Elev= 30
  4189.9  376.47  4298.8  368.73  4438.4   364.1  4538.3  363.85  4551.5  363.08
  4637.1  363.13  4864.4  365.82    4893  365.03  4913.8  366.76  4927.3  365.38
  4945.7  366.44  4977.2   366.5  4984.1  366.17  4995.3  359.67    4998  359.17
  5001.3  359.67  5008.8  363.95    5016  364.82  5021.3  367.68  5035.8  369.88
  5053.1  371.71  5061.4  377.16    5072  378.33  5079.7   380.9  5103.5  385.13
  5137.7  387.64  5219.3  390.17  5250.8  393.34    5314  397.86  5351.7  398.45
#Mann= 6 ,-1 , 0
  4189.9     .05       0  4298.8     .12       0  4995.3     .07       0
  5001.3     .12       0  5035.8     .16       0  5137.7     .05       0
Bank Sta=4995.3,5001.3
XS Rating Curve= 0 ,0
Exp/Cntr=0.3,0.1

Type RM Length L Ch R = 1 ,6271    ,196,196,196
BEGIN DESCRIPTION:
Mapping XS 7bdcdd1e
END DESCRIPTION:
XS GIS Cut Line= 3
      3726595.48     10665104.38       3726410.6     10665596.53
       3726363.8     10666165.98
#Sta/Elev= 30
    4206  389.92    4318  385.42  4400.5   376.7    4519  367.09  4596.8  364.04
  4662.7  362.89  4733.2   363.2  4845.4  364.17    4916  363.87  4936.1  365.76
  4976.2  364.99  4986.2   363.3  4993.3  359.38    4996  358.88  4999.3  359.38
  5006.3  359.59  5016.3  366.67  5036.4  372.78  5045.2  372.64  5050.2   376.9
  5056.5  379.06  5066.5  379.89  5106.6  380.61  5166.5  377.35  5171.5  377.99
  5176.9  377.04    5207  376.32  5237.7  377.31  5297.7   379.2  5303.1  380.07
#Mann= 8 ,-1 , 0
    4206     .05       0  4400.5     .12       0  4662.7     .16       0
  4733.2     .12       0  4845.4     .16       0  4993.3     .07       0
  4999.3     .16       0  5237.7     .05       0
Bank Sta=4993.3,4999.3
XS Rating Curve= 0 ,0
Exp/Cntr=0.3,0.1

Type RM Length L Ch R = 1 ,6075    ,494,494,494
BEGIN DESCRIPTION:
UNT 0477 IN LACR 12.0
END DESCRIPTION:
XS GIS Cut Line= 3
      3725949.63     10665410.21      3726249.61     10665710.19
      3726299.61      10666060.2
#Sta/Elev= 30
  4556.1  393.08  4570.2  392.13  4612.6  385.03  4626.8   380.8  4682.7  374.21
  4697.5  371.99  4711.6  371.21  4725.8  368.77  4796.5   362.7  4954.5  364.61
  4982.9  364.56  4990.4     360  4997.5  358.02  5000.3  357.52  5003.5  358.02
  5010.6  364.54  5081.4  364.91  5091.5  366.78  5101.6   366.8  5111.7  369.09
  5152.1  371.58  5162.2  373.66  5192.5  373.16  5202.6  373.94  5222.8  372.49
    5243  372.77    5278  370.45  5303.6  371.61  5313.7   370.9  5333.9   371.2
#Mann= 6 ,-1 , 0
  4556.1     .05       0  4682.7     .16       0  4954.5     .12       0
  4997.5     .07       0  5003.5     .12       0    5278     .16       0
Bank Sta=4997.5,5003.5
XS Rating Curve= 0 ,0
Exp/Cntr=0.3,0.1

Type RM Length L Ch R = 1 ,5581    ,504,504,504
BEGIN DESCRIPTION:
UNT 0477 IN LACR 11.0
END DESCRIPTION:
XS GIS Cut Line= 3
      3725849.61      10665610.2      3725849.61     10665860.19
      3726249.63     10666260.21
#Sta/Elev= 30
    4750  387.13    4760  385.48    4770  385.02    4780  382.99    4800  380.69
    4820  376.77    4830  376.25    4850  368.26    4860  362.19    4870  360.96
    4930  360.58    4960  361.46    4980   360.8    4990  358.99  4994.5  356.39
  4997.2  355.89  5000.5  356.39  5003.5  356.39  5014.1  360.97  5028.3  362.54
    5099  361.59  5141.4  361.91  5169.7  360.76  5226.3  361.03  5268.7  363.11
    5297  363.39  5372.2  367.42    5396  367.68  5438.4  370.24  5565.7  380.99
#Mann= 4 ,-1 , 0
    4750     .12       0  4994.5     .07       0  5000.5     .12       0
  5372.2     .05       0
Bank Sta=4994.5,5000.5
XS Rating Curve= 0 ,0
Exp/Cntr=0.3,0.1

Type RM Length L Ch R = 1 ,5077    ,284,284,284
BEGIN DESCRIPTION:
UNT 0477 IN LACR 10.0
END DESCRIPTION:
XS GIS Cut Line= 3
       3725449.6     10665760.15      3725499.61     10666110.19
      3725599.61     10666510.19
#Sta/Elev= 30
  4631.2  389.12  4641.3  388.59  4661.5  384.93  4681.7  383.11  4752.1  374.85
  4772.7   372.6    4803  367.87  4813.1  367.22  4823.2  365.21  4853.5  361.98
  4863.6  360.01  4873.7   359.3  4987.4  360.25  4995.1  358.11  4999.8  353.85
  5002.6  353.35  5005.8  353.85    5008  359.06  5015.7  360.33  5090.4  358.09
    5209  358.86  5242.5  360.12    5289  364.12  5324.9  367.61  5332.7  369.46
  5345.6  370.23  5373.9  374.95  5379.1  374.89  5394.5  377.76  5397.1  377.76
#Mann= 5 ,-1 , 0
  4631.2     .05       0  4752.1     .12       0  4999.8     .07       0
  5005.8     .12       0    5289     .05       0
Bank Sta=4999.8,5005.8
XS Rating Curve= 0 ,0
Exp/Cntr=0.3,0.1

Type RM Length L Ch R = 1 ,4793    ,281,281,281
BEGIN DESCRIPTION:
UNT 0477 IN LACR 9.0
END DESCRIPTION:
XS GIS Cut Line= 2
      3725160.25     10665855.51      3725492.66     10667206.62
#Sta/Elev= 30
  4577.8  377.38  4633.4  370.95  4644.4  368.56  4763.2  357.09  4788.6  358.31
  4984.2  358.85  5001.8  352.93  5004.6  352.43  5007.8  352.93  5017.5  358.46
  5053.8  357.48  5199.3  361.78  5391.2  369.85  5437.9  370.26    5458  372.45
  5468.3     376  5474.2  376.42  5530.1  375.79  5645.5  381.24  5681.9  380.83
    5687  382.69  5723.4     382  5728.5  383.63  5770.1  385.19  5806.4  384.76
  5811.6  386.34    5848  387.28  5900.8  391.75  5952.3  394.38  5969.2  393.96
#Mann= 4 ,-1 , 0
  4577.8     .12       0  5001.8     .07       0  5007.8     .12       0
  5199.3     .05       0
Bank Sta=5001.8,5007.8
XS Rating Curve= 0 ,0
Exp/Cntr=0.3,0.1

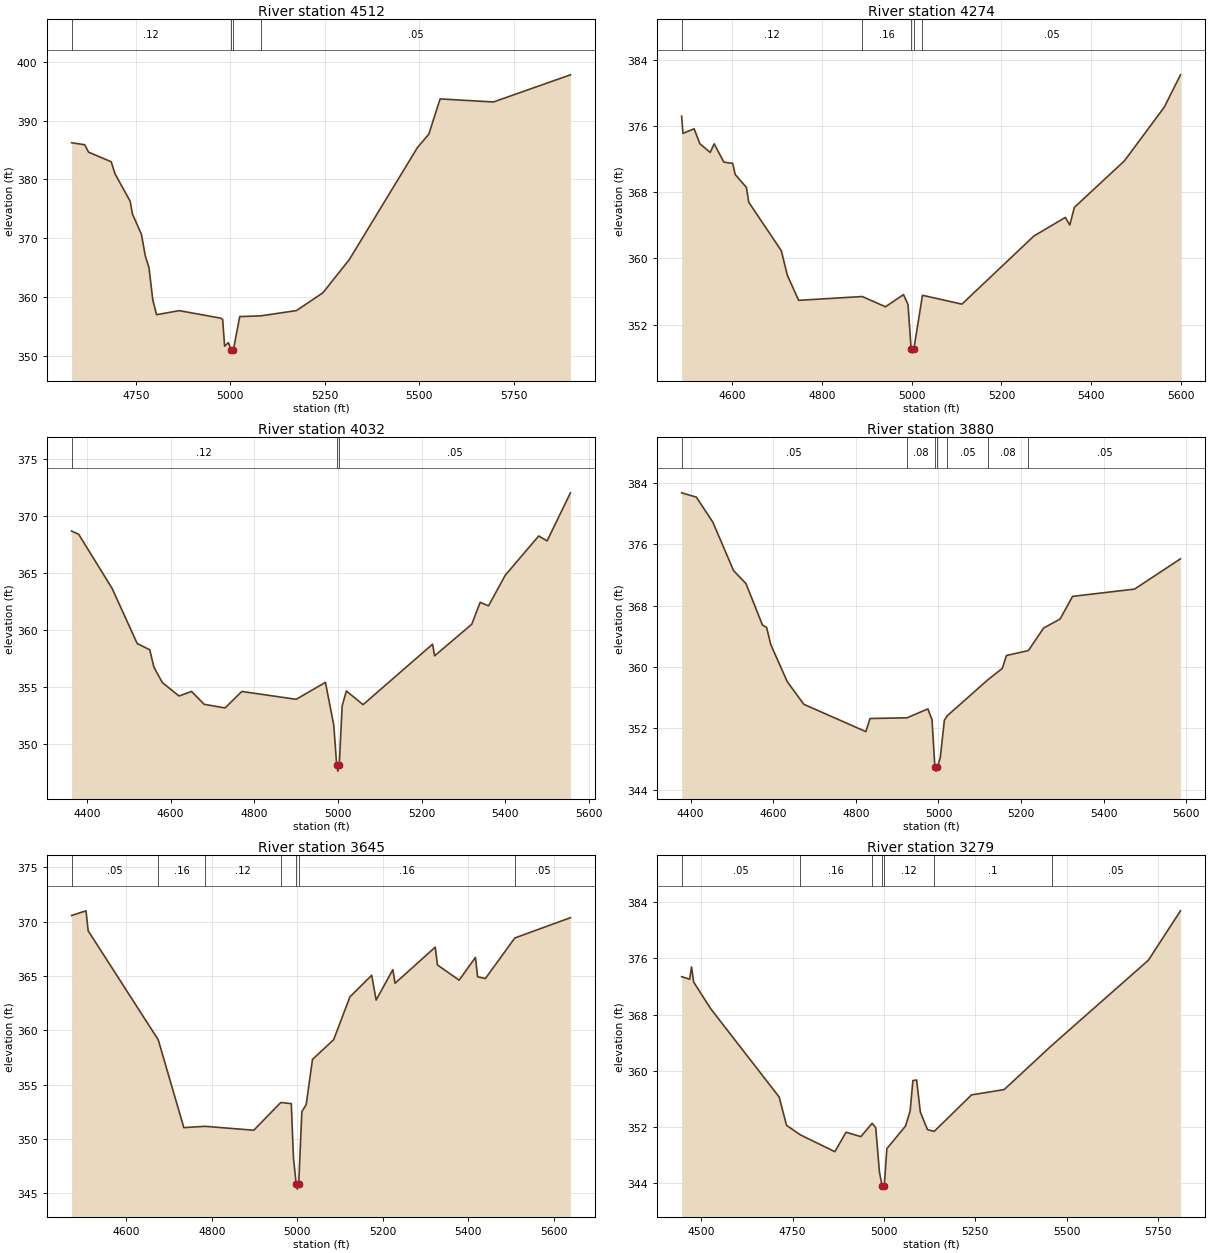
Type RM Length L Ch R = 1 ,4512    ,238,238,238
BEGIN DESCRIPTION:
Mapping XS 4a8c579f
END DESCRIPTION:
XS GIS Cut Line= 2
      3725001.43     10665875.47      3724945.87      10667194.9
#Sta/Elev= 30
    4580  386.25  4614.8  385.91  4624.8  384.65  4684.8  383.02  4694.8  380.97
  4734.9  376.32  4740.9  374.16  4764.9  370.66  4774.9  367.05  4784.9  364.98
  4794.9  359.53  4804.9  356.99    4865  357.68  4974.9   356.4  4979.9  356.18
  4985.1  351.64  4995.1  352.25  5002.1  350.95  5004.8  350.45  5008.1  350.95
  5025.1  356.67  5080.6  356.79  5175.2  357.69  5245.3  360.72  5315.4  366.39
  5495.5  385.43  5525.6   387.7  5555.6  393.71  5696.8  393.19  5900.6  397.81
#Mann= 4 ,-1 , 0
    4580     .12       0  5002.1     .07       0  5008.1     .12       0
  5080.6     .05       0
Bank Sta=5002.1,5008.1
XS Rating Curve= 0 ,0
Exp/Cntr=0.3,0.1

Type RM Length L Ch R = 1 ,4274    ,242,242,242
BEGIN DESCRIPTION:
UNT 0477 IN LACR 8.0
END DESCRIPTION:
XS GIS Cut Line= 3
      3724895.52     10665822.26       3724752.3     10666208.52
      3724730.63     10666906.23
#Sta/Elev= 30
  4488.3  377.18  4491.2  375.11  4516.2  375.66  4528.7  373.86  4551.9   372.8
  4560.7  373.84  4582.3  371.63    4602  371.48  4607.4  370.14  4632.4  368.58
  4637.7  366.78  4710.1  360.93  4723.5  357.97  4748.6  354.93  4890.2  355.39
  4941.9  354.15    4982  355.62    4992  354.43    4999  349.05  5001.7  348.55
    5005  349.05  5024.2  355.54    5112  354.47  5272.1   362.7  5342.1  364.95
  5352.1  364.03  5362.1  366.16  5473.7  371.79  5562.2  378.27  5598.3  382.18
#Mann= 5 ,-1 , 0
  4488.3     .12       0  4890.2     .16       0    4999     .07       0
    5005     .16       0  5024.2     .05       0
Bank Sta=4999,5005
XS Rating Curve= 0 ,0
Exp/Cntr=0.3,0.1

Type RM Length L Ch R = 1 ,4032    ,152,152,152
BEGIN DESCRIPTION:
Mapping XS 0af98e5e
END DESCRIPTION:
XS GIS Cut Line= 2
      3724526.61     10665683.31      3724496.25     10666876.02
#Sta/Elev= 30
  4363.1  368.68    4380   368.4    4460  363.64    4520   358.8    4550  358.25
    4560  356.72  4580.1  355.37  4620.1  354.19  4650.1  354.59  4680.1  353.46
  4730.1  353.14  4770.1  354.59  4900.2   353.9  4970.2  355.39  4990.2  351.62
  4997.2  348.09  4999.9  347.59  5003.2  348.09  5010.2  353.32  5020.2  354.63
  5060.2  353.43  5226.4  358.74  5231.4  357.72  5320.3   360.5  5340.3  362.42
  5360.3  362.11  5400.3   364.8  5480.3  368.25  5500.4  367.82  5556.2  372.04
#Mann= 3 ,-1 , 0
  4363.1     .12       0  4997.2     .07       0  5003.2     .05       0
Bank Sta=4997.2,5003.2
XS Rating Curve= 0 ,0
Exp/Cntr=0.3,0.1

Type RM Length L Ch R = 1 ,3880    ,235,235,235
BEGIN DESCRIPTION:
UNT 0477 IN LACR 7.0
END DESCRIPTION:
XS GIS Cut Line= 2
      3724387.72     10665674.62      3724344.31     10666881.24
#Sta/Elev= 30
  4378.3  382.72  4413.9  382.16  4453.9  378.89    4504  372.58    4534  370.89
    4574  365.48    4584  365.18    4594  362.94    4634   358.1  4674.1  355.15
  4824.2  351.59  4834.2   353.3  4923.7  353.39  4974.3  354.55  4984.3  353.15
  4991.3  346.94    4994  346.44  4997.3  346.94  5004.3   348.2  5014.3  353.09
  5021.7  353.68  5119.7  358.36  5154.4  359.83  5164.4  361.51  5217.7  362.16
  5254.4  365.09  5294.4  366.27  5324.5  369.22  5474.6  370.17  5585.7  374.12
#Mann= 7 ,-1 , 0
  4378.3     .05       0  4923.7     .08       0  4991.3     .07       0
  4997.3     .08       0  5021.7     .05       0  5119.7     .08       0
  5217.7     .05       0
Bank Sta=4991.3,4997.3
XS Rating Curve= 0 ,0
Exp/Cntr=0.3,0.1

Type RM Length L Ch R = 1 ,3645    ,366,366,366
BEGIN DESCRIPTION:
Mapping XS 556c8739
END DESCRIPTION:
XS GIS Cut Line= 2
      3724261.85     10665683.35      3724018.79     10666824.86
#Sta/Elev= 30
    4472  370.58  4505.7  371.01  4510.8  369.17  4674.7  359.14  4734.6  351.06
    4784  351.18  4898.2  350.82  4961.3  353.37    4986  353.27  4991.1  348.27
  4997.4   345.9  5000.2   345.4  5003.4   345.9  5010.7  352.52  5020.9  353.19
  5035.6  357.34  5085.1  359.15  5123.1  363.09  5174.1  365.08  5184.5   362.8
  5223.6   365.6  5228.7  364.34  5322.8  367.67  5327.9  366.03  5378.7  364.63
  5416.8  366.72  5421.9  364.94  5440.1  364.78  5508.9  368.51  5639.1  370.38
#Mann= 7 ,-1 , 0
    4472     .05       0  4674.7     .16       0    4784     .12       0
  4961.3     .16       0  4997.4     .07       0  5003.4     .16       0
  5508.9     .05       0
Bank Sta=4997.4,5003.4
XS Rating Curve= 0 ,0
Exp/Cntr=0.3,0.1

Type RM Length L Ch R = 1 ,3279    ,450,450,450
BEGIN DESCRIPTION:
UNT 0477 IN LACR 6.0
END DESCRIPTION:
XS GIS Cut Line= 3
      3723919.45     10665517.79      3723789.25      10666212.2
      3723494.36     10666801.98
#Sta/Elev= 30
    4446  373.39    4468  373.02  4473.1  374.77    4479  372.61  4525.6  368.83
    4713  356.29  4733.3  352.26  4770.8  350.92  4865.6  348.52  4896.1  351.28
  4936.8  350.66  4967.6  352.55  4977.5  351.93  4987.7   345.6  4994.8   343.7
  4997.6   343.2  5000.8   343.7    5008  348.96  5058.9  352.15  5071.7  354.31
  5079.2  358.62  5089.4  358.71  5099.6  354.15  5119.1  351.65  5137.5   351.4
  5239.7  356.59  5329.1  357.34  5458.9  363.59    5724  375.72  5811.9  382.74
#Mann= 7 ,-1 , 0
    4446     .05       0  4770.8     .16       0  4967.6     .12       0
  4994.8     .07       0  5000.8     .12       0  5137.5      .1       0
  5458.9     .05       0
Bank Sta=4994.8,5000.8
XS Rating Curve= 0 ,0
Exp/Cntr=0.3,0.1