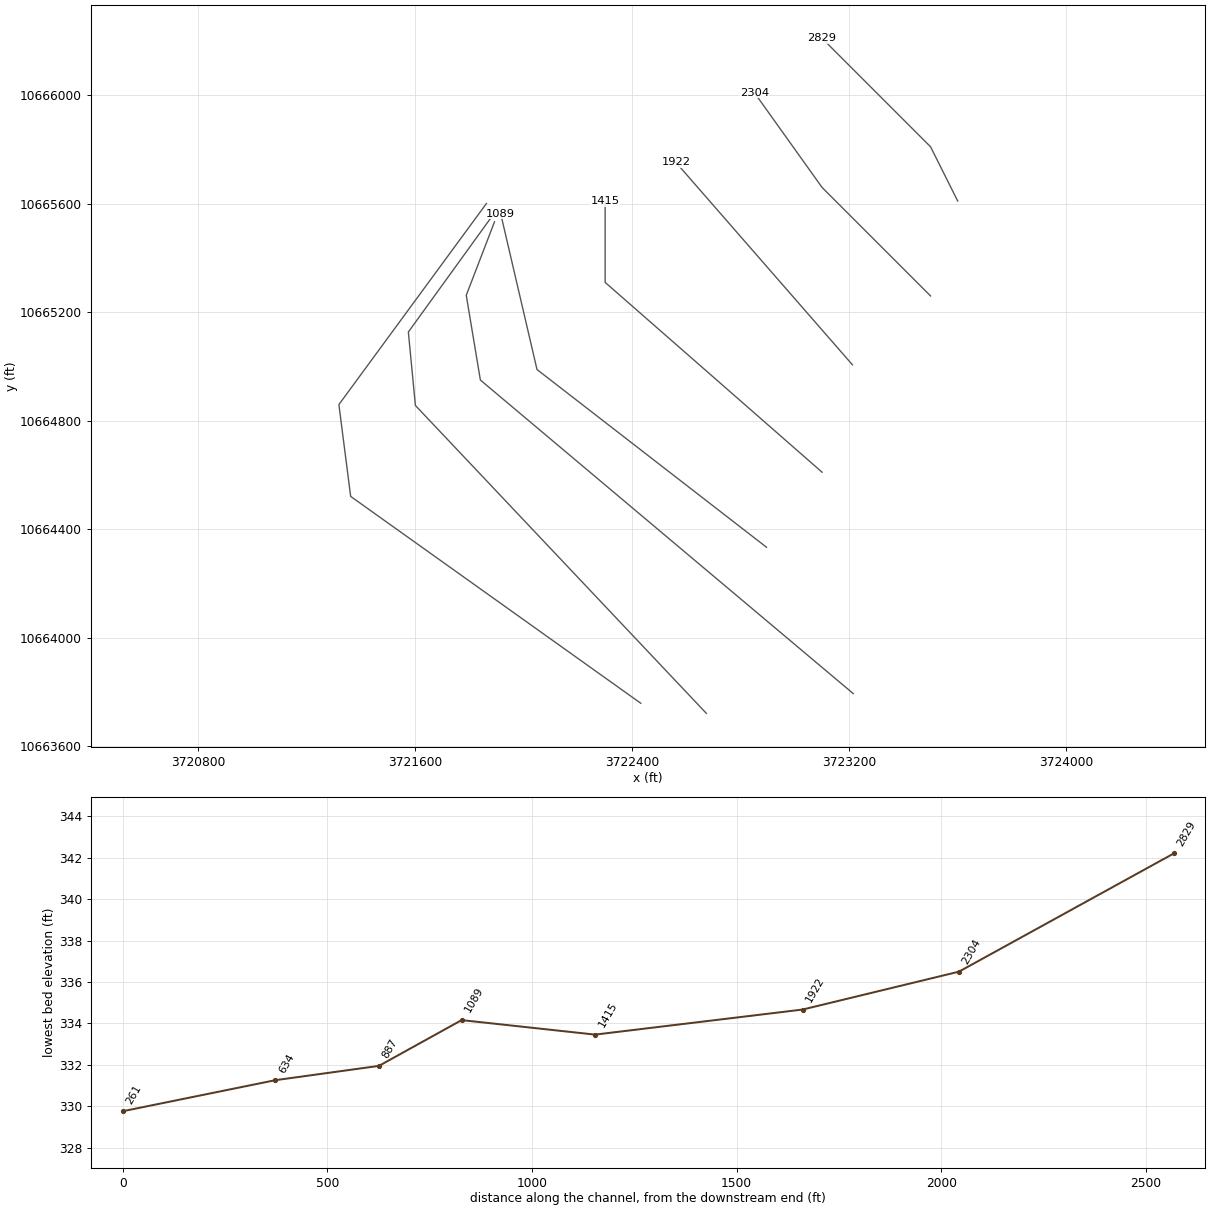
HEC-RAS study UNT 0477 IN LACR.prj: UNT 0477 IN LACR Base Level Engineering

--- UNT 0477 IN LACR.g01 (geometry) --- (continued)

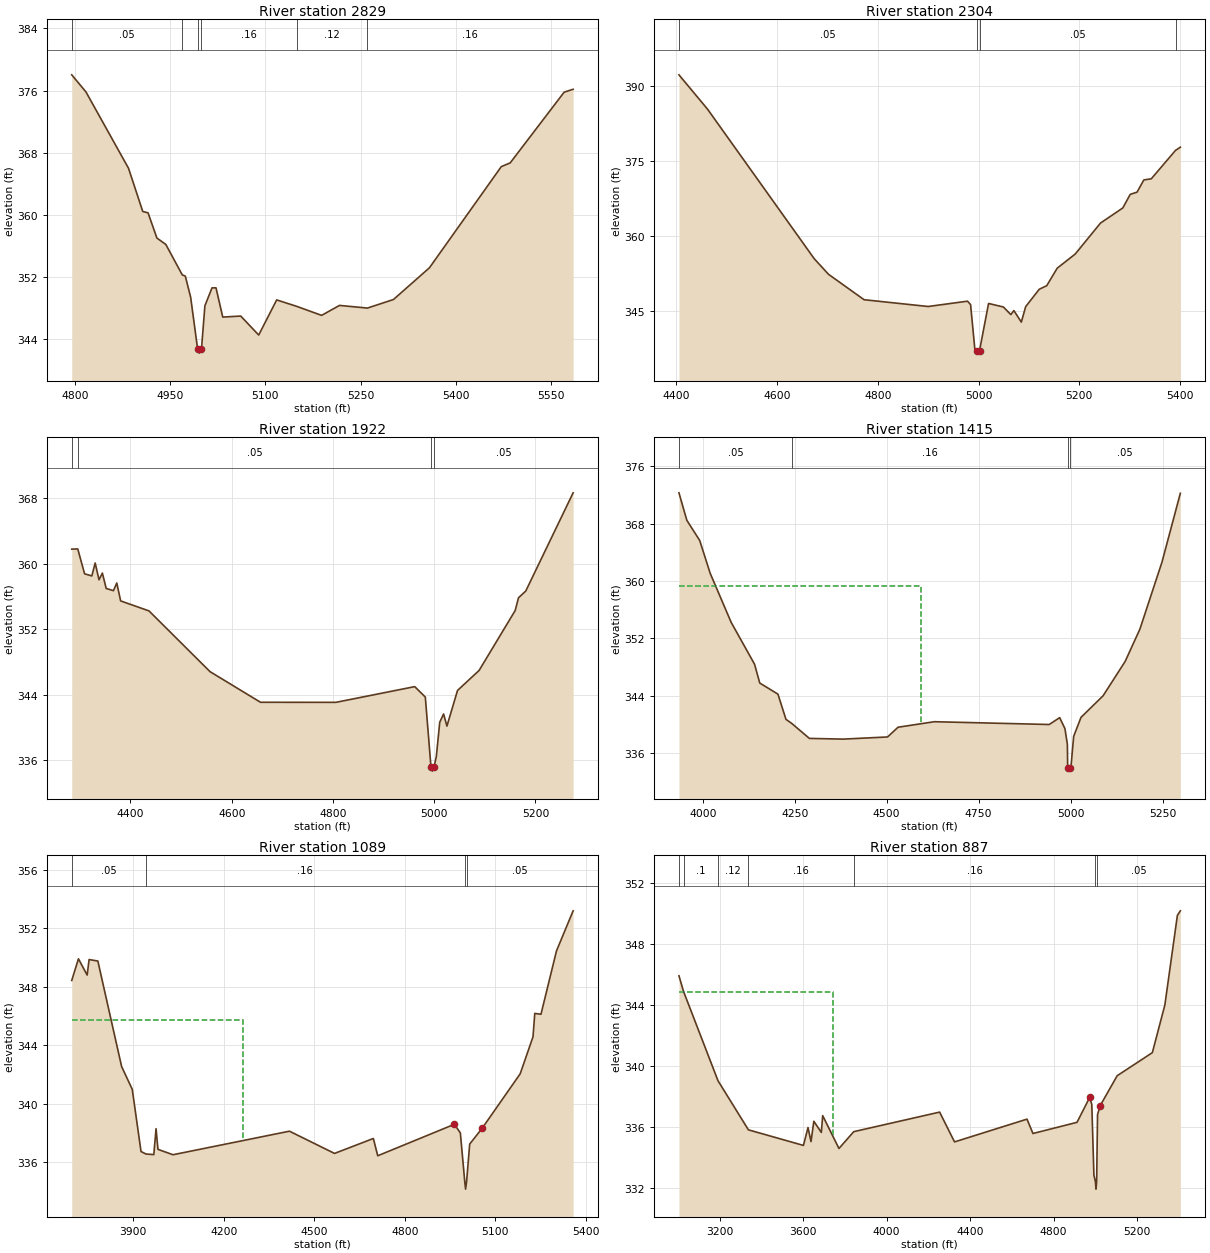
Type RM Length L Ch R = 1 ,2829    ,525,525,525
BEGIN DESCRIPTION:
UNT 0477 IN LACR 5.0
END DESCRIPTION:
XS GIS Cut Line= 3
      3723599.59     10665610.23      3723499.61     10665810.19
      3723099.64     10666210.16
#Sta/Elev= 30
  4795.3  378.03  4817.6  375.84  4884.7     366  4907.1  360.44  4915.4  360.27
  4929.4  357.02  4943.4   356.2  4969.3  352.28  4974.1  352.12  4982.5   349.4
  4993.5  342.71  4996.2  342.21  4999.5  342.71  5004.9   348.3  5016.1  350.61
  5022.4  350.61    5033  346.85  5061.3  346.98  5089.6  344.54  5117.9  349.06
  5149.1  348.24  5188.6  347.07  5216.8  348.35  5260.8  348.01  5301.7  349.11
  5358.3  353.19  5471.4  366.21  5485.5   366.7  5570.4   375.8  5584.5  376.17
#Mann= 6 ,-1 , 0
  4795.3     .05       0  4969.3     .16       0  4993.5     .07       0
  4999.5     .16       0  5149.1     .12       0  5260.8     .16       0
Bank Sta=4993.5,4999.5
XS Rating Curve= 0 ,0
Exp/Cntr=0.3,0.1

Type RM Length L Ch R = 1 ,2304    ,382,382,382
BEGIN DESCRIPTION:
UNT 0477 IN LACR 4.0
END DESCRIPTION:
XS GIS Cut Line= 3
      3723499.62     10665260.17      3723099.61     10665660.19
      3722849.62     10666010.17
#Sta/Elev= 30
    4405  392.31  4461.6  385.45  4673.7  355.43    4702  352.31  4772.7  347.21
    4900  345.85  4978.1  346.92  4984.2  346.23  4992.8  337.15    4996     337
  4998.7   336.5    5002     337  5019.9  346.46  5049.4  345.75  5064.1  344.23
  5070.2  345.03    5085  342.72  5093.6  345.82  5120.6  349.31  5135.4  350.02
  5156.3  353.54  5191.9  356.36  5242.3  362.59  5286.5  365.61  5301.3  368.34
  5314.8  368.78  5328.3  371.23  5343.1  371.46  5391.2  377.16  5400.8   377.8
#Mann= 4 ,-1 , 0
    4405     .05       0    4996     .03       0    5002     .05       0
  5391.2     .16       0
Bank Sta=4996,5002
XS Rating Curve= 0 ,0
Exp/Cntr=0.3,0.1

Type RM Length L Ch R = 1 ,1922    ,507,507,507
BEGIN DESCRIPTION:
UNT 0477 IN LACR 3.0
END DESCRIPTION:
XS GIS Cut Line= 2
       3723211.5     10665006.26      3722560.49     10665752.76
#Sta/Elev= 30
    4284  361.78  4295.9  361.81  4309.4  358.77  4323.7  358.51  4330.3  360.09
  4337.9  358.04  4344.5  358.86  4352.1  356.98  4366.4  356.71    4373  357.65
  4380.6  355.46  4436.6  354.24  4557.2  346.82  4656.9  343.08  4805.9  343.07
  4961.6  344.99  4982.5  343.72  4993.7  335.17  4996.5  334.67  4999.7  335.17
  5004.3  336.47    5011  340.64  5018.6  341.65  5025.2  340.17  5046.1  344.52
  5088.8  346.97    5160  354.28  5166.6  355.84  5180.9  356.66  5274.5  368.66
#Mann= 4 ,-1 , 0
    4284     .16       0  4295.9     .05       0  4993.7     .03       0
  4999.7     .05       0
Bank Sta=4993.7,4999.7
XS Rating Curve= 0 ,0
Exp/Cntr=0.3,0.1

Type RM Length L Ch R = 1 ,1415    ,326,326,326
BEGIN DESCRIPTION:
UNT 0477 IN LACR 2.0
END DESCRIPTION:
XS GIS Cut Line= 3
      3723099.63     10664610.17      3722299.61     10665310.19
      3722299.61     10665610.15
#Sta/Elev= 30
  3935.3  372.32  3956.7  368.49  3991.8  365.66  4020.3  361.07  4077.2  354.24
  4140.8  348.39    4155  345.76  4204.4  344.21  4226.2  340.69  4242.2  340.11
  4289.8  338.03  4381.9  337.93  4502.4  338.23  4530.9  339.59  4629.6  340.36
  4941.9  339.97  4970.3  340.93  4984.6  339.39  4991.2  337.21    4992  333.96
  4994.8  333.46    4998  333.96  5000.8  333.96  5008.3  338.31  5028.3  340.97
  5088.3  343.98  5148.3  348.78  5188.3  353.28  5248.3  362.63  5298.3  372.26
#Mann= 4 ,-1 , 0
  3935.3     .05       0  4242.2     .16       0    4992     .03       0
    4998     .05       0
#XS Ineff= 2 , 0
         4593.31  359.35
Permanent Ineff=
       F       F
Bank Sta=4992,4998
XS Rating Curve= 0 ,0
Exp/Cntr=0.3,0.1

Type RM Length L Ch R = 1 ,1089    ,202,202,202
BEGIN DESCRIPTION:
Mapping XS 4ddaa738
END DESCRIPTION:
XS GIS Cut Line= 3
      3722894.63     10664333.55      3722048.31      10664988.9
      3721914.29     10665563.89
#Sta/Elev= 30
  3696.8  348.42    3719   349.9  3747.9  348.79  3754.3  349.85  3783.3  349.75
    3862  342.54  3897.3  340.98  3926.3  336.73  3942.7  336.56  3968.7  336.52
  3976.1  338.29  3982.4  336.88  4032.2  336.51  4417.9  338.12  4567.3   336.6
  4695.9  337.62  4710.4  336.44  4964.2  338.59  4984.1     338  4998.7  334.66
  5001.4  334.16  5004.7  334.66    5015  337.24    5056  338.31  5182.2  342.04
  5224.7  344.57  5230.6  346.17  5251.1  346.11  5302.5  350.44  5357.6  353.18
#Mann= 4 ,-1 , 0
  3696.8     .05       0  3942.7     .16       0  4998.7     .03       0
  5004.7     .05       0
#XS Ineff= 2 , 0
         4264.52  345.69
Permanent Ineff=
       F       F
Bank Sta=4964.2,5056
XS Rating Curve= 0 ,0
Exp/Cntr=0.3,0.1

Type RM Length L Ch R = 1 ,887     ,253,253,253
BEGIN DESCRIPTION:
Mapping XS ff0db515
END DESCRIPTION:
XS GIS Cut Line= 4
       3723214.5      10663793.9      3721839.53     10664950.12
      3721787.45     10665262.62      3721891.62     10665533.48
#Sta/Elev= 30
  3004.3  345.91  3026.4  344.88  3191.6  339.04  3337.2  335.83    3601  334.81
    3623  335.98  3637.3  335.06  3650.9  336.39  3686.8  335.66  3693.3  336.76
  3771.3  334.61  3842.3  335.71  4253.9  336.99  4325.4  335.04  4672.7  336.53
  4701.3  335.59  4912.4  336.32  4973.2  337.95  4983.3  337.49  4993.5  332.86
  5000.6  332.45  5003.4  331.95  5006.6  332.45  5010.9  336.83  5023.9  337.42
    5105  339.37  5273.6  340.88  5333.6     344  5393.6  349.86  5407.8  350.16
#Mann= 7 ,-1 , 0
  3004.3     .05       0  3026.4      .1       0  3191.6     .12       0
  3337.2     .16       0  3842.3     .16       0  5000.6     .03       0
  5006.6     .05       0
#XS Ineff= 2 , 0
         3740.74  344.84
Permanent Ineff=
       F       F
Bank Sta=4973.2,5023.9
XS Rating Curve= 0 ,0
Exp/Cntr=0.3,0.1

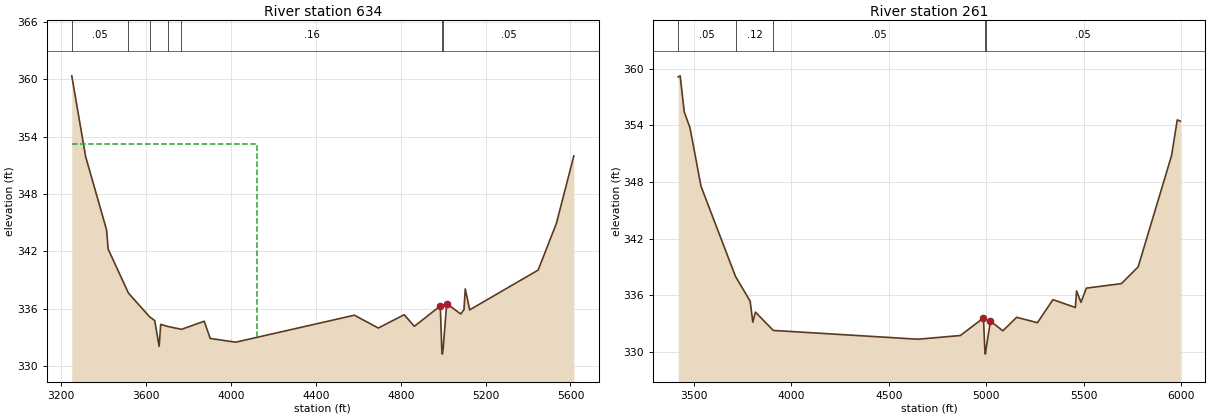
Type RM Length L Ch R = 1 ,634     ,373,373,373
BEGIN DESCRIPTION:
Mapping XS 70a28045
END DESCRIPTION:
XS GIS Cut Line= 4
      3722672.84     10663720.98      3721599.95     10664856.37
       3721573.9     10665127.21      3721885.51     10665558.27
#Sta/Elev= 30
  3249.7  360.36  3315.2   351.9  3413.9  344.24  3421.2  342.24  3516.9  337.64
  3616.2  335.17  3640.5  334.77  3661.5  332.07  3668.8  334.37  3701.3  334.16
  3766.8  333.85  3873.9   334.7  3902.2   332.9  4022.4  332.51  4581.5  335.33
  4694.3  333.99  4816.2  335.38  4864.2  334.17  4986.4   336.3  4993.5  331.76
  4996.2  331.26  4999.5  331.76  5016.6  336.54  5082.9  335.46    5098  335.91
  5104.1  338.08    5125  335.89  5447.6  340.05  5533.4  344.92  5615.8  351.99
#Mann= 7 ,-1 , 0
  3249.7     .05       0  3516.9     .12       0  3616.2     .16       0
  3701.3     .12       0  3766.8     .16       0  4993.5     .05       0
  4999.5     .05       0
#XS Ineff= 2 , 0
         4121.86  353.25
Permanent Ineff=
       F       F
Bank Sta=4986.4,5016.6
XS Rating Curve= 0 ,0
Exp/Cntr=0.3,0.1

Type RM Length L Ch R = 1 ,261     ,0,0,0
BEGIN DESCRIPTION:
UNT 0477 IN LACR 1.0
END DESCRIPTION:
XS GIS Cut Line= 4
      3722431.04      10663758.3      3721361.19     10664521.09
      3721317.78     10664859.63      3721861.65     10665600.85
#Sta/Elev= 30
  3419.6  359.13  3429.5  359.24  3450.4  355.42  3479.9  353.73  3536.4  347.54
  3713.3  337.99  3788.4  335.37  3802.1  333.15  3815.5  334.21  3907.1  332.27
  4648.9  331.34  4866.3  331.73  4984.7  333.59  4991.8  330.26  4994.5  329.76
  4997.8  330.26  5020.6  333.26  5084.1  332.23  5155.1  333.66  5261.6  333.09
  5341.1  335.53  5456.1   334.7  5462.3  336.45  5484.8  335.25  5512.4  336.75
  5692.2  337.23  5777.9     339  5949.2  350.78  5978.5  354.57  5994.2  354.44
#Mann= 5 ,-1 , 0
  3419.6     .05       0  3713.3     .12       0  3907.1     .05       0
  4991.8     .03       0  4997.8     .05       0
Bank Sta=4984.7,5020.6
XS Rating Curve= 0 ,0
Exp/Cntr=0.3,0.1

Chan Stop Cuts=-1
Use User Specified Reach Order=0
Composite Channel Slope=5