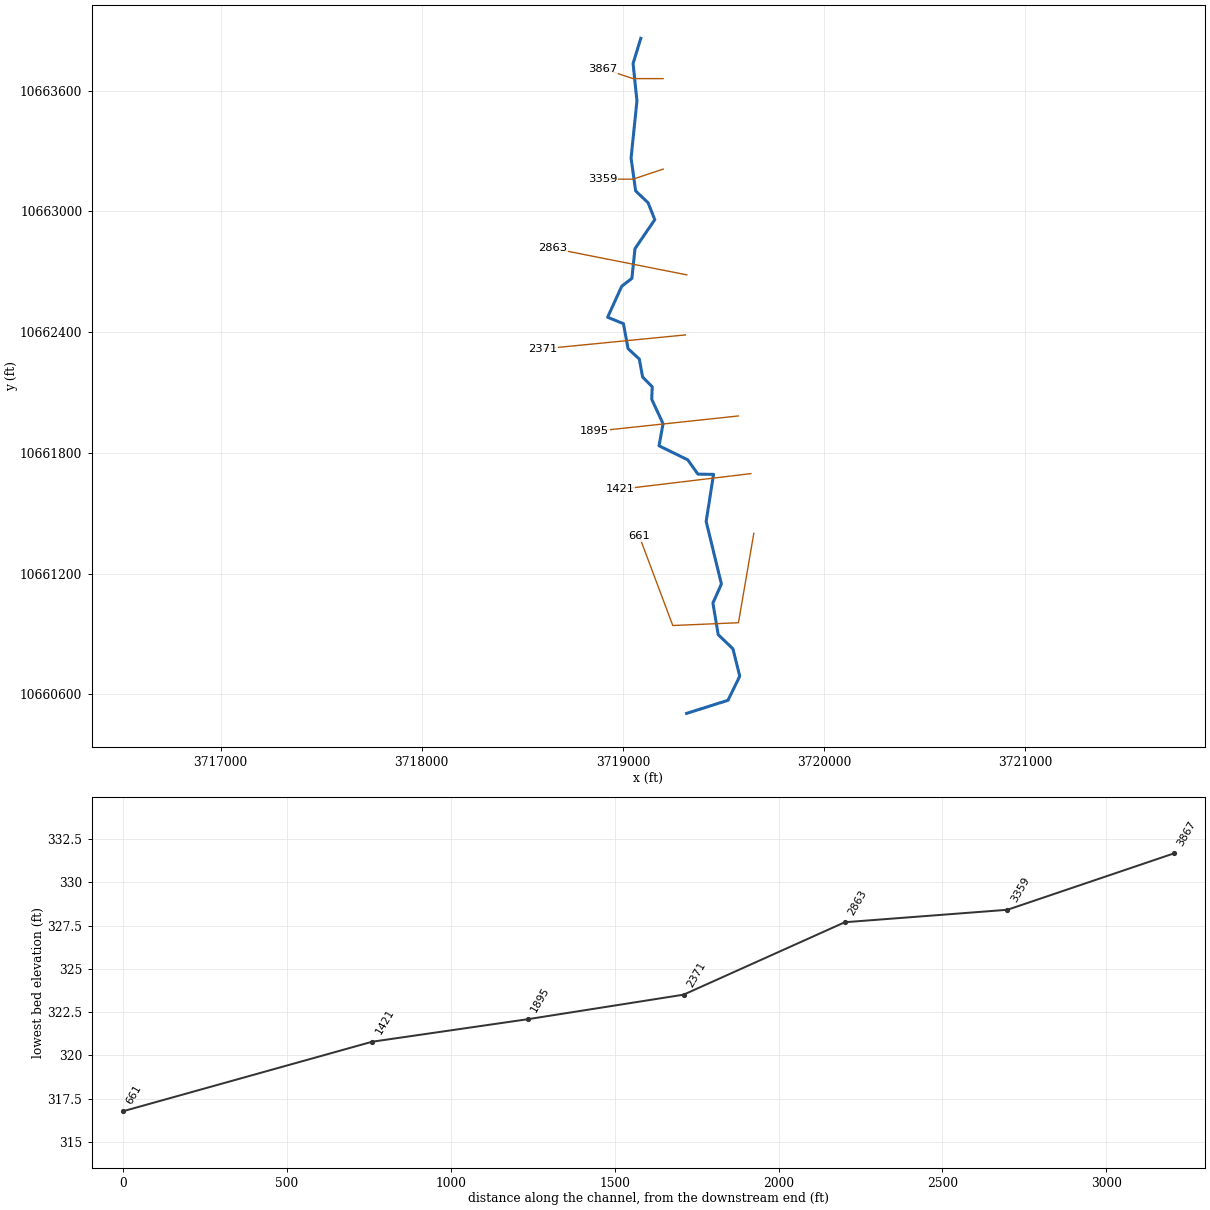
--- UNT 0478 IN LACR.prj (project) ---

Proj Title=UNT 0478 IN LACR Base Level Engineering
Current Plan=p01
Default Exp/Contr=0.3,0.1
English Units
Geom File=g01
Flow File=f01
Plan File=p01
BEGIN DESCRIPTION:
UNT 0478 IN LACR
END DESCRIPTION:

--- UNT 0478 IN LACR.p01 (plan) ---

Plan Title=Multiple Run
Short Identifier=Multiple
Geom File=g01
Flow File=f01
Subcritical Flow
K Sum by GR= 0
Std Step Tol= 0.01
Critical Tol= 0.01
Num of Std Step Trials= 20
Max Error Tol= 0.3
Flow Tol Ratio= 0.001
Split Flow NTrial= 30
Split Flow Tol= 0.02
Split Flow Ratio= 0.02
Log Output Level= 0
Friction Slope Method= 1
Unsteady Friction Slope Method= 2
Unsteady Bridges Friction Slope Method= 1
Parabolic Critical Depth
Global Vel Dist=  1 , 1 , 1
Global Log Level= 0
CheckData=True
Encroach Param= -1, 0, 0, 0
BEGIN DESCRIPTION:
Multiple Run
END DESCRIPTION:

--- UNT 0478 IN LACR.f01 (steady flow) ---

Flow Title=Multiple
Number of Profiles=7
Profile Names=10-year,25-year,50-year,1pct_min,100-year,1pct_plu,500-year
River Rch & RM= UNT 0478 IN LACR,Reach-1,3867
     470     627     755     668     904    1222    1300
Boundary for River Rch & Prof#=UNT 0478 IN LACR,Reach-1,1
Up Type=0
Dn Type=3
Dn Slope=0.005
Boundary for River Rch & Prof#=UNT 0478 IN LACR,Reach-1,2
Up Type=0
Dn Type=3
Dn Slope=0.005
Boundary for River Rch & Prof#=UNT 0478 IN LACR,Reach-1,3
Up Type=0
Dn Type=3
Dn Slope=0.005
Boundary for River Rch & Prof#=UNT 0478 IN LACR,Reach-1,4
Up Type=0
Dn Type=3
Dn Slope=0.005
Boundary for River Rch & Prof#=UNT 0478 IN LACR,Reach-1,5
Up Type=0
Dn Type=3
Dn Slope=0.005
Boundary for River Rch & Prof#=UNT 0478 IN LACR,Reach-1,6
Up Type=0
Dn Type=3
Dn Slope=0.005
Boundary for River Rch & Prof#=UNT 0478 IN LACR,Reach-1,7
Up Type=0
Dn Type=3
Dn Slope=0.005

--- UNT 0478 IN LACR.g01 (geometry) ---

Geom Title=Existing Conditions

River Reach=UNT 0478 IN LACR,Reach-1
Reach XY= 30
      3719088.61     10663860.29      3719050.25     10663735.00
      3719069.50     10663550.00      3719040.25     10663265.00
      3719063.00     10663102.00      3719124.75     10663043.00
      3719158.25     10662959.00      3719059.75     10662815.00
      3719044.25     10662667.00      3718993.75     10662628.00
      3718923.75     10662474.00      3719002.25     10662442.00
      3719025.25     10662318.00      3719081.25     10662266.00
      3719097.50     10662177.00      3719145.50     10662128.00
      3719143.00     10662066.00      3719199.25     10661945.00
      3719179.25     10661835.00      3719322.25     10661765.00
      3719372.50     10661694.00      3719450.25     10661693.00
      3719413.50     10661459.00      3719489.25     10661148.00
      3719447.00     10661053.00      3719473.50     10660896.00
      3719546.50     10660826.00      3719580.50     10660690.00
      3719522.00     10660570.00      3719316.50     10660505.00

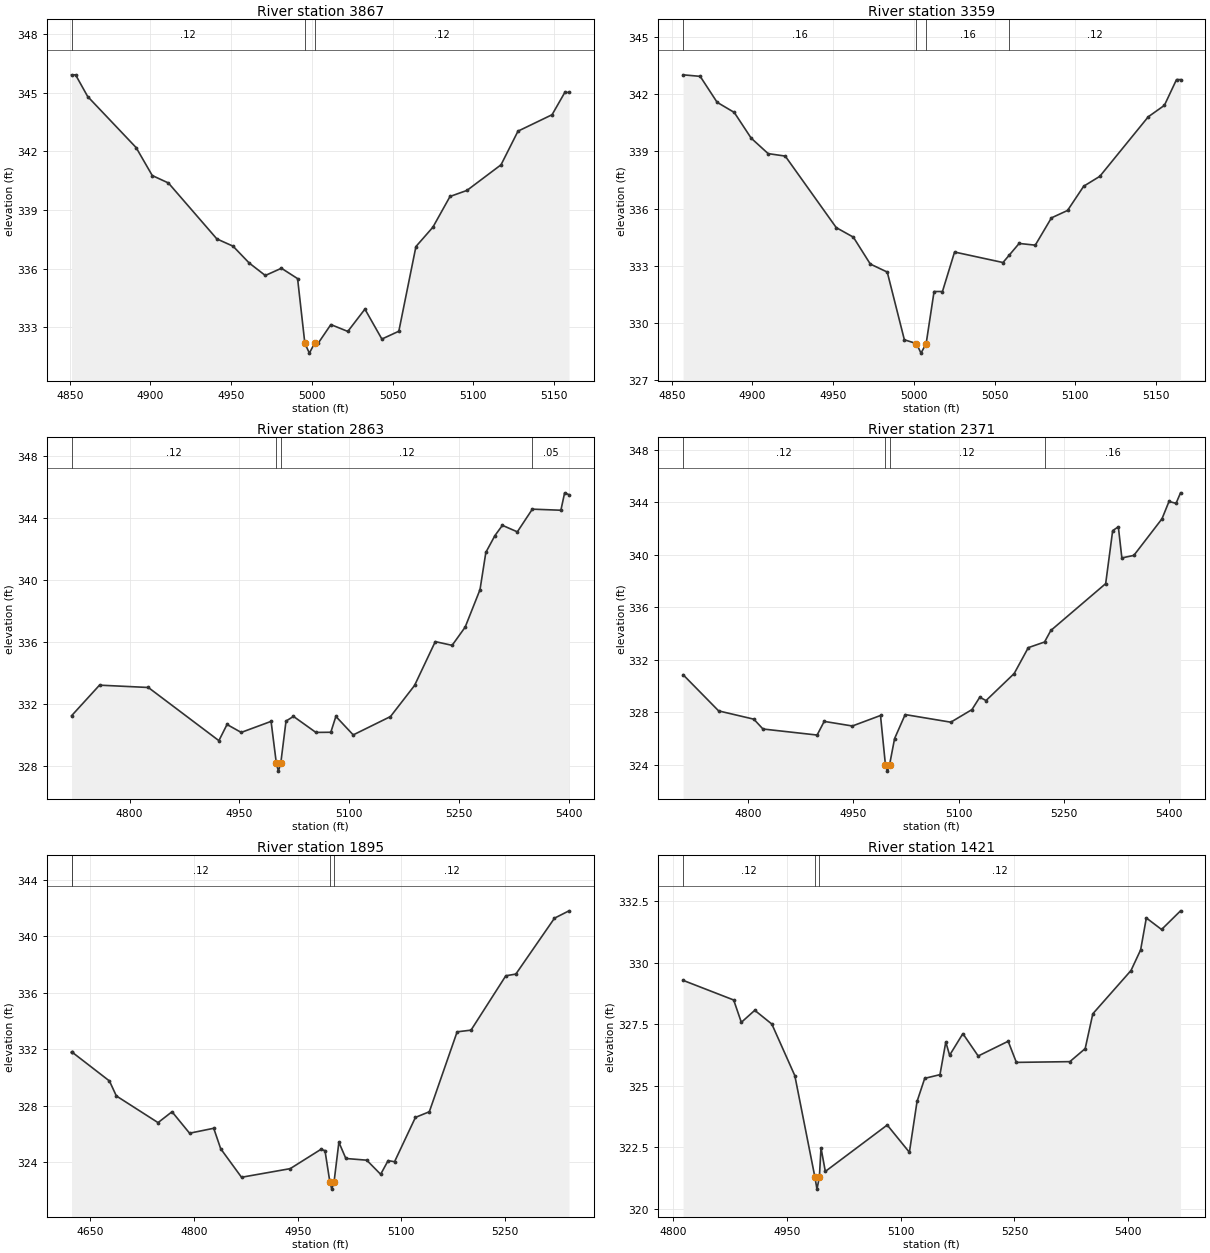
Type RM Length L Ch R = 1,3867,508,508,508
BEGIN DESCRIPTION:
UNT 0478 IN LACR 5.0
END DESCRIPTION:
XS GIS Cut Line= 3
      3719199.64     10663660.19      3719049.61     10663660.19
      3718899.65     10663710.17
#Sta/Elev= 30
  4851.1  345.91  4853.6  345.91  4861.1  344.80  4891.1  342.19  4901.1  340.76
  4911.1  340.38  4941.1  337.52  4951.1  337.15  4961.1  336.29  4971.1  335.65
  4981.1  336.02  4991.1  335.49  4995.6  332.18  4998.4  331.68  5001.6  332.18
  5003.8  332.18  5011.7  333.14  5022.2  332.79  5032.8  333.93  5043.3  332.40
  5053.8  332.80  5064.4  337.13  5074.9  338.12  5085.5  339.69  5096.0  340.00
  5117.1  341.31  5127.6  343.03  5148.7  343.87  5156.6  345.01  5159.2  345.01
#Mann=3,-1,0
  4851.1    0.12       0  4995.6    0.07       0  5001.6    0.12       0
Bank Sta=4995.6,5001.6
Exp/Cntr=0.3,0.1

Type RM Length L Ch R = 1,3359,496,496,496
BEGIN DESCRIPTION:
UNT 0478 IN LACR 4.0
END DESCRIPTION:
XS GIS Cut Line= 3
      3719199.65     10663210.20      3719049.61     10663160.19
      3718899.57     10663160.19
#Sta/Elev= 30
  4857.0  343.01  4867.6  342.93  4878.1  341.57  4888.7  341.04  4899.2  339.69
  4909.7  338.88  4920.3  338.75  4951.9  335.00  4962.5  334.50  4973.0  333.09
  4983.5  332.67  4994.1  329.12  5001.6  328.92  5004.4  328.42  5007.6  328.92
  5012.5  331.65  5017.7  331.65  5025.2  333.72  5055.2  333.17  5059.1  333.56
  5065.2  334.17  5075.2  334.08  5085.2  335.51  5095.2  335.90  5105.2  337.17
  5115.2  337.69  5145.2  340.81  5155.2  341.41  5162.7  342.76  5165.2  342.76
#Mann=4,-1,0
  4857.0    0.16       0  5001.6    0.07       0  5007.6    0.16       0
  5059.1    0.12       0
Bank Sta=5001.6,5007.6
Exp/Cntr=0.3,0.1

Type RM Length L Ch R = 1,2863,492,492,492
BEGIN DESCRIPTION:
UNT 0478 IN LACR 3.0
END DESCRIPTION:
XS GIS Cut Line= 2
      3719317.04     10662684.74      3718650.37     10662816.69
#Sta/Elev= 30
  4720.8  331.26  4759.0  333.23  4825.7  333.08  4922.1  329.66  4933.2  330.70
  4952.6  330.19  4993.4  330.90  5000.6  328.20  5003.4  327.70  5006.6  328.20
  5013.8  330.92  5024.0  331.22  5054.6  330.19  5075.0  330.20  5081.9  331.22
  5105.6  330.03  5156.5  331.21  5189.4  333.21  5217.7  336.03  5240.7  335.79
  5258.5  336.96  5278.8  339.37  5286.8  341.77  5299.2  342.85  5309.4  343.51
  5329.8  343.09  5350.3  344.55  5389.3  344.48  5394.4  345.60  5400.4  345.48
#Mann=4,-1,0
  4720.8    0.12       0  5000.6    0.07       0  5006.6    0.12       0
  5350.3    0.05       0
Bank Sta=5000.6,5006.6
Exp/Cntr=0.3,0.1

Type RM Length L Ch R = 1,2371,476,476,476
BEGIN DESCRIPTION:
UNT 0478 IN LACR 2.0
END DESCRIPTION:
XS GIS Cut Line= 2
      3719310.13     10662386.13      3718603.22     10662316.82
#Sta/Elev= 30
  4706.7  330.86  4757.5  328.10  4807.7  327.47  4820.8  326.72  4898.1  326.26
  4908.2  327.30  4948.4  326.95  4988.6  327.75  4995.6  324.01  4998.4  323.51
  5001.6  324.01  5008.7  325.99  5023.8  327.82  5089.0  327.24  5119.2  328.20
  5130.3  329.14  5139.3  328.89  5179.5  330.95  5199.6  332.92  5222.8  333.35
  5231.8  334.23  5310.1  337.80  5320.1  341.84  5328.2  342.13  5333.2  339.76
  5350.3  339.95  5390.5  342.74  5400.5  344.06  5410.6  343.92  5417.0  344.72
#Mann=4,-1,0
  4706.7    0.12       0  4995.6    0.07       0  5001.6    0.12       0
  5222.8    0.16       0
Bank Sta=4995.6,5001.6
Exp/Cntr=0.3,0.1

Type RM Length L Ch R = 1,1895,474,474,474
BEGIN DESCRIPTION:
Mapping XS e7a9574d
END DESCRIPTION:
XS GIS Cut Line= 2
      3719574.05     10661983.35      3718858.72     10661906.96
#Sta/Elev= 30
  4623.0  331.78  4624.1  331.78  4677.8  329.75  4687.8  328.69  4748.1  326.80
  4768.3  327.57  4793.7  326.05  4828.6  326.40  4838.7  324.95  4868.8  322.93
  4939.2  323.54  4983.4  324.90  4989.5  324.82  4996.6  322.59  4999.3  322.09
  5002.6  322.59  5009.6  325.41  5019.7  324.26  5049.9  324.14  5070.0  323.14
  5080.8  324.11  5090.1  324.03  5120.3  327.17  5140.4  327.57  5180.6  333.23
  5200.7  333.35  5251.0  337.20  5265.5  337.32  5321.4  341.28  5342.4  341.80
#Mann=4,-1,0
  4623.0    0.16       0  4624.1    0.12       0  4996.6    0.07       0
  5002.6    0.12       0
Bank Sta=4996.6,5002.6
Exp/Cntr=0.3,0.1

Type RM Length L Ch R = 1,1421,760,760,760
BEGIN DESCRIPTION:
Mapping XS 440253b6
END DESCRIPTION:
XS GIS Cut Line= 2
      3719635.82     10661696.76      3718984.79     10661618.63
#Sta/Elev= 30
  4813.3  329.29  4880.0  328.49  4890.1  327.58  4907.8  328.07  4930.3  327.51
  4960.6  325.41  4987.0  321.29  4989.8  320.79  4993.0  321.29  4995.1  322.47
  5000.8  321.51  5082.4  323.40  5111.6  322.29  5121.7  324.36  5131.8  325.30
  5151.9  325.45  5159.6  326.78  5164.6  326.24  5182.1  327.12  5202.3  326.21
  5241.8  326.81  5252.6  325.95  5323.1  325.98  5343.3  326.51  5353.4  327.93
  5403.7  329.69  5416.4  330.53  5423.9  331.83  5444.0  331.36  5469.0  332.12
#Mann=3,-1,0
  4813.3    0.12       0  4987.0    0.07       0  4993.0    0.12       0
Bank Sta=4987,4993
Exp/Cntr=0.3,0.1

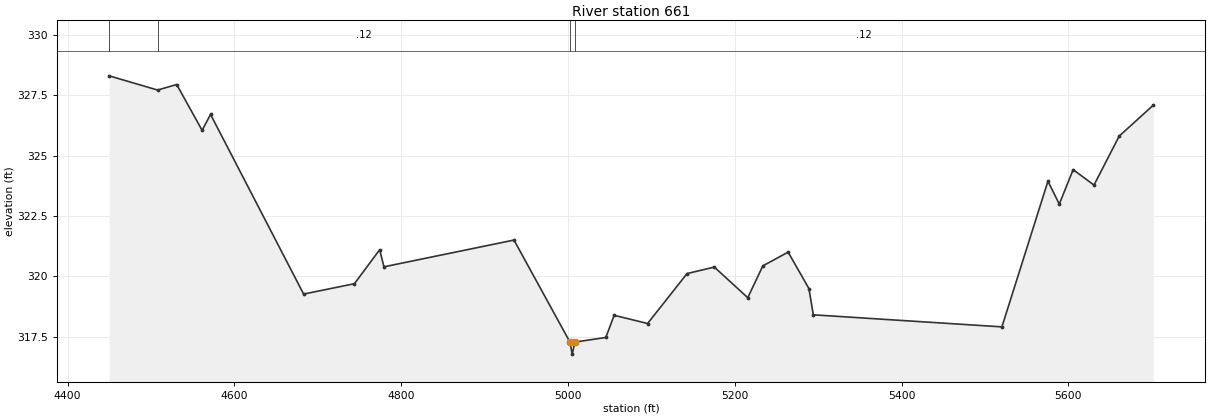
Type RM Length L Ch R = 1,661,0,0,0
BEGIN DESCRIPTION:
UNT 0478 IN LACR 1.0
END DESCRIPTION:
XS GIS Cut Line= 4
      3719650.39     10661400.04      3719574.00     10660955.57
      3719247.61     10660941.68      3719081.13     10661385.63
#Sta/Elev= 30
  4449.9  328.31  4508.0  327.72  4530.9  327.95  4561.4  326.05  4571.5  326.71
  4683.1  319.26  4744.0  319.69  4774.3  321.10  4779.4  320.39  4935.3  321.50
  5002.4  317.27  5005.1  316.77  5008.4  317.27  5045.4  317.46  5055.4  318.38
  5095.5  318.04  5142.8  320.11  5175.5  320.38  5215.6  319.11  5233.7  320.43
  5264.0  321.00  5288.9  319.49  5294.2  318.40  5520.3  317.90  5575.5  323.94
  5589.1  322.99  5605.7  324.42  5630.7  323.78  5660.9  325.81  5701.7  327.09
#Mann=4,-1,0
  4449.9    0.16       0  4508.0    0.12       0  5002.4    0.07       0
  5008.4    0.12       0
Bank Sta=5002.4,5008.4
Exp/Cntr=0.3,0.1

Chan Stop Cuts=-1