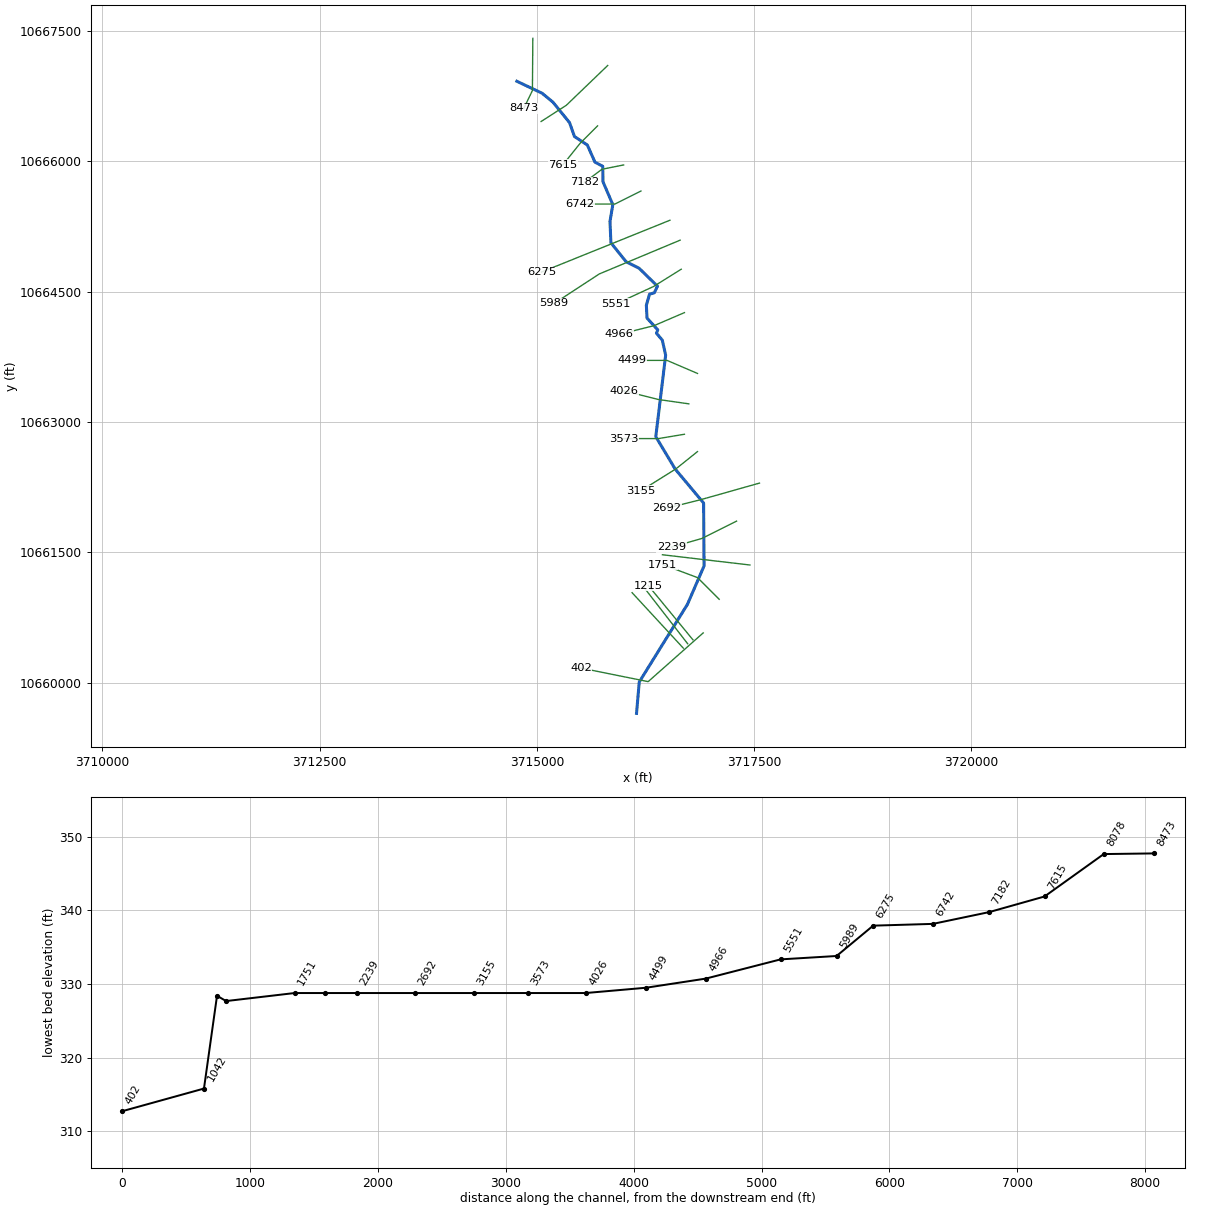
--- UNT 0479 IN LACR.prj (project) ---

Proj Title=UNT 0479 IN LACR Base Level Engineering
Current Plan=p01
Default Exp/Contr=0.3,0.1
English Units
Geom File=g01
Flow File=f01
Plan File=p01
BEGIN DESCRIPTION:
UNT 0479 IN LACR
END DESCRIPTION:

--- UNT 0479 IN LACR.p01 (plan) ---

Plan Title=Multiple Run
Short Identifier=Multiple
Geom File=g01
Flow File=f01
Subcritical Flow
K Sum by GR= 0
Std Step Tol= 0.01
Critical Tol= 0.01
Num of Std Step Trials= 20
Max Error Tol= 0.3
Flow Tol Ratio= 0.001
Split Flow NTrial= 30
Split Flow Tol= 0.02
Split Flow Ratio= 0.02
Log Output Level= 0
Friction Slope Method= 1
Unsteady Friction Slope Method= 2
Unsteady Bridges Friction Slope Method= 1
Parabolic Critical Depth
Global Vel Dist=  1 , 1 , 1
Global Log Level= 0
CheckData=True
Encroach Param= -1, 0, 0, 0
BEGIN DESCRIPTION:
Multiple Run
END DESCRIPTION:

--- UNT 0479 IN LACR.f01 (steady flow) ---

Flow Title=Multiple
Number of Profiles=7
Profile Names=10-year,25-year,50-year,1pct_min,100-year,1pct_plu,500-year
River Rch & RM= UNT 0479 IN LACR,Reach-1,8473
     869    1199    1476    1334    1804    2440    2706
Boundary for River Rch & Prof#=UNT 0479 IN LACR,Reach-1,1
Up Type=0
Dn Type=3
Dn Slope=0.005
Boundary for River Rch & Prof#=UNT 0479 IN LACR,Reach-1,2
Up Type=0
Dn Type=3
Dn Slope=0.005
Boundary for River Rch & Prof#=UNT 0479 IN LACR,Reach-1,3
Up Type=0
Dn Type=3
Dn Slope=0.005
Boundary for River Rch & Prof#=UNT 0479 IN LACR,Reach-1,4
Up Type=0
Dn Type=3
Dn Slope=0.005
Boundary for River Rch & Prof#=UNT 0479 IN LACR,Reach-1,5
Up Type=0
Dn Type=3
Dn Slope=0.005
Boundary for River Rch & Prof#=UNT 0479 IN LACR,Reach-1,6
Up Type=0
Dn Type=3
Dn Slope=0.005
Boundary for River Rch & Prof#=UNT 0479 IN LACR,Reach-1,7
Up Type=0
Dn Type=3
Dn Slope=0.005

--- UNT 0479 IN LACR.g01 (geometry) ---

Geom Title=Existing Conditions

River Reach=UNT 0479 IN LACR,Reach-1
Reach XY= 30
      3714770.75     10666923.40      3715062.00     10666785.00
      3715185.75     10666683.00      3715376.50     10666448.00
      3715434.00     10666287.00      3715581.50     10666190.00
      3715669.25     10665993.00      3715759.25     10665944.00
      3715762.25     10665766.00      3715875.00     10665503.00
      3715842.50     10665310.00      3715853.25     10665064.00
      3716028.00     10664846.00      3716176.00     10664772.00
      3716389.25     10664565.00      3716353.00     10664489.00
      3716297.50     10664472.00      3716261.25     10664345.00
      3716268.75     10664197.00      3716392.50     10664062.00
      3716377.75     10664023.00      3716445.00     10663943.00
      3716483.25     10663770.00      3716369.75     10662832.00
      3716593.50     10662459.00      3716920.25     10662068.00
      3716925.50     10661344.00      3716734.00     10660902.00
      3716179.50     10660008.00      3716148.00     10659647.00

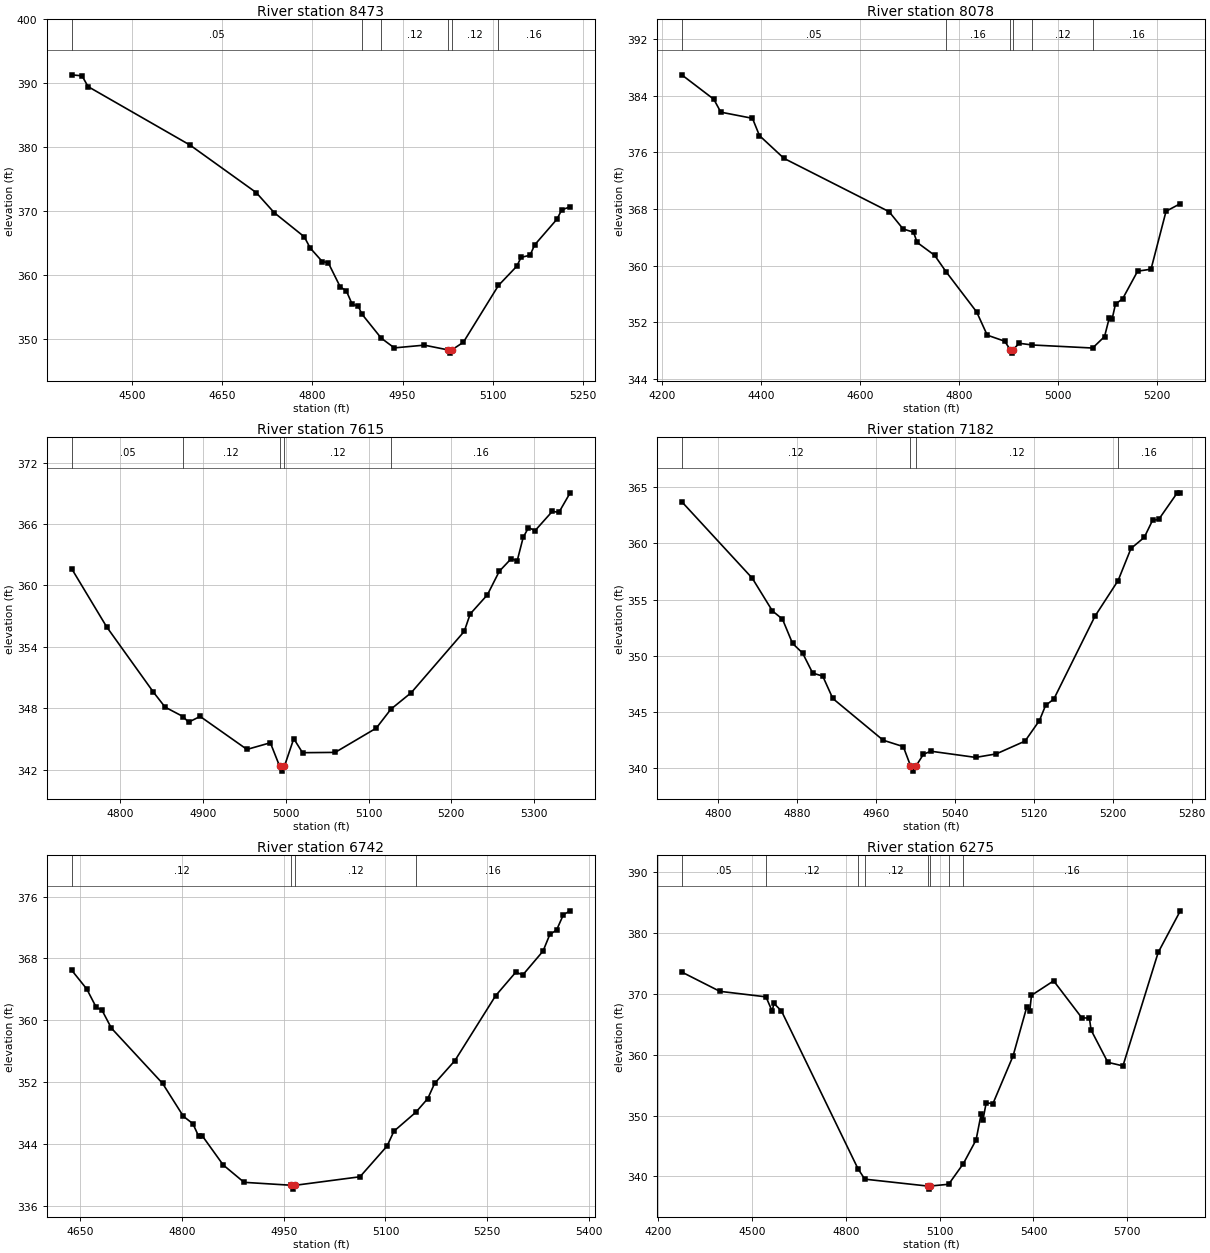
Type RM Length L Ch R = 1,8473,395,395,395
BEGIN DESCRIPTION:
UNT 0479 IN LACR 18.0
END DESCRIPTION:
XS GIS Cut Line= 3
      3714954.25     10667417.63      3714949.61     10666816.45
      3714849.62     10666610.21
#Sta/Elev= 30
  4398.8  391.30  4416.2  391.14  4426.2  389.46  4596.2  380.29  4706.2  372.87
  4736.2  369.72  4786.3  365.94  4796.3  364.17  4816.3  362.06  4826.3  361.87
  4846.3  358.08  4856.3  357.49  4866.3  355.34  4876.3  355.10  4881.8  353.90
  4914.5  350.07  4936.3  348.54  4986.3  348.97  5026.0  348.22  5028.8  347.72
  5032.0  348.22  5051.4  349.43  5109.8  358.32  5140.3  361.33  5147.4  362.71
  5162.5  363.06  5170.0  364.66  5207.0  368.67  5215.2  370.15  5229.2  370.64
#Mann=6,-1,0
  4398.8    0.05       0  4881.8    0.16       0  4914.5    0.12       0
  5026.0    0.07       0  5032.0    0.12       0  5109.8    0.16       0
Bank Sta=5026,5032
Exp/Cntr=0.3,0.1

Type RM Length L Ch R = 1,8078,463,463,463
BEGIN DESCRIPTION:
UNT 0479 IN LACR 17.0
END DESCRIPTION:
XS GIS Cut Line= 3
      3715816.26     10667105.20      3715339.67     10666646.84
      3715049.58     10666460.17
#Sta/Elev= 30
  4240.3  386.92  4305.0  383.47  4319.1  381.65  4383.0  380.78  4397.1  378.34
  4446.5  375.13  4658.7  367.60  4687.0  365.16  4708.1  364.70  4715.3  363.26
  4750.6  361.44  4773.6  359.13  4835.5  353.44  4856.8  350.17  4892.1  349.31
  4903.1  348.13  4905.8  347.63  4909.1  348.13  4921.3  349.02  4947.7  348.78
  5069.5  348.35  5093.6  349.97  5102.8  352.52  5108.8  352.43  5115.7  354.57
  5129.9  355.28  5160.3  359.20  5187.4  359.48  5217.7  367.66  5246.5  368.73
#Mann=6,-1,0
  4240.3    0.05       0  4773.6    0.16       0  4903.1    0.07       0
  4909.1    0.16       0  4947.7    0.12       0  5069.5    0.16       0
Bank Sta=4903.1,4909.1
Exp/Cntr=0.3,0.1

Type RM Length L Ch R = 1,7615,433,433,433
BEGIN DESCRIPTION:
UNT 0479 IN LACR 16.0
END DESCRIPTION:
XS GIS Cut Line= 3
      3715699.60     10666410.18      3715499.61     10666210.19
      3715299.60     10665960.17
#Sta/Elev= 30
  4740.9  361.65  4783.3  355.96  4839.9  349.58  4854.0  348.12  4875.7  347.20
  4882.3  346.65  4896.4  347.21  4953.0  343.99  4981.3  344.64  4992.4  342.37
  4995.2  341.87  4998.4  342.37  5009.6  345.04  5020.2  343.67  5059.7  343.70
  5109.4  346.07  5127.1  347.92  5151.8  349.54  5215.8  355.52  5223.0  357.22
  5243.8  359.09  5258.2  361.39  5272.6  362.62  5279.8  362.40  5287.1  364.70
  5293.5  365.65  5301.5  365.36  5322.3  367.24  5330.3  367.14  5343.9  369.05
#Mann=5,-1,0
  4740.9    0.05       0  4875.7    0.12       0  4992.4    0.07       0
  4998.4    0.12       0  5127.1    0.16       0
Bank Sta=4992.4,4998.4
Exp/Cntr=0.3,0.1

Type RM Length L Ch R = 1,7182,440,440,440
BEGIN DESCRIPTION:
UNT 0479 IN LACR 15.0
END DESCRIPTION:
XS GIS Cut Line= 3
      3715999.66     10665960.20      3715749.61     10665910.19
      3715549.61     10665760.19
#Sta/Elev= 30
  4763.5  363.71  4834.9  356.91  4855.3  354.00  4865.5  353.27  4875.7  351.11
  4885.9  350.25  4896.1  348.47  4906.3  348.20  4916.5  346.21  4967.5  342.50
  4987.9  341.93  4995.1  340.25  4997.9  339.75  5001.1  340.25  5008.3  341.25
  5015.9  341.52  5061.2  340.97  5082.0  341.28  5111.2  342.42  5125.8  344.25
  5132.0  345.59  5140.4  346.16  5182.0  353.52  5205.5  356.70  5218.5  359.55
  5232.0  360.54  5240.4  362.06  5246.6  362.13  5265.4  364.50  5268.5  364.50
#Mann=4,-1,0
  4763.5    0.12       0  4995.1    0.07       0  5001.1    0.12       0
  5205.5    0.16       0
Bank Sta=4995.1,5001.1
Exp/Cntr=0.3,0.1

Type RM Length L Ch R = 1,6742,467,467,467
BEGIN DESCRIPTION:
UNT 0479 IN LACR 14.0
END DESCRIPTION:
XS GIS Cut Line= 3
      3716199.64     10665660.20      3715899.61     10665510.19
      3715499.65     10665510.19
#Sta/Elev= 30
  4637.0  366.49  4659.4  364.04  4673.4  361.66  4681.8  361.31  4695.7  358.98
  4771.2  351.83  4801.9  347.57  4815.9  346.62  4824.3  345.01  4829.9  345.03
  4860.6  341.28  4891.4  339.03  4961.1  338.65  4963.8  338.15  4967.1  338.65
  5062.4  339.75  5102.4  343.73  5112.4  345.64  5144.8  348.10  5162.4  349.87
  5172.4  351.82  5202.4  354.78  5262.4  363.17  5292.4  366.24  5302.4  365.85
  5332.4  368.95  5342.4  371.10  5352.4  371.68  5362.4  373.66  5372.4  374.16
#Mann=4,-1,0
  4637.0    0.12       0  4961.1    0.07       0  4967.1    0.12       0
  5144.8    0.16       0
Bank Sta=4961.1,4967.1
Exp/Cntr=0.3,0.1

Type RM Length L Ch R = 1,6275,286,286,286
BEGIN DESCRIPTION:
UNT 0479 IN LACR 13.0
END DESCRIPTION:
XS GIS Cut Line= 2
      3716532.37     10665323.64      3715053.93     10664726.71
#Sta/Elev= 30
  4275.3  373.62  4396.9  370.45  4544.6  369.54  4564.5  367.18  4569.9  368.47
  4594.0  367.23  4839.2  341.23  4860.7  339.55  5062.5  338.41  5065.3  337.91
  5068.5  338.41  5128.8  338.71  5175.9  342.11  5216.5  346.00  5232.7  350.26
  5238.1  349.20  5248.9  352.11  5270.4  351.97  5334.7  359.80  5378.3  367.80
  5388.3  367.27  5393.7  369.79  5464.6  372.17  5554.7  366.09  5578.9  366.04
  5584.3  364.08  5637.9  358.77  5686.2  358.18  5798.9  376.84  5869.7  383.69
#Mann=8,-1,0
  4275.3    0.05       0  4544.6    0.12       0  4839.2    0.05       0
  4860.7    0.12       0  5062.5    0.07       0  5068.5    0.12       0
  5128.8    0.05       0  5175.9    0.16       0
Bank Sta=5062.5,5068.5
Exp/Cntr=0.3,0.1

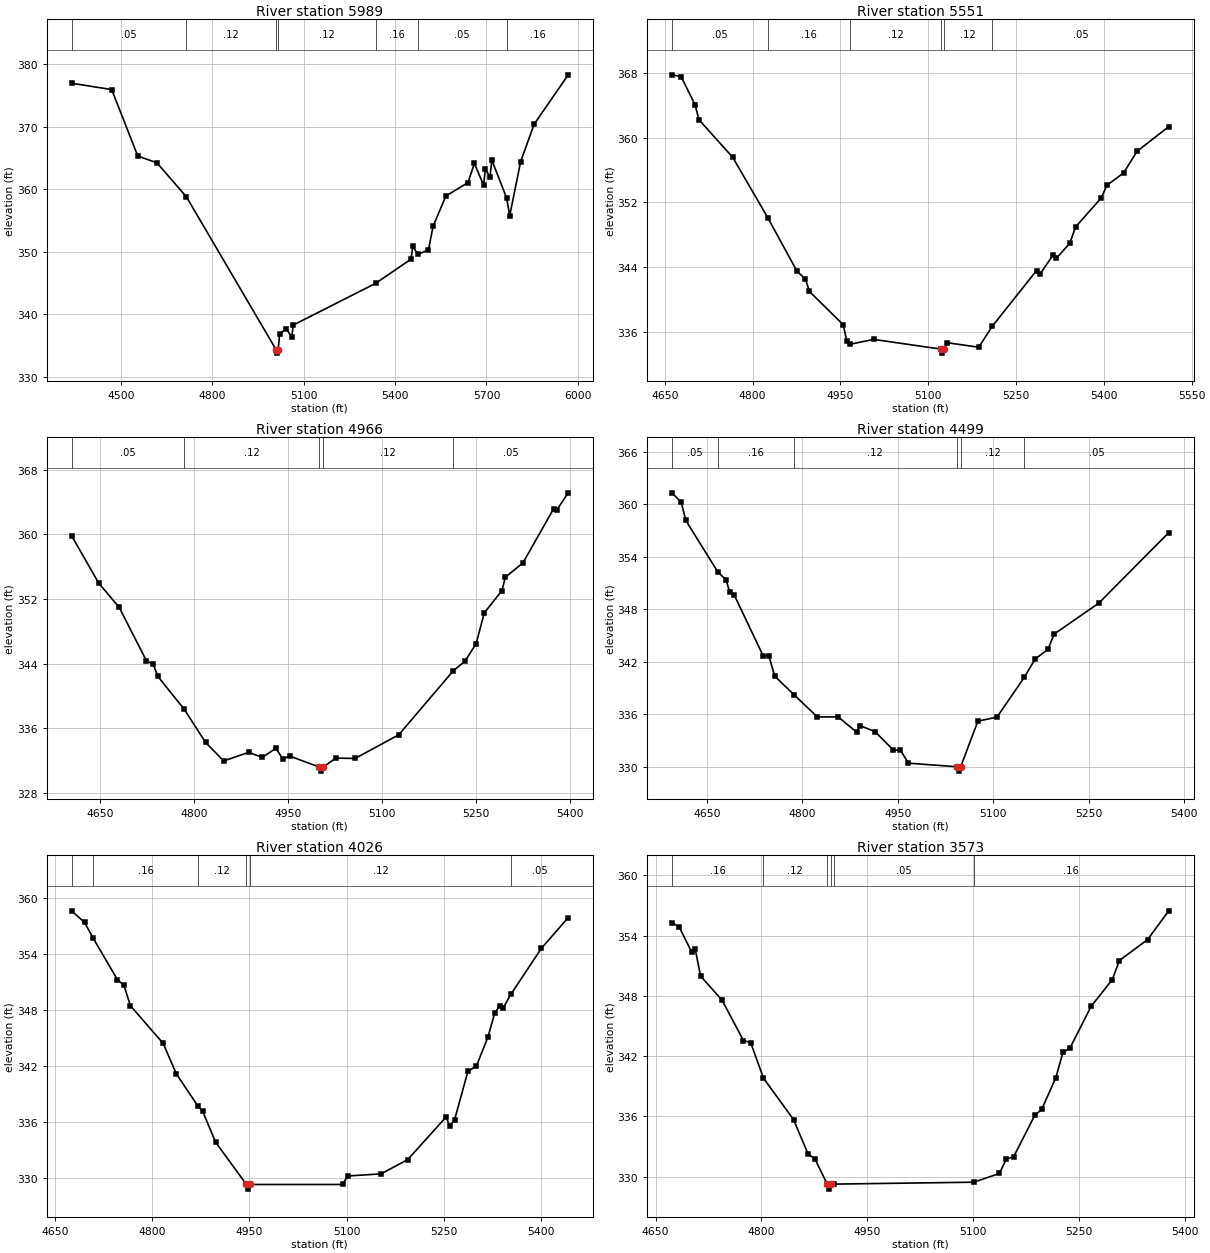
Type RM Length L Ch R = 1,5989,438,438,438
BEGIN DESCRIPTION:
UNT 0479 IN LACR 12.0
END DESCRIPTION:
XS GIS Cut Line= 3
      3716650.37     10665094.45      3715719.83     10664705.57
      3715198.97     10664365.27
#Sta/Elev= 30
  4337.6  376.93  4469.6  375.91  4555.2  365.29  4617.9  364.22  4715.0  358.76
  5009.9  334.29  5012.6  333.79  5015.9  334.29  5021.2  336.89  5042.9  337.68
  5060.5  336.35  5065.9  338.28  5335.9  344.94  5452.2  348.80  5458.2  350.84
  5475.1  349.60  5509.5  350.26  5524.6  354.04  5566.8  358.91  5639.2  361.04
  5660.3  364.10  5690.5  360.67  5696.5  363.22  5711.6  361.92  5717.6  364.65
  5766.1  358.60  5776.4  355.78  5812.3  364.41  5856.4  370.36  5968.3  378.27
#Mann=7,-1,0
  4337.6    0.05       0  4715.0    0.12       0  5009.9    0.07       0
  5015.9    0.12       0  5335.9    0.16       0  5475.1    0.05       0
  5766.1    0.16       0
Bank Sta=5009.9,5015.9
Exp/Cntr=0.3,0.1

Type RM Length L Ch R = 1,5551,585,585,585
BEGIN DESCRIPTION:
UNT 0479 IN LACR 11.0
END DESCRIPTION:
XS GIS Cut Line= 3
      3716662.86     10664760.05      3716344.89     10664561.31
      3715915.07     10664362.60
#Sta/Elev= 30
  4662.3  367.79  4677.9  367.56  4701.5  364.11  4708.3  362.23  4766.1  357.56
  4826.3  350.04  4875.8  343.47  4890.2  342.50  4897.0  340.97  4954.8  336.84
  4960.9  334.77  4966.6  334.43  5006.7  335.03  5121.5  333.83  5124.3  333.33
  5127.5  333.83  5131.2  334.63  5186.3  334.06  5209.5  336.67  5285.1  343.56
  5290.6  343.08  5313.5  345.50  5319.0  345.09  5341.9  346.94  5351.6  348.95
  5395.6  352.55  5405.2  354.11  5433.7  355.64  5456.6  358.31  5510.8  361.38
#Mann=6,-1,0
  4662.3    0.05       0  4826.3    0.16       0  4966.6    0.12       0
  5121.5    0.07       0  5127.5    0.12       0  5209.5    0.05       0
Bank Sta=5121.5,5127.5
Exp/Cntr=0.3,0.1

Type RM Length L Ch R = 1,4966,467,467,467
BEGIN DESCRIPTION:
UNT 0479 IN LACR 10.0
END DESCRIPTION:
XS GIS Cut Line= 3
      3716699.61     10664260.19      3716349.61     10664110.19
      3715949.61     10664010.19
#Sta/Elev= 30
  4603.7  359.85  4647.2  353.97  4679.9  350.97  4723.4  344.36  4734.3  343.93
  4741.5  342.44  4783.4  338.40  4817.7  334.28  4846.7  331.98  4886.6  333.04
  4908.3  332.42  4930.1  333.54  4941.0  332.24  4951.9  332.59  4999.5  331.22
  5002.3  330.72  5005.5  331.22  5025.7  332.33  5056.6  332.29  5126.2  335.21
  5213.5  343.14  5231.9  344.31  5249.9  346.50  5262.8  350.29  5291.1  353.05
  5296.3  354.69  5324.6  356.48  5373.6  363.18  5378.8  363.03  5396.8  365.14
#Mann=5,-1,0
  4603.7    0.05       0  4783.4    0.12       0  4999.5    0.07       0
  5005.5    0.12       0  5213.5    0.05       0
Bank Sta=4999.5,5005.5
Exp/Cntr=0.3,0.1

Type RM Length L Ch R = 1,4499,473,473,473
BEGIN DESCRIPTION:
UNT 0479 IN LACR 9.0
END DESCRIPTION:
XS GIS Cut Line= 3
      3716849.59     10663560.20      3716499.61     10663710.19
      3716099.58     10663710.19
#Sta/Elev= 30
  4595.0  361.28  4609.5  360.18  4616.7  358.12  4666.5  352.29  4680.2  351.30
  4685.6  349.91  4692.9  349.59  4738.2  342.66  4747.3  342.63  4756.4  340.34
  4786.4  338.23  4823.5  335.67  4856.1  335.68  4885.1  333.94  4890.5  334.68
  4914.1  334.00  4943.1  331.87  4954.0  331.87  4966.7  330.39  5042.8  329.98
  5045.5  329.48  5048.8  329.98  5075.8  335.19  5105.8  335.65  5148.9  340.21
  5165.8  342.29  5185.8  343.38  5195.8  345.15  5265.8  348.67  5375.8  356.73
#Mann=6,-1,0
  4595.0    0.05       0  4666.5    0.16       0  4786.4    0.12       0
  5042.8    0.07       0  5048.8    0.12       0  5148.9    0.05       0
Bank Sta=5042.8,5048.8
Exp/Cntr=0.3,0.1

Type RM Length L Ch R = 1,4026,453,453,453
BEGIN DESCRIPTION:
UNT 0479 IN LACR 8.0
END DESCRIPTION:
XS GIS Cut Line= 3
      3716749.58     10663210.19      3716399.61     10663260.19
      3715999.64     10663360.18
#Sta/Elev= 30
  4675.9  358.66  4696.1  357.41  4708.9  355.77  4746.6  351.28  4756.7  350.66
  4766.8  348.46  4817.3  344.41  4837.5  341.15  4871.1  337.65  4877.9  337.16
  4898.1  333.80  4945.6  329.26  4948.4  328.76  4951.6  329.26  5093.8  329.26
  5101.6  330.17  5153.1  330.40  5194.3  331.93  5253.6  336.52  5258.8  335.54
  5266.5  336.20  5287.1  341.42  5300.0  341.96  5318.0  345.10  5328.3  347.65
  5336.1  348.48  5341.2  348.18  5353.4  349.70  5400.5  354.64  5441.7  357.93
#Mann=6,-1,0
  4675.9    0.05       0  4708.9    0.16       0  4871.1    0.12       0
  4945.6    0.07       0  4951.6    0.12       0  5353.4    0.05       0
Bank Sta=4945.6,4951.6
Exp/Cntr=0.3,0.1

Type RM Length L Ch R = 1,3573,418,418,418
BEGIN DESCRIPTION:
UNT 0479 IN LACR 7.0
END DESCRIPTION:
XS GIS Cut Line= 3
      3716699.56     10662860.18      3716399.61     10662810.19
      3715999.60     10662810.19
#Sta/Elev= 30
  4673.3  355.28  4683.4  354.88  4701.1  352.38  4706.2  352.66  4713.8  349.98
  4744.2  347.58  4774.6  343.56  4784.8  343.35  4802.9  339.82  4845.6  335.68
  4865.9  332.30  4876.0  331.74  4893.3  329.26  4896.0  328.76  4899.3  329.26
  4902.6  329.26  5101.0  329.45  5137.4  330.32  5147.4  331.79  5157.4  331.96
  5187.4  336.10  5197.4  336.71  5217.4  339.87  5227.4  342.37  5237.4  342.81
  5267.4  346.97  5297.4  349.62  5307.4  351.53  5347.4  353.61  5377.4  356.48
#Mann=6,-1,0
  4673.3    0.16       0  4802.9    0.12       0  4893.3   0.033       0
  4899.3    0.12       0  4902.6    0.05       0  5101.0    0.16       0
Bank Sta=4893.3,4899.3
Exp/Cntr=0.3,0.1

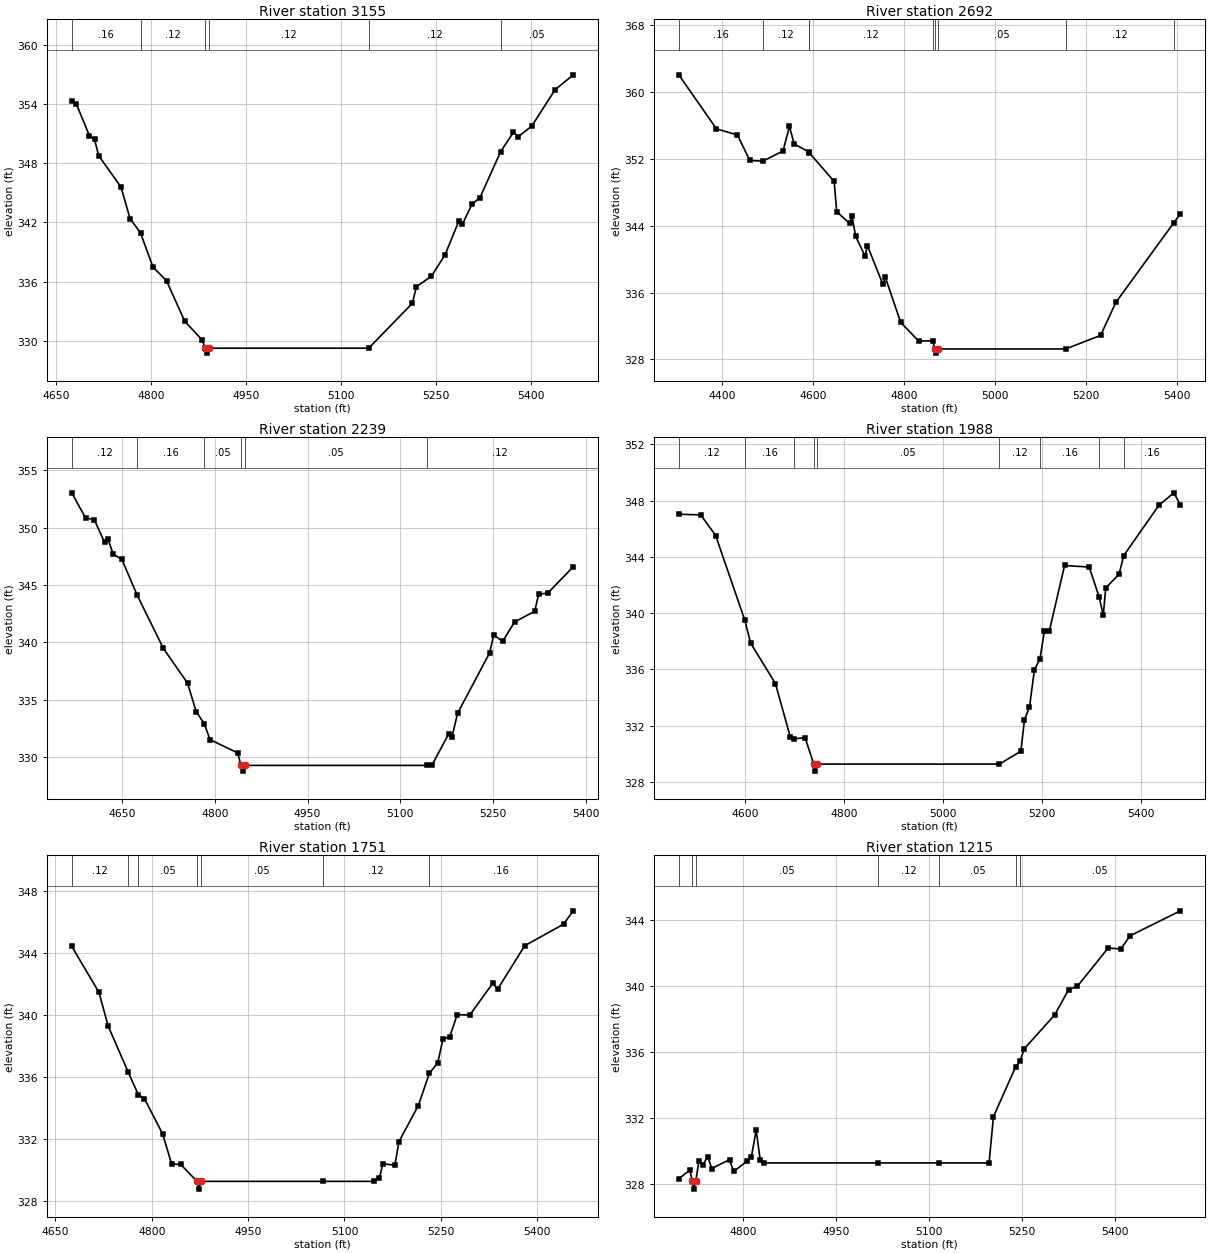
Type RM Length L Ch R = 1,3155,463,463,463
BEGIN DESCRIPTION:
UNT 0479 IN LACR 6.0
END DESCRIPTION:
XS GIS Cut Line= 3
      3716849.63     10662660.21      3716599.61     10662460.19
      3716199.60     10662210.18
#Sta/Elev= 30
  4674.5  354.29  4681.7  354.02  4702.5  350.78  4710.5  350.42  4717.0  348.77
  4752.2  345.60  4766.6  342.39  4783.1  340.95  4802.6  337.50  4824.2  336.08
  4853.0  331.98  4880.2  330.11  4885.2  329.26  4888.0  328.76  4891.2  329.26
  5143.4  329.26  5212.3  333.81  5218.7  335.49  5242.3  336.54  5264.1  338.74
  5285.4  342.10  5291.3  341.82  5306.6  343.87  5319.0  344.51  5351.8  349.19
  5372.0  351.14  5379.7  350.70  5400.9  351.77  5437.5  355.44  5466.4  356.96
#Mann=6,-1,0
  4674.5    0.16       0  4783.1    0.12       0  4885.2   0.033       0
  4891.2    0.12       0  5143.4    0.12       0  5351.8    0.05       0
Bank Sta=4885.2,4891.2
Exp/Cntr=0.3,0.1

Type RM Length L Ch R = 1,2692,453,453,453
BEGIN DESCRIPTION:
UNT 0479 IN LACR 5.0
END DESCRIPTION:
XS GIS Cut Line= 3
      3717563.65     10662297.89      3716895.01     10662109.04
      3716499.58     10662010.18
#Sta/Elev= 30
  4305.2  362.07  4388.0  355.60  4434.1  354.87  4461.2  351.83  4489.7  351.73
  4534.3  352.96  4548.4  355.89  4558.8  353.79  4590.3  352.87  4591.5  352.77
  4646.7  349.31  4652.3  345.69  4680.7  344.28  4685.9  345.19  4693.9  342.73
  4714.7  340.37  4719.8  341.63  4753.8  336.98  4759.0  337.85  4793.0  332.44
  4832.2  330.21  4863.0  330.23  4868.4  329.26  4871.1  328.76  4874.4  329.26
  5155.5  329.26  5232.3  330.88  5265.8  334.83  5393.0  344.35  5407.6  345.42
#Mann=9,-1,0
  4305.2    0.16       0  4489.7    0.12       0  4590.3    0.16       0
  4591.5    0.12       0  4863.0    0.05       0  4868.4   0.033       0
  4874.4    0.05       0  5155.5    0.12       0  5393.0     0.1       0
Bank Sta=4868.4,4874.4
Exp/Cntr=0.3,0.1

Type RM Length L Ch R = 1,2239,251,251,251
BEGIN DESCRIPTION:
UNT 0479 IN LACR 4.0
END DESCRIPTION:
XS GIS Cut Line= 3
      3717299.64     10661860.20      3716899.61     10661660.19
      3716549.66     10661560.20
#Sta/Elev= 30
  4568.6  353.05  4591.0  350.85  4605.0  350.72  4621.7  348.72  4627.3  348.99
  4635.7  347.70  4649.7  347.24  4674.5  344.11  4716.8  339.47  4755.9  336.44
  4769.9  333.95  4783.0  332.90  4792.2  331.51  4837.0  330.35  4842.3  329.26
  4845.1  328.76  4848.3  329.26  5142.7  329.26  5151.0  329.26  5178.3  332.01
  5183.5  331.71  5192.6  333.80  5244.6  339.09  5251.1  340.66  5265.4  340.08
  5284.9  341.78  5317.4  342.71  5323.9  344.22  5338.2  344.28  5379.8  346.60
#Mann=6,-1,0
  4568.6    0.12       0  4674.5    0.16       0  4783.0    0.05       0
  4842.3   0.033       0  4848.3    0.05       0  5142.7    0.12       0
Bank Sta=4842.3,4848.3
Exp/Cntr=0.3,0.1

Type RM Length L Ch R = 1,1988,237,237,237
BEGIN DESCRIPTION:
Mapping XS d598b5e7
END DESCRIPTION:
XS GIS Cut Line= 2
      3717453.58     10661354.92      3716446.67     10661472.97
#Sta/Elev= 30
  4466.7  347.04  4511.0  346.99  4541.2  345.52  4600.2  339.49  4611.7  337.88
  4662.0  334.99  4692.2  331.17  4700.3  331.06  4722.0  331.14  4739.5  329.26
  4742.3  328.76  4745.5  329.26  5114.9  329.26  5158.2  330.18  5165.4  332.41
  5175.5  333.31  5185.6  335.97  5196.7  336.73  5205.7  338.72  5215.8  338.75
  5246.5  343.39  5296.3  343.28  5316.6  341.12  5324.7  339.84  5329.7  341.79
  5356.7  342.78  5366.1  344.10  5437.3  347.68  5467.5  348.56  5480.5  347.71
#Mann=9,-1,0
  4466.7    0.12       0  4600.2    0.16       0  4700.3    0.05       0
  4739.5   0.033       0  4745.5    0.05       0  5114.9    0.12       0
  5196.7    0.16       0  5316.6    0.12       0  5366.1    0.16       0
Bank Sta=4739.5,4745.5
Exp/Cntr=0.3,0.1

Type RM Length L Ch R = 1,1751,536,536,536
BEGIN DESCRIPTION:
UNT 0479 IN LACR 3.0
END DESCRIPTION:
XS GIS Cut Line= 3
      3717099.58     10660960.21      3716849.61     10661210.19
      3716449.63     10661360.18
#Sta/Elev= 30
  4675.5  344.42  4717.9  341.45  4732.0  339.30  4763.2  336.32  4779.3  334.84
  4788.6  334.60  4816.9  332.33  4831.0  330.38  4845.2  330.35  4870.5  329.26
  4873.2  328.76  4876.5  329.26  5067.2  329.26  5146.5  329.26  5154.5  329.49
  5159.8  330.40  5178.5  330.30  5184.8  331.82  5215.0  334.15  5232.1  336.22
  5245.3  336.91  5253.3  338.44  5264.0  338.60  5275.5  340.01  5295.1  339.99
  5330.7  342.03  5338.7  341.67  5380.6  344.46  5441.1  345.85  5456.2  346.71
#Mann=7,-1,0
  4675.5    0.12       0  4763.2    0.16       0  4779.3    0.05       0
  4870.5   0.033       0  4876.5    0.05       0  5067.2    0.12       0
  5232.1    0.16       0
Bank Sta=4870.5,4876.5
Exp/Cntr=0.3,0.1

Type RM Length L Ch R = 1,1215,71,71,71
BEGIN DESCRIPTION:
UNT 0479 IN LACR 2.0
END DESCRIPTION:
XS GIS Cut Line= 2
      3716797.82     10660493.40      3716283.39     10661118.68
#Sta/Elev= 30
  4695.9  328.30  4713.9  328.83  4717.4  328.17  4720.2  327.67  4723.4  328.17
  4728.3  329.37  4734.7  329.14  4742.6  329.64  4749.1  328.92  4777.8  329.46
  4784.3  328.74  4806.5  329.38  4812.9  329.61  4820.8  331.24  4827.3  329.46
  4834.2  329.26  5017.3  329.26  5116.7  329.26  5196.8  329.26  5203.9  332.07
  5239.7  335.09  5246.7  335.43  5253.4  336.18  5302.9  338.25  5325.2  339.78
  5339.2  339.97  5389.0  342.30  5409.8  342.25  5424.2  343.04  5505.6  344.56
#Mann=7,-1,0
  4695.9    0.05       0  4717.4   0.033       0  4723.4    0.05       0
  5017.3    0.12       0  5116.7    0.05       0  5239.7    0.07       0
  5246.7    0.05       0
Bank Sta=4717.4,4723.4
Exp/Cntr=0.3,0.1

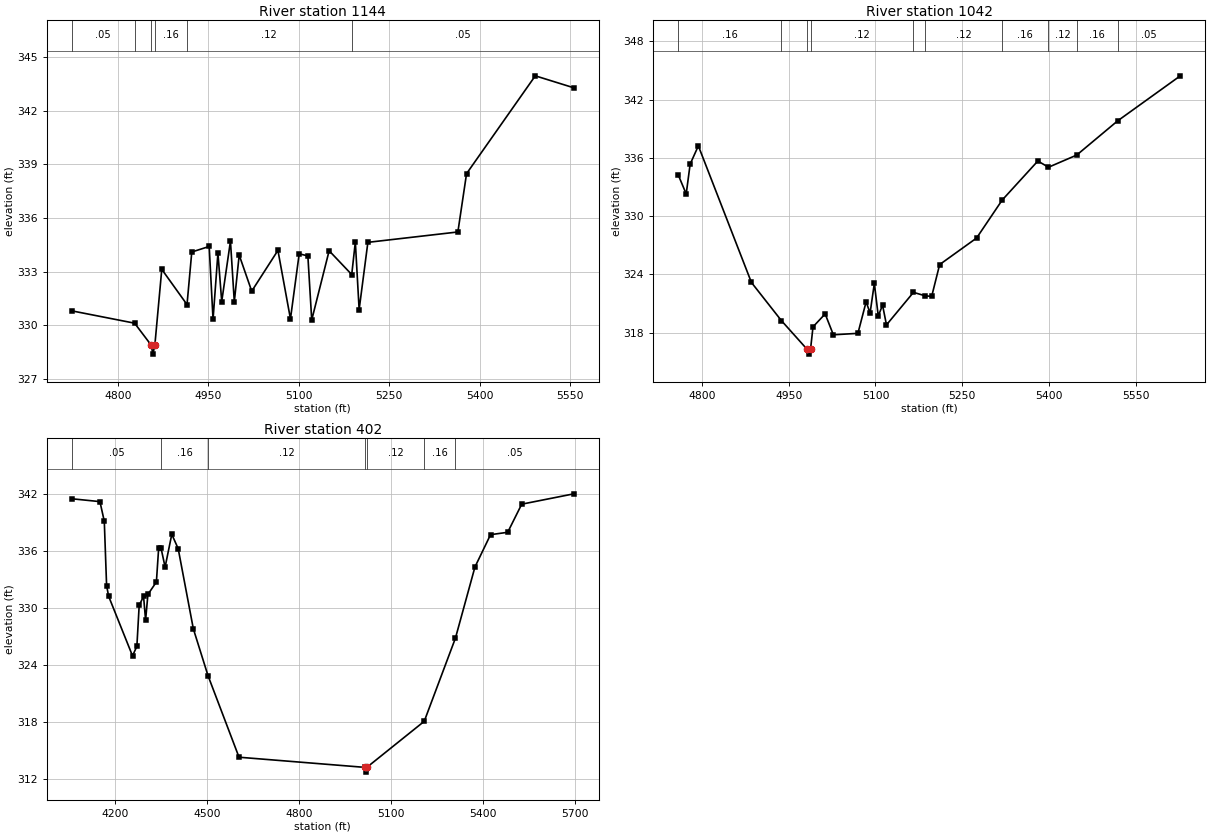
Type RM Length L Ch R = 1,1144,102,102,102
BEGIN DESCRIPTION:
Mapping XS 728dbd0c
END DESCRIPTION:
XS GIS Cut Line= 2
      3716737.04     10660448.27      3716225.99     10661106.58
#Sta/Elev= 30
  4723.1  330.81  4827.4  330.12  4855.0  328.89  4857.7  328.39  4861.0  328.89
  4872.5  333.13  4914.4  331.16  4922.3  334.10  4951.2  334.41  4957.6  330.33
  4965.7  334.04  4972.0  331.33  4986.5  334.71  4992.9  331.31  5001.0  333.93
  5021.8  331.91  5065.3  334.19  5086.1  330.36  5100.6  334.00  5115.0  333.88
  5121.4  330.30  5150.3  334.17  5187.8  332.84  5193.8  334.66  5200.1  330.88
  5214.6  334.64  5364.0  335.22  5378.4  338.48  5492.5  343.95  5556.5  343.28
#Mann=6,-1,0
  4723.1    0.05       0  4827.4    0.16       0  4855.0    0.07       0
  4861.0    0.16       0  4914.4    0.12       0  5187.8    0.05       0
Bank Sta=4855,4861
Exp/Cntr=0.3,0.1

Type RM Length L Ch R = 1,1042,640,640,640
BEGIN DESCRIPTION:
Mapping XS 8575b5e9
END DESCRIPTION:
XS GIS Cut Line= 2
      3716686.66     10660397.96      3716097.15     10661036.02
#Sta/Elev= 30
  4758.7  334.24  4772.5  332.28  4779.3  335.35  4793.5  337.23  4885.3  323.17
  4937.2  319.24  4981.6  316.29  4984.3  315.79  4987.6  316.29  4991.9  318.60
  5012.9  319.93  5027.1  317.78  5069.6  317.93  5083.8  321.18  5090.6  320.01
  5098.0  323.07  5104.8  319.71  5112.2  320.84  5119.0  318.80  5165.7  322.15
  5185.5  321.80  5197.2  321.73  5211.0  325.01  5274.9  327.74  5319.2  331.65
  5380.9  335.67  5399.3  335.03  5448.1  336.28  5518.9  339.80  5627.4  344.44
#Mann=10,-1,0
  4758.7    0.16       0  4937.2    0.12       0  4981.6    0.07       0
  4987.6    0.12       0  5165.7    0.16       0  5185.5    0.12       0
  5319.2    0.16       0  5399.3    0.12       0  5448.1    0.16       0
  5518.9    0.05       0
Bank Sta=4981.6,4987.6
Exp/Cntr=0.3,0.1

Type RM Length L Ch R = 1,402,0,0,0
BEGIN DESCRIPTION:
UNT 0479 IN LACR 1.0
END DESCRIPTION:
XS GIS Cut Line= 3
      3716915.88     10660573.74      3716282.17     10660012.52
      3715507.87     10660168.77
#Sta/Elev= 30
  4059.6  341.49  4151.4  341.19  4165.6  339.12  4173.1  332.35  4179.8  331.22
  4257.6  324.95  4271.8  325.96  4279.3  330.26  4293.6  331.22  4300.2  328.71
  4307.8  331.42  4335.4  332.73  4342.9  336.35  4350.5  336.30  4363.8  334.30
  4385.6  337.75  4406.5  336.23  4455.8  327.80  4503.6  322.87  4604.7  314.28
  5015.2  313.21  5018.0  312.71  5021.2  313.21  5208.4  318.06  5310.1  326.82
  5373.7  334.31  5424.5  337.71  5480.4  337.96  5526.1  340.92  5696.0  342.01
#Mann=7,-1,0
  4059.6    0.05       0  4350.5    0.16       0  4503.6    0.12       0
  5015.2    0.07       0  5021.2    0.12       0  5208.4    0.16       0
  5310.1    0.05       0
Bank Sta=5015.2,5021.2
Exp/Cntr=0.3,0.1

Chan Stop Cuts=-1