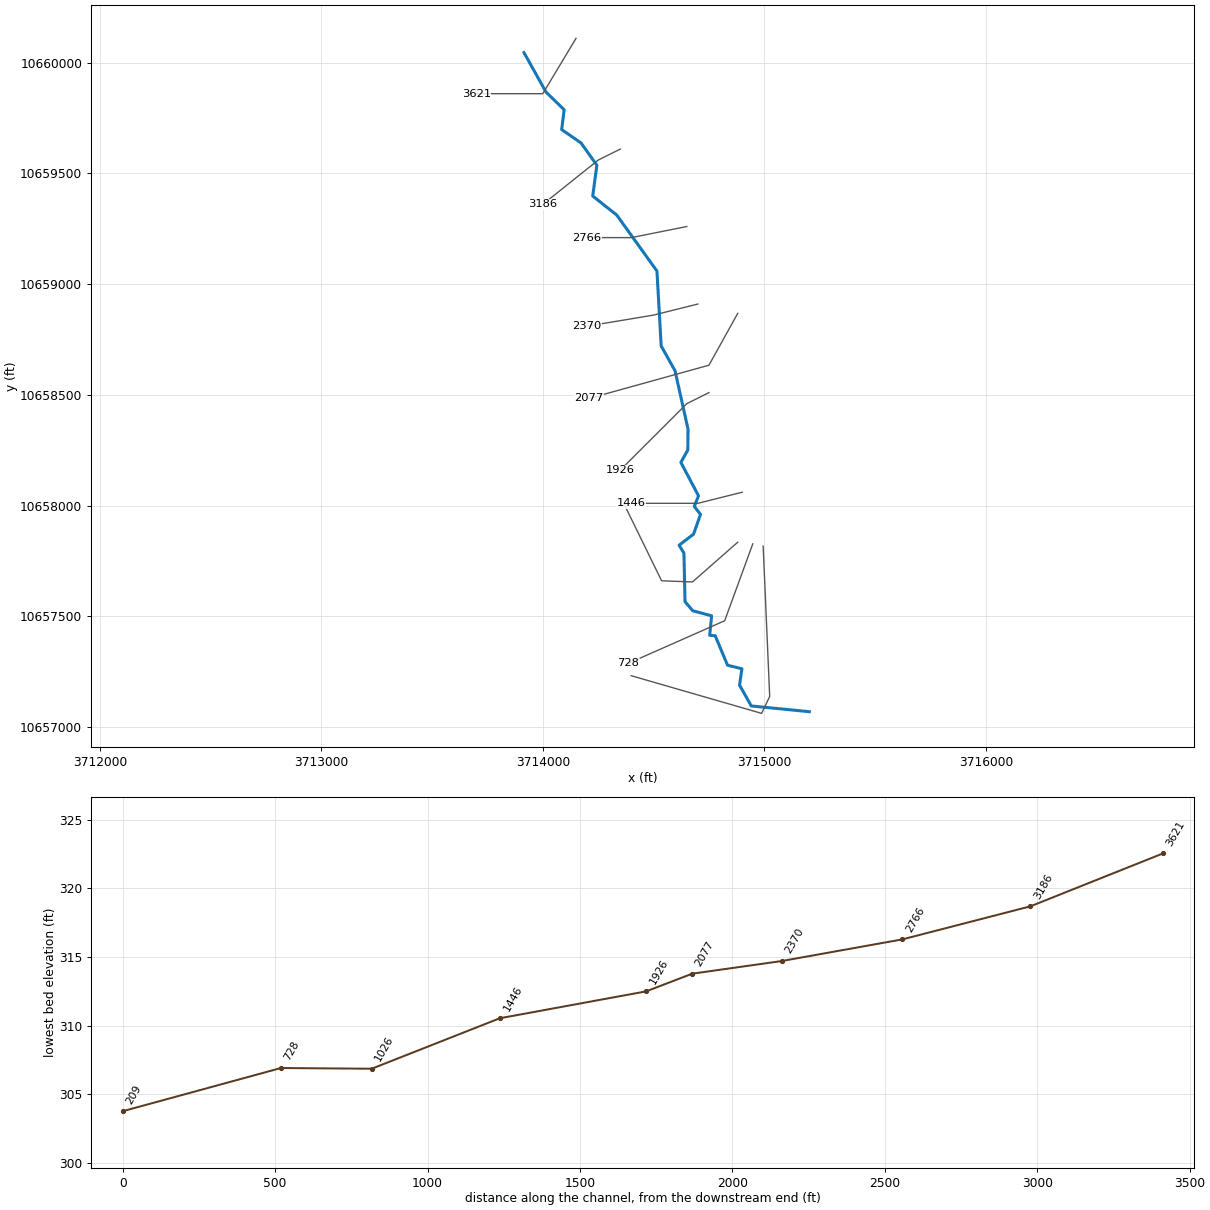
--- UNT 0480 IN LACR.prj (project) ---

Proj Title=UNT 0480 IN LACR Base Level Engineering
Current Plan=p01
Default Exp/Contr=0.3,0.1
English Units
Geom File=g01
Flow File=f01
Plan File=p01
BEGIN DESCRIPTION:
UNT 0480 IN LACR
END DESCRIPTION:

--- UNT 0480 IN LACR.p01 (plan) ---

Plan Title=Multiple Run
Short Identifier=Multiple
Geom File=g01
Flow File=f01
Subcritical Flow
K Sum by GR= 0
Std Step Tol= 0.01
Critical Tol= 0.01
Num of Std Step Trials= 20
Max Error Tol= 0.3
Flow Tol Ratio= 0.001
Split Flow NTrial= 30
Split Flow Tol= 0.02
Split Flow Ratio= 0.02
Log Output Level= 0
Friction Slope Method= 1
Unsteady Friction Slope Method= 2
Unsteady Bridges Friction Slope Method= 1
Parabolic Critical Depth
Global Vel Dist=  1 , 1 , 1
Global Log Level= 0
CheckData=True
Encroach Param= -1, 0, 0, 0
BEGIN DESCRIPTION:
Multiple Run
END DESCRIPTION:

--- UNT 0480 IN LACR.f01 (steady flow) ---

Flow Title=Multiple
Number of Profiles=7
Profile Names=10-year,25-year,50-year,1pct_min,100-year,1pct_plu,500-year
River Rch & RM= UNT 0480 IN LACR,Reach-1,3621
     411     545     654     578     782    1057    1119
River Rch & RM= UNT 0480 IN LACR,Reach-1,728
     605     821    1000     896    1212    1639    1784
Boundary for River Rch & Prof#=UNT 0480 IN LACR,Reach-1,1
Up Type=0
Dn Type=3
Dn Slope=0.005
Boundary for River Rch & Prof#=UNT 0480 IN LACR,Reach-1,2
Up Type=0
Dn Type=3
Dn Slope=0.005
Boundary for River Rch & Prof#=UNT 0480 IN LACR,Reach-1,3
Up Type=0
Dn Type=3
Dn Slope=0.005
Boundary for River Rch & Prof#=UNT 0480 IN LACR,Reach-1,4
Up Type=0
Dn Type=3
Dn Slope=0.005
Boundary for River Rch & Prof#=UNT 0480 IN LACR,Reach-1,5
Up Type=0
Dn Type=3
Dn Slope=0.005
Boundary for River Rch & Prof#=UNT 0480 IN LACR,Reach-1,6
Up Type=0
Dn Type=3
Dn Slope=0.005
Boundary for River Rch & Prof#=UNT 0480 IN LACR,Reach-1,7
Up Type=0
Dn Type=3
Dn Slope=0.005

--- UNT 0480 IN LACR.g01 (geometry) ---

Geom Title=Existing Conditions

River Reach=UNT 0480 IN LACR,Reach-1
Reach XY= 30
      3713914.65     10660045.99      3714014.50     10659867.00
      3714096.00     10659788.00      3714085.00     10659698.00
      3714172.00     10659638.00      3714243.75     10659537.00
      3714225.00     10659398.00      3714333.50     10659312.00
      3714515.00     10659059.00      3714534.00     10658721.00
      3714596.50     10658609.00      3714655.25     10658345.00
      3714654.25     10658251.00      3714623.00     10658195.00
      3714702.50     10658044.00      3714683.50     10657996.00
      3714711.50     10657960.00      3714680.25     10657871.00
      3714615.00     10657821.00      3714636.75     10657785.00
      3714641.75     10657566.00      3714676.50     10657525.00
      3714761.75     10657502.00      3714753.00     10657414.00
      3714778.00     10657412.00      3714833.50     10657279.00
      3714898.50     10657263.00      3714887.75     10657189.00
      3714940.75     10657095.00      3715202.75     10657069.00

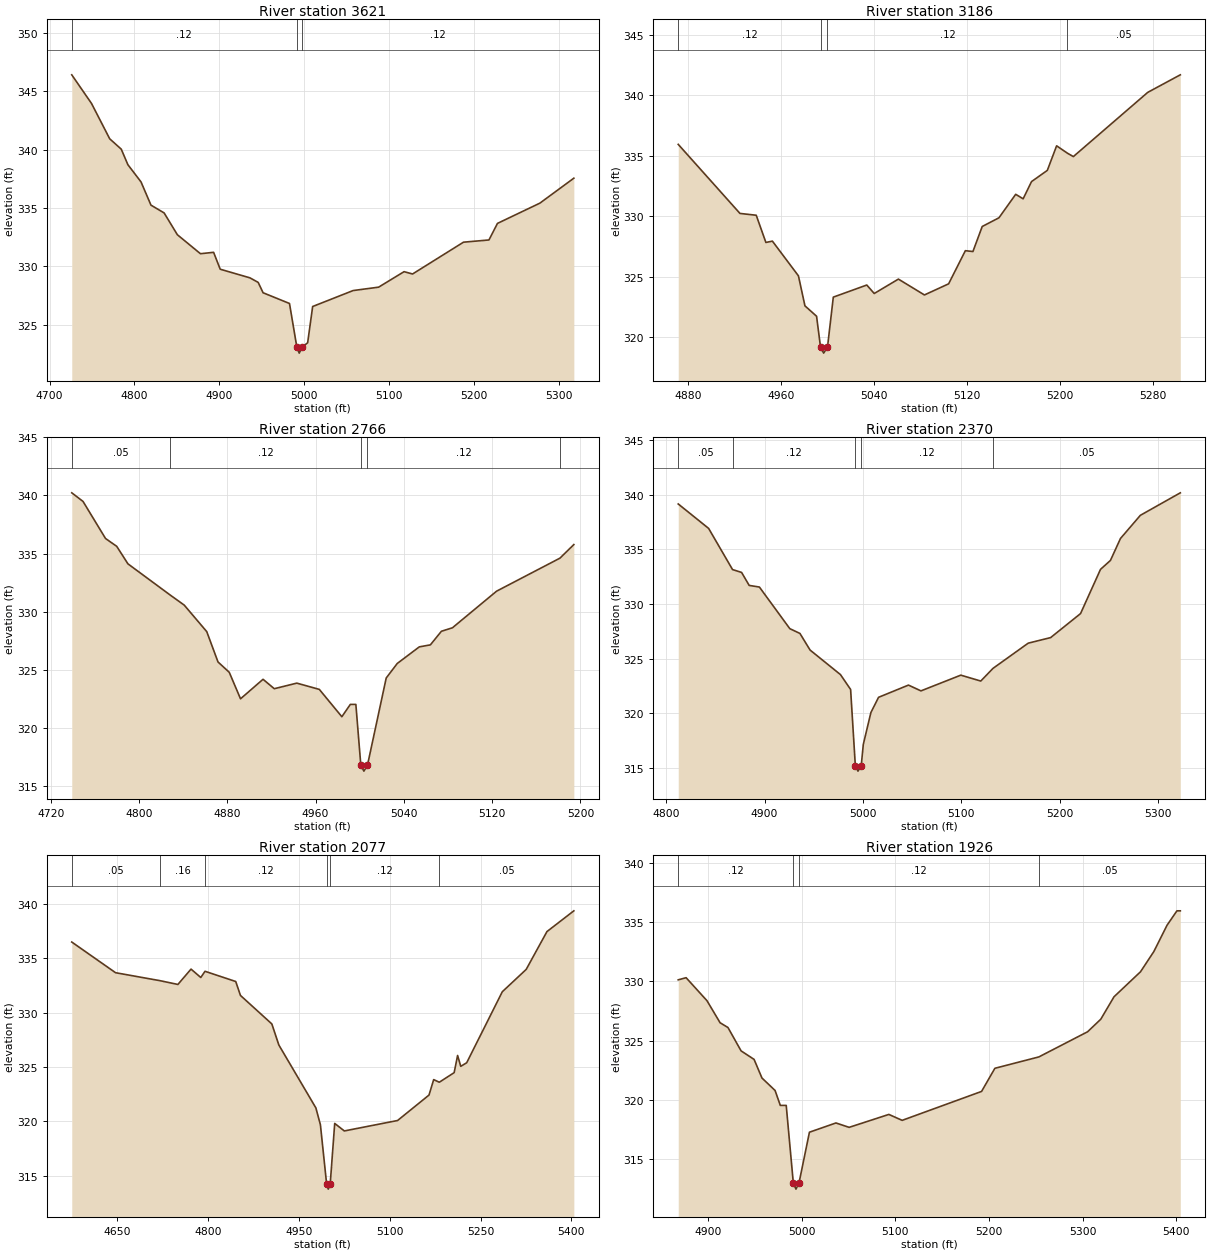
Type RM Length L Ch R = 1,3621,435,435,435
BEGIN DESCRIPTION:
UNT 0480 IN LACR 7.0
END DESCRIPTION:
XS GIS Cut Line= 3
      3714149.60     10660110.17      3713999.61     10659860.19
      3713699.64     10659860.19
#Sta/Elev= 30
  4726.1  346.43  4749.4  343.97  4770.8  340.94  4784.4  340.05  4792.2  338.72
  4807.7  337.24  4819.4  335.25  4834.9  334.58  4850.5  332.71  4877.7  331.08
  4893.2  331.20  4901.0  329.75  4936.0  329.01  4945.7  328.62  4951.5  327.73
  4982.6  326.81  4991.3  323.05  4994.1  322.55  4997.3  323.05  5004.0  323.44
  5009.9  326.55  5057.6  327.92  5087.6  328.21  5117.6  329.54  5127.6  329.34
  5187.6  332.07  5217.6  332.26  5227.6  333.68  5277.6  335.42  5317.6  337.56
#Mann=3,-1,0
  4726.1    0.12       0  4991.3    0.07       0  4997.3    0.12       0
Bank Sta=4991.3,4997.3
Exp/Cntr=0.3,0.1

Type RM Length L Ch R = 1,3186,420,420,420
BEGIN DESCRIPTION:
UNT 0480 IN LACR 6.0
END DESCRIPTION:
XS GIS Cut Line= 3
      3714349.59     10659610.18      3714249.61     10659560.19
      3713999.64     10659360.21
#Sta/Elev= 30
  4871.7  335.95  4924.8  330.24  4938.8  330.09  4947.1  327.84  4952.7  327.95
  4975.1  325.08  4980.7  322.60  4990.7  321.74  4994.1  319.19  4996.8  318.69
  5000.1  319.19  5005.1  323.32  5033.9  324.32  5040.3  323.62  5061.1  324.81
  5083.5  323.50  5104.3  324.42  5118.7  327.16  5125.2  327.09  5133.2  329.16
  5147.6  329.88  5162.0  331.82  5168.4  331.45  5175.6  332.87  5189.2  333.80
  5197.2  335.83  5206.5  335.22  5211.6  334.94  5275.6  340.25  5303.6  341.70
#Mann=4,-1,0
  4871.7    0.12       0  4994.1    0.07       0  5000.1    0.12       0
  5206.5    0.05       0
Bank Sta=4994.1,5000.1
Exp/Cntr=0.3,0.1

Type RM Length L Ch R = 1,2766,396,396,396
BEGIN DESCRIPTION:
UNT 0480 IN LACR 5.0
END DESCRIPTION:
XS GIS Cut Line= 3
      3714649.57     10659260.18      3714399.61     10659210.19
      3714199.62     10659210.19
#Sta/Elev= 30
  4739.1  340.22  4749.3  339.48  4769.7  336.29  4779.8  335.62  4790.0  334.11
  4828.1  331.44  4841.0  330.56  4861.4  328.28  4871.6  325.67  4881.8  324.78
  4892.0  322.50  4912.4  324.18  4922.6  323.37  4943.0  323.85  4963.4  323.31
  4983.8  320.96  4991.5  322.02  4996.5  322.02  5001.0  316.78  5003.8  316.28
  5007.0  316.78  5024.0  324.29  5034.0  325.54  5054.0  326.97  5064.0  327.14
  5074.0  328.31  5084.0  328.61  5124.0  331.76  5181.4  334.60  5194.0  335.77
#Mann=5,-1,0
  4739.1    0.05       0  4828.1    0.12       0  5001.0    0.07       0
  5007.0    0.12       0  5181.4    0.05       0
Bank Sta=5001,5007
Exp/Cntr=0.3,0.1

Type RM Length L Ch R = 1,2370,293,293,293
BEGIN DESCRIPTION:
UNT 0480 IN LACR 4.0
END DESCRIPTION:
XS GIS Cut Line= 3
      3714699.60     10658910.19      3714499.61     10658860.19
      3714199.59     10658810.19
#Sta/Elev= 30
  4812.2  339.17  4843.1  336.93  4867.4  333.16  4876.6  332.90  4884.3  331.71
  4894.7  331.56  4925.6  327.75  4935.9  327.31  4946.2  325.79  4977.1  323.54
  4987.4  322.18  4992.2  315.20  4994.9  314.70  4998.2  315.20  5000.3  317.15
  5008.0  320.06  5015.8  321.46  5046.2  322.58  5058.9  322.05  5099.4  323.49
  5119.7  322.95  5132.1  324.11  5167.9  326.42  5190.7  326.93  5221.1  329.13
  5241.4  333.18  5251.5  334.00  5261.7  336.01  5281.9  338.13  5322.5  340.19
#Mann=5,-1,0
  4812.2    0.05       0  4867.4    0.12       0  4992.2    0.07       0
  4998.2    0.12       0  5132.1    0.05       0
Bank Sta=4992.2,4998.2
Exp/Cntr=0.3,0.1

Type RM Length L Ch R = 1,2077,151,151,151
BEGIN DESCRIPTION:
Mapping XS a8f397c1
END DESCRIPTION:
XS GIS Cut Line= 3
      3714879.76     10658868.23      3714749.54     10658633.83
      3714209.15     10658484.08
#Sta/Elev= 30
  4575.2  336.50  4647.5  333.68  4720.6  332.95  4750.4  332.60  4772.1  334.01
  4788.2  333.24  4795.2  333.81  4845.9  332.87  4853.7  331.59  4905.5  328.97
  4917.1  327.03  4978.2  321.25  4985.7  319.70  4995.9  314.28  4998.7  313.78
  5001.9  314.28  5009.3  319.82  5025.2  319.13  5113.1  320.09  5165.0  322.43
  5172.7  323.85  5182.0  323.61  5206.5  324.49  5212.2  326.07  5217.4  325.07
  5227.2  325.40  5286.0  331.93  5325.4  333.98  5359.7  337.46  5404.1  339.37
#Mann=6,-1,0
  4575.2    0.05       0  4720.6    0.16       0  4795.2    0.12       0
  4995.9    0.07       0  5001.9    0.12       0  5182.0    0.05       0
Bank Sta=4995.9,5001.9
Exp/Cntr=0.3,0.1

Type RM Length L Ch R = 1,1926,480,480,480
BEGIN DESCRIPTION:
UNT 0480 IN LACR 3.0
END DESCRIPTION:
XS GIS Cut Line= 3
      3714749.60     10658510.18      3714649.61     10658460.19
      3714349.58     10658160.16
#Sta/Elev= 30
  4868.1  330.14  4876.5  330.32  4898.8  328.38  4912.8  326.52  4921.2  326.12
  4935.2  324.15  4949.1  323.43  4957.5  321.86  4971.5  320.81  4977.1  319.55
  4983.4  319.55  4991.0  312.99  4993.8  312.49  4997.0  312.99  5008.2  317.29
  5036.5  318.07  5050.6  317.70  5093.0  318.79  5107.2  318.29  5192.0  320.73
  5206.2  322.68  5253.2  323.64  5305.2  325.76  5319.3  326.82  5333.4  328.71
  5361.7  330.82  5375.9  332.52  5390.0  334.74  5400.6  335.96  5404.2  335.96
#Mann=4,-1,0
  4868.1    0.12       0  4991.0    0.07       0  4997.0    0.12       0
  5253.2    0.05       0
Bank Sta=4991,4997
Exp/Cntr=0.3,0.1

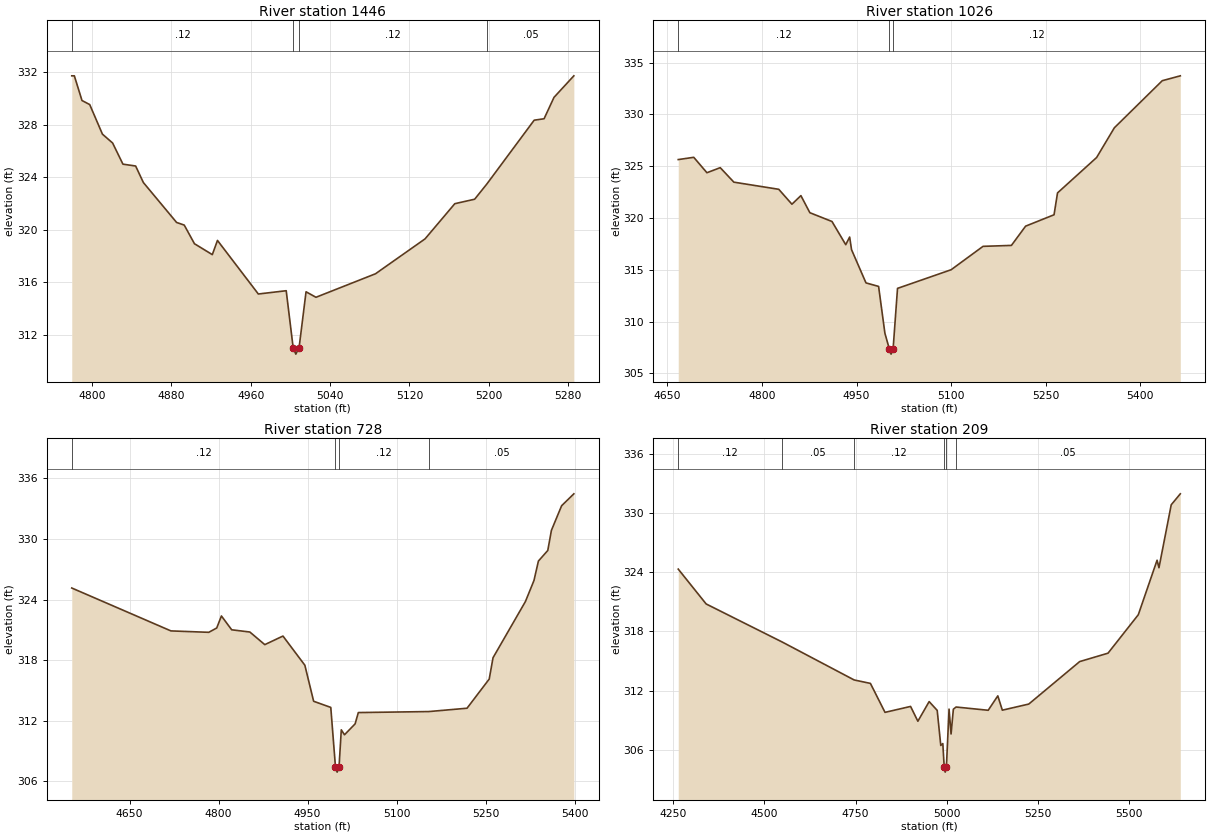
Type RM Length L Ch R = 1,1446,420,420,420
BEGIN DESCRIPTION:
UNT 0480 IN LACR 2.0
END DESCRIPTION:
XS GIS Cut Line= 3
      3714899.62     10658060.19      3714699.61     10658010.19
      3714399.58     10658010.19
#Sta/Elev= 30
  4779.6  331.73  4782.2  331.73  4789.9  329.85  4797.7  329.54  4810.5  327.29
  4820.8  326.61  4831.2  325.00  4844.0  324.86  4851.8  323.60  4885.3  320.56
  4893.0  320.36  4903.3  318.94  4921.3  318.11  4926.5  319.19  4967.7  315.11
  4995.8  315.36  5002.8  311.03  5005.5  310.53  5008.8  311.03  5015.8  315.28
  5025.8  314.86  5085.8  316.65  5135.8  319.31  5165.8  321.99  5185.8  322.33
  5198.2  323.50  5245.8  328.35  5255.8  328.46  5265.8  330.09  5285.8  331.73
#Mann=4,-1,0
  4779.6    0.12       0  5002.8    0.07       0  5008.8    0.12       0
  5198.2    0.05       0
Bank Sta=5002.8,5008.8
Exp/Cntr=0.3,0.1

Type RM Length L Ch R = 1,1026,298,298,298
BEGIN DESCRIPTION:
Mapping XS 48e88ea6
END DESCRIPTION:
XS GIS Cut Line= 4
      3714879.60     10657834.54      3714675.31     10657655.01
      3714535.98     10657660.21      3714367.06     10658005.85
#Sta/Elev= 30
  4667.2  325.64  4691.8  325.86  4712.7  324.37  4733.8  324.86  4755.4  323.46
  4826.6  322.77  4847.5  321.33  4861.7  322.16  4875.9  320.51  4911.0  319.66
  4932.8  317.42  4939.0  318.16  4942.0  316.94  4964.9  313.73  4984.9  313.39
  4994.9  308.87  5001.9  307.35  5004.7  306.85  5007.9  307.35  5014.9  313.20
  5099.9  315.00  5150.5  317.26  5195.5  317.35  5218.0  319.21  5263.1  320.31
  5268.6  322.42  5330.6  325.84  5358.7  328.71  5434.7  333.26  5463.3  333.73
#Mann=3,-1,0
  4667.2    0.12       0  5001.9    0.07       0  5007.9    0.12       0
Bank Sta=5001.9,5007.9
Exp/Cntr=0.3,0.1

Type RM Length L Ch R = 1,728,519,519,519
BEGIN DESCRIPTION:
Mapping XS 27b6cdbc
END DESCRIPTION:
XS GIS Cut Line= 3
      3714947.49     10657827.12      3714820.75     10657479.87
      3714385.01     10657287.18
#Sta/Elev= 30
  4552.6  325.14  4719.7  320.89  4783.5  320.75  4796.9  321.18  4804.8  322.37
  4822.1  321.00  4852.7  320.78  4877.9  319.53  4908.5  320.38  4945.4  317.49
  4960.2  313.92  4989.1  313.31  4997.0  307.40  4999.8  306.90  5003.0  307.40
  5006.8  311.09  5012.2  310.60  5030.1  311.68  5035.5  312.80  5154.4  312.90
  5218.7  313.23  5256.1  316.12  5262.5  318.23  5317.1  323.80  5331.5  325.88
  5339.0  327.81  5354.8  328.86  5360.9  330.85  5378.1  333.29  5398.7  334.47
#Mann=4,-1,0
  4552.6    0.12       0  4997.0    0.07       0  5003.0    0.12       0
  5154.4    0.05       0
Bank Sta=4997,5003
Exp/Cntr=0.3,0.1

Type RM Length L Ch R = 1,209,0,0,0
BEGIN DESCRIPTION:
UNT 0480 IN LACR 1.0
END DESCRIPTION:
XS GIS Cut Line= 4
      3714994.36     10657816.67      3715023.87     10657137.86
      3714987.41     10657061.47      3714398.91     10657231.60
#Sta/Elev= 30
  4263.7  324.30  4340.3  320.77  4549.3  316.91  4746.0  313.08  4790.7  312.73
  4830.7  309.80  4900.8  310.40  4920.8  308.90  4951.7  310.89  4973.8  310.00
  4983.6  306.45  4989.2  306.64  4993.0  304.25  4995.7  303.75  4999.0  304.25
  5006.3  310.13  5011.8  307.61  5018.1  310.12  5025.6  310.34  5113.6  310.01
  5140.0  311.47  5152.4  310.02  5224.9  310.64  5364.5  314.94  5442.2  315.79
  5525.2  319.68  5576.7  325.20  5581.9  324.44  5615.5  330.81  5640.4  331.92
#Mann=6,-1,0
  4263.7    0.12       0  4549.3    0.05       0  4746.0    0.12       0
  4993.0    0.07       0  4999.0    0.12       0  5025.6    0.05       0
Bank Sta=4993,4999
Exp/Cntr=0.3,0.1

Chan Stop Cuts=-1