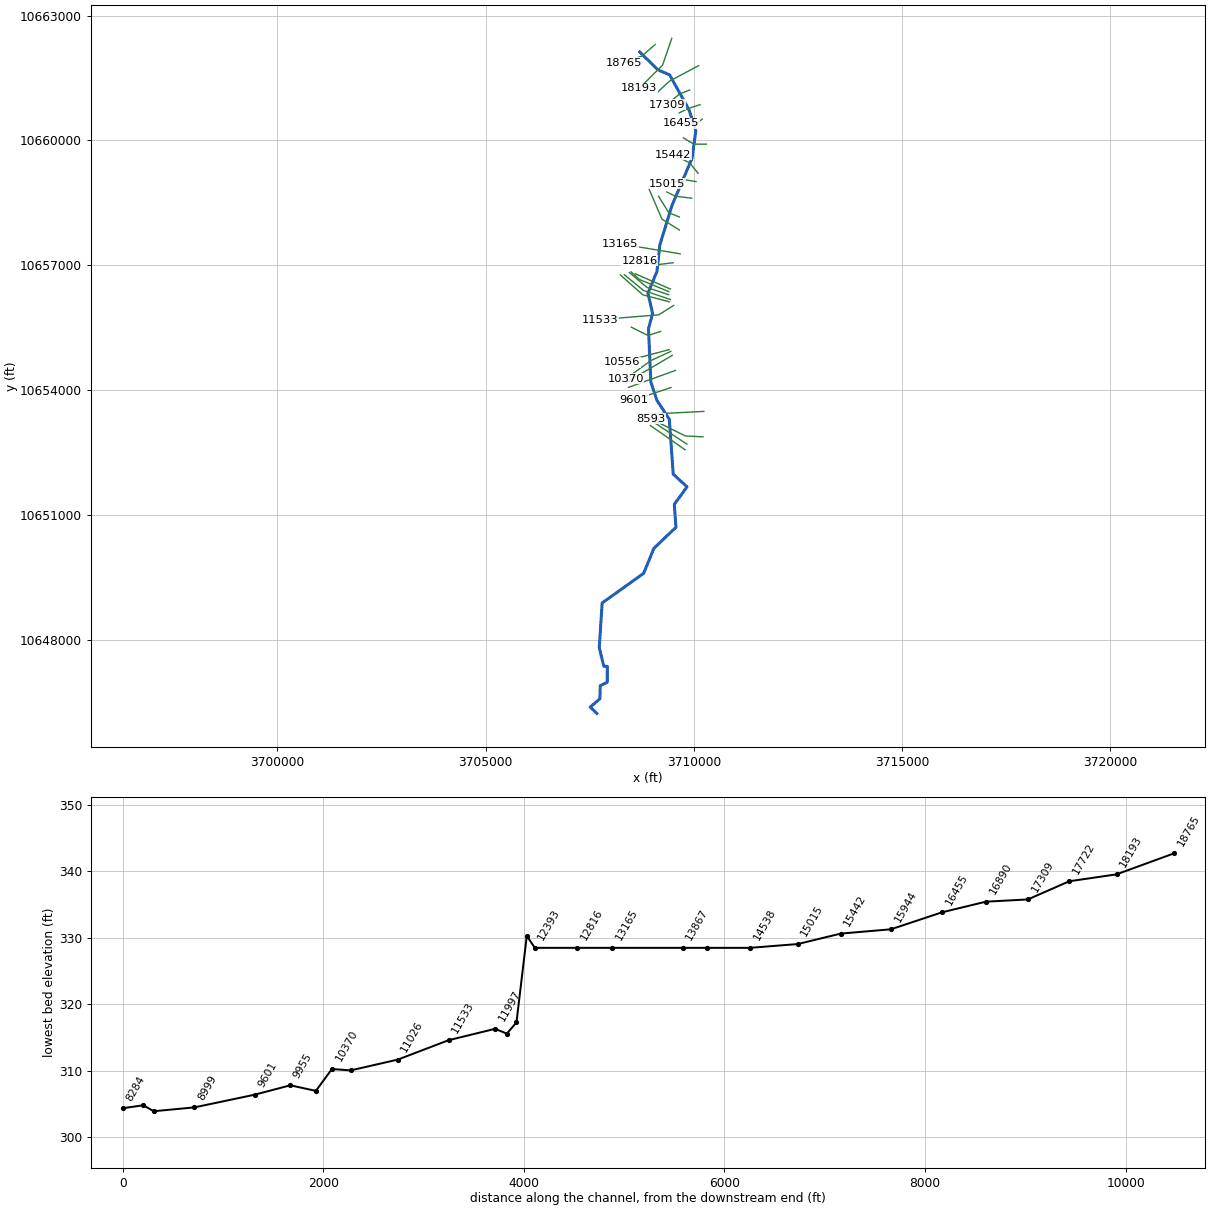
--- UNT 0481 IN LACR.prj (project) ---

Proj Title=UNT 0481 IN LACR Base Level Engineering
Current Plan=p01
Default Exp/Contr=0.3,0.1
English Units
Geom File=g01
Flow File=f01
Plan File=p01
BEGIN DESCRIPTION:
UNT 0481 IN LACR
END DESCRIPTION:

--- UNT 0481 IN LACR.p01 (plan) ---

Plan Title=Multiple Run
Short Identifier=Multiple
Geom File=g01
Flow File=f01
Subcritical Flow
K Sum by GR= 0
Std Step Tol= 0.01
Critical Tol= 0.01
Num of Std Step Trials= 20
Max Error Tol= 0.3
Flow Tol Ratio= 0.001
Split Flow NTrial= 30
Split Flow Tol= 0.02
Split Flow Ratio= 0.02
Log Output Level= 0
Friction Slope Method= 1
Unsteady Friction Slope Method= 2
Unsteady Bridges Friction Slope Method= 1
Parabolic Critical Depth
Global Vel Dist=  1 , 1 , 1
Global Log Level= 0
CheckData=True
Encroach Param= -1, 0, 0, 0
BEGIN DESCRIPTION:
Multiple Run
END DESCRIPTION:

--- UNT 0481 IN LACR.f01 (steady flow) ---

Flow Title=Multiple
Number of Profiles=7
Profile Names=10-year,25-year,50-year,1pct_min,100-year,1pct_plu,500-year
River Rch & RM= UNT 0481 IN LACR,Reach-1,18765
     580     783     950     847    1145    1549    1671
River Rch & RM= UNT 0481 IN LACR,Reach-1,17722
     633     855    1036     923    1248    1688    1817
River Rch & RM= UNT 0481 IN LACR,Reach-1,13165
     751    1024    1250    1120    1515    2048    2232
River Rch & RM= UNT 0481 IN LACR,Reach-1,11533
     961    1322    1623    1460    1975    2670    2938
River Rch & RM= UNT 0481 IN LACR,Reach-1,8129
    1005    1385    1702    1533    2074    2804    3091
River Rch & RM= UNT 0481 IN LACR,Reach-1,5041
    1073    1480    1820    1640    2218    3000    3310
River Rch & RM= UNT 0481 IN LACR,Reach-1,2778
    1236    1716    2119    1917    2592    3506    3897
River Rch & RM= UNT 0481 IN LACR,Reach-1,2128
    1365    1905    2363    2145    2901    3923    4394
Boundary for River Rch & Prof#=UNT 0481 IN LACR,Reach-1,1
Up Type=0
Dn Type=3
Dn Slope=0.005
Boundary for River Rch & Prof#=UNT 0481 IN LACR,Reach-1,2
Up Type=0
Dn Type=3
Dn Slope=0.005
Boundary for River Rch & Prof#=UNT 0481 IN LACR,Reach-1,3
Up Type=0
Dn Type=3
Dn Slope=0.005
Boundary for River Rch & Prof#=UNT 0481 IN LACR,Reach-1,4
Up Type=0
Dn Type=3
Dn Slope=0.005
Boundary for River Rch & Prof#=UNT 0481 IN LACR,Reach-1,5
Up Type=0
Dn Type=3
Dn Slope=0.005
Boundary for River Rch & Prof#=UNT 0481 IN LACR,Reach-1,6
Up Type=0
Dn Type=3
Dn Slope=0.005
Boundary for River Rch & Prof#=UNT 0481 IN LACR,Reach-1,7
Up Type=0
Dn Type=3
Dn Slope=0.005

--- UNT 0481 IN LACR.g01 (geometry) ---

Geom Title=Existing Conditions

River Reach=UNT 0481 IN LACR,Reach-1
Reach XY= 30
      3708699.61     10662124.00      3709133.25     10661698.00
      3709419.75     10661571.00      3709881.75     10660737.00
      3710046.25     10660231.00      3709957.00     10659572.00
      3709476.75     10658445.00      3709182.75     10657491.00
      3709113.25     10656850.00      3708896.25     10656330.00
      3709009.50     10655843.00      3708910.00     10655475.00
      3708967.25     10654192.00      3709116.00     10653750.00
      3709410.50     10653299.00      3709503.25     10651981.00
      3709835.25     10651676.00      3709530.75     10651257.00
      3709569.00     10650703.00      3709039.00     10650198.00
      3708796.25     10649600.00      3707798.00     10648886.00
      3707728.25     10647814.00      3707837.50     10647366.00
      3707921.00     10647363.00      3707920.25     10646979.00
      3707752.00     10646900.00      3707743.50     10646583.00
      3707511.25     10646385.00      3707669.75     10646233.00

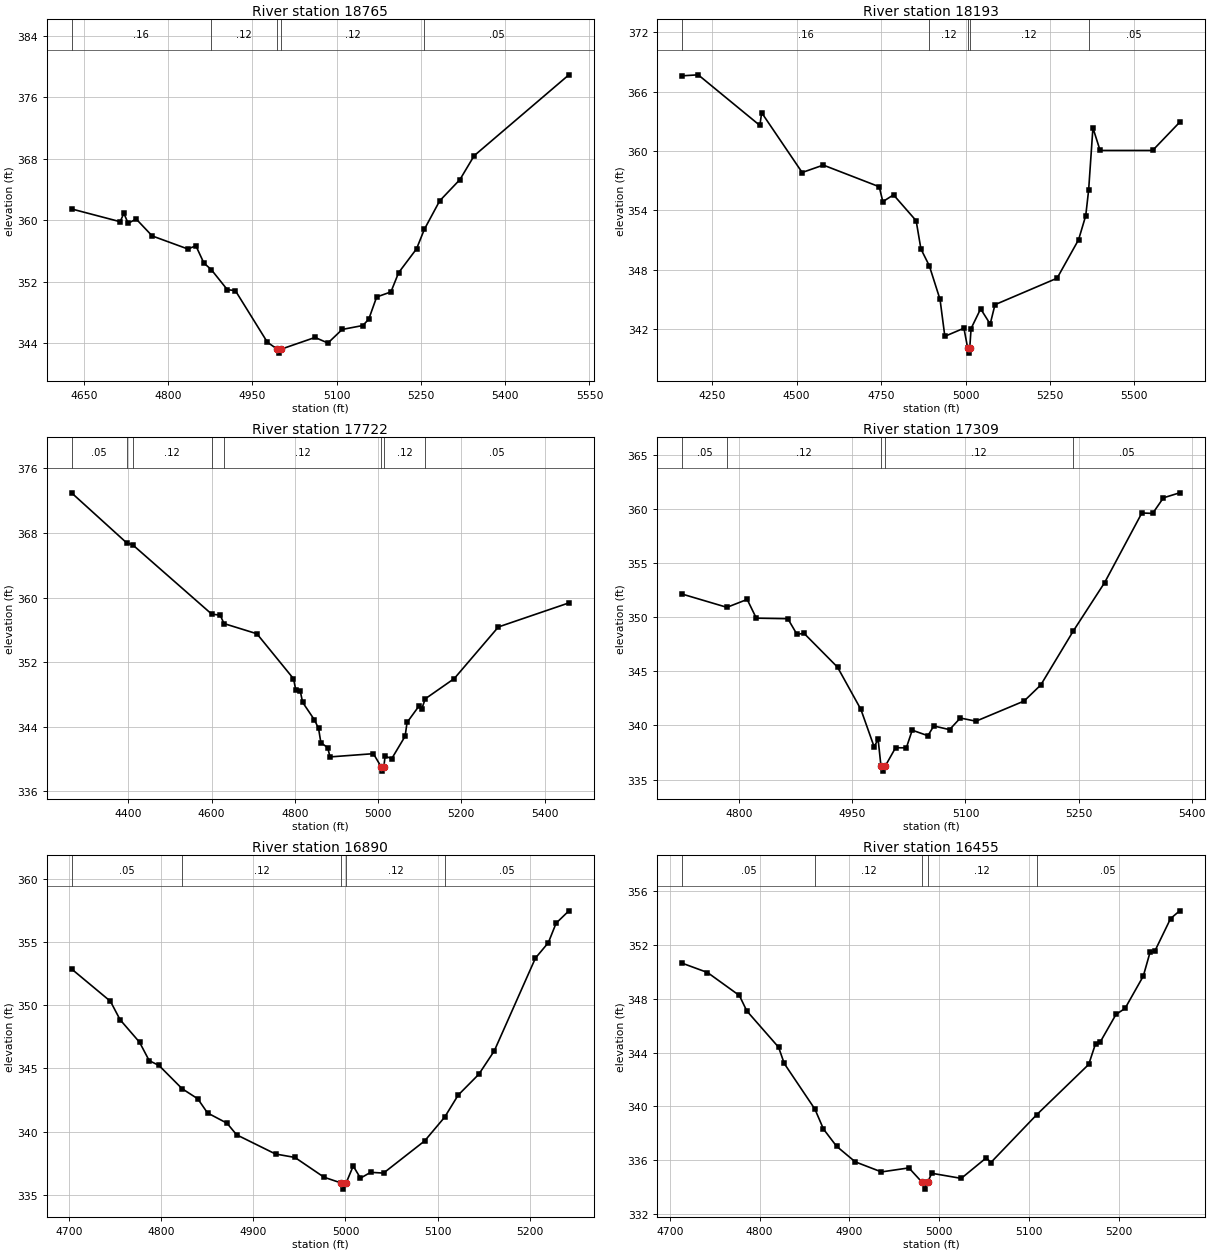
Type RM Length L Ch R = 1,18765,572,572,572
BEGIN DESCRIPTION:
UNT 0481 IN LACR 39.0
END DESCRIPTION:
XS GIS Cut Line= 3
      3709069.19     10662302.56      3708747.99     10662024.77
      3708314.30     10661868.64
#Sta/Elev= 30
  4627.8  361.45  4714.3  359.79  4721.0  360.88  4728.6  359.58  4742.9  360.14
  4771.4  357.94  4835.0  356.24  4849.2  356.66  4863.5  354.41  4876.5  353.57
  4905.2  350.95  4919.5  350.83  4976.5  344.12  4994.4  343.20  4997.2  342.70
  5000.4  343.20  5061.4  344.74  5084.3  344.01  5109.7  345.78  5146.4  346.29
  5157.0  347.11  5171.1  350.00  5196.5  350.66  5210.2  353.16  5242.1  356.26
  5256.1  358.81  5283.3  362.50  5319.4  365.27  5344.7  368.37  5513.4  378.89
#Mann=5,-1,0
  4627.8    0.16       0  4876.5    0.12       0  4994.4    0.07       0
  5000.4    0.12       0  5256.1    0.05       0
Bank Sta=4994.4,5000.4
Exp/Cntr=0.3,0.1

Type RM Length L Ch R = 1,18193,471,471,471
BEGIN DESCRIPTION:
UNT 0481 IN LACR 38.0
END DESCRIPTION:
XS GIS Cut Line= 3
      3709469.20     10662451.92      3709249.61     10661810.19
      3708687.93     10661248.79
#Sta/Elev= 30
  4161.5  367.60  4208.7  367.70  4391.2  362.58  4396.5  363.87  4516.4  357.82
  4579.0  358.57  4744.6  356.38  4755.2  354.87  4786.9  355.56  4853.9  352.94
  4868.0  350.09  4892.9  348.38  4924.6  344.98  4938.8  341.25  4995.3  342.07
  5006.5  340.05  5009.2  339.55  5012.5  340.05  5016.5  342.04  5044.8  344.03
  5073.1  342.49  5087.2  344.45  5271.1  347.13  5334.7  351.02  5355.9  353.45
  5364.5  356.04  5377.2  362.34  5398.4  360.05  5553.9  360.05  5633.9  362.90
#Mann=5,-1,0
  4161.5    0.16       0  4892.9    0.12       0  5006.5    0.07       0
  5012.5    0.12       0  5364.5    0.05       0
Bank Sta=5006.5,5012.5
Exp/Cntr=0.3,0.1

Type RM Length L Ch R = 1,17722,413,413,413
BEGIN DESCRIPTION:
UNT 0481 IN LACR 37.0
END DESCRIPTION:
XS GIS Cut Line= 3
      3710115.04     10661795.69      3709411.01     10661421.59
      3709120.26     10661149.87
#Sta/Elev= 30
  4263.4  372.97  4396.0  366.77  4410.2  366.54  4600.5  357.94  4620.6  357.83
  4629.8  356.78  4708.8  355.52  4796.7  349.96  4802.3  348.59  4813.0  348.44
  4818.7  347.03  4847.1  344.86  4857.0  343.80  4862.6  342.03  4878.9  341.42
  4884.6  340.27  4988.8  340.67  5007.8  339.01  5010.6  338.51  5013.8  339.01
  5016.9  340.37  5032.8  340.05  5065.0  342.83  5069.7  344.54  5098.1  346.55
  5104.9  346.19  5113.3  347.46  5183.1  349.97  5289.1  356.36  5458.6  359.34
#Mann=8,-1,0
  4263.4    0.05       0  4396.0    0.16       0  4410.2    0.12       0
  4600.5    0.16       0  4629.8    0.12       0  5007.8    0.07       0
  5013.8    0.12       0  5113.3    0.05       0
Bank Sta=5007.8,5013.8
Exp/Cntr=0.3,0.1

Type RM Length L Ch R = 1,17309,419,419,419
BEGIN DESCRIPTION:
UNT 0481 IN LACR 36.0
END DESCRIPTION:
XS GIS Cut Line= 3
      3709899.57     10661210.17      3709649.61     10661110.19
      3709349.63     10660860.20
#Sta/Elev= 30
  4724.4  352.12  4783.6  350.90  4810.5  351.63  4822.6  349.90  4864.4  349.85
  4876.5  348.41  4885.9  348.50  4930.3  345.38  4961.3  341.48  4978.8  338.04
  4984.2  338.70  4987.9  336.28  4990.7  335.78  4993.9  336.28  5007.3  337.94
  5021.6  337.93  5029.4  339.56  5050.2  339.05  5058.0  339.95  5078.9  339.61
  5093.2  340.68  5114.0  340.39  5177.8  342.25  5199.9  343.73  5243.0  348.71
  5284.5  353.17  5334.0  359.61  5348.3  359.57  5362.6  361.01  5384.1  361.47
#Mann=5,-1,0
  4724.4    0.05       0  4783.6    0.12       0  4987.9    0.07       0
  4993.9    0.12       0  5243.0    0.05       0
Bank Sta=4987.9,4993.9
Exp/Cntr=0.3,0.1

Type RM Length L Ch R = 1,16890,435,435,435
BEGIN DESCRIPTION:
UNT 0481 IN LACR 35.0
END DESCRIPTION:
XS GIS Cut Line= 3
      3710149.61     10660860.19      3709849.61     10660760.19
      3709649.64     10660660.21
#Sta/Elev= 30
  4702.7  352.87  4744.9  350.31  4755.4  348.85  4776.5  347.07  4787.0  345.61
  4797.6  345.23  4822.7  343.39  4839.7  342.59  4850.3  341.47  4871.4  340.66
  4881.9  339.74  4924.1  338.22  4945.1  337.95  4976.8  336.38  4994.8  335.94
  4997.6  335.44  5000.8  335.94  5008.4  337.27  5016.3  336.31  5027.3  336.77
  5041.3  336.71  5086.0  339.26  5107.7  341.14  5122.3  342.88  5144.7  344.53
  5161.5  346.38  5206.2  353.73  5220.2  354.95  5228.6  356.49  5242.5  357.47
#Mann=5,-1,0
  4702.7    0.05       0  4822.7    0.12       0  4994.8    0.07       0
  5000.8    0.12       0  5107.7    0.05       0
Bank Sta=4994.8,5000.8
Exp/Cntr=0.3,0.1

Type RM Length L Ch R = 1,16455,511,511,511
BEGIN DESCRIPTION:
UNT 0481 IN LACR 34.0
END DESCRIPTION:
XS GIS Cut Line= 3
      3710199.62     10660510.19      3709999.61     10660360.19
      3709699.66     10660410.18
#Sta/Elev= 30
  4713.8  350.66  4741.9  349.97  4777.4  348.26  4785.7  347.11  4821.1  344.41
  4827.4  343.20  4861.6  339.80  4871.1  338.32  4885.7  337.04  4906.5  335.88
  4935.7  335.13  4966.3  335.43  4981.1  334.35  4983.8  333.85  4987.1  334.35
  4991.7  335.03  5024.6  334.65  5052.5  336.18  5057.6  335.83  5108.7  339.39
  5166.6  343.13  5174.2  344.67  5179.2  344.77  5197.0  346.85  5207.1  347.30
  5227.4  349.70  5235.0  351.49  5240.1  351.54  5257.8  353.98  5267.9  354.56
#Mann=5,-1,0
  4713.8    0.05       0  4861.6    0.12       0  4981.1    0.07       0
  4987.1    0.12       0  5108.7    0.05       0
Bank Sta=4981.1,4987.1
Exp/Cntr=0.3,0.1

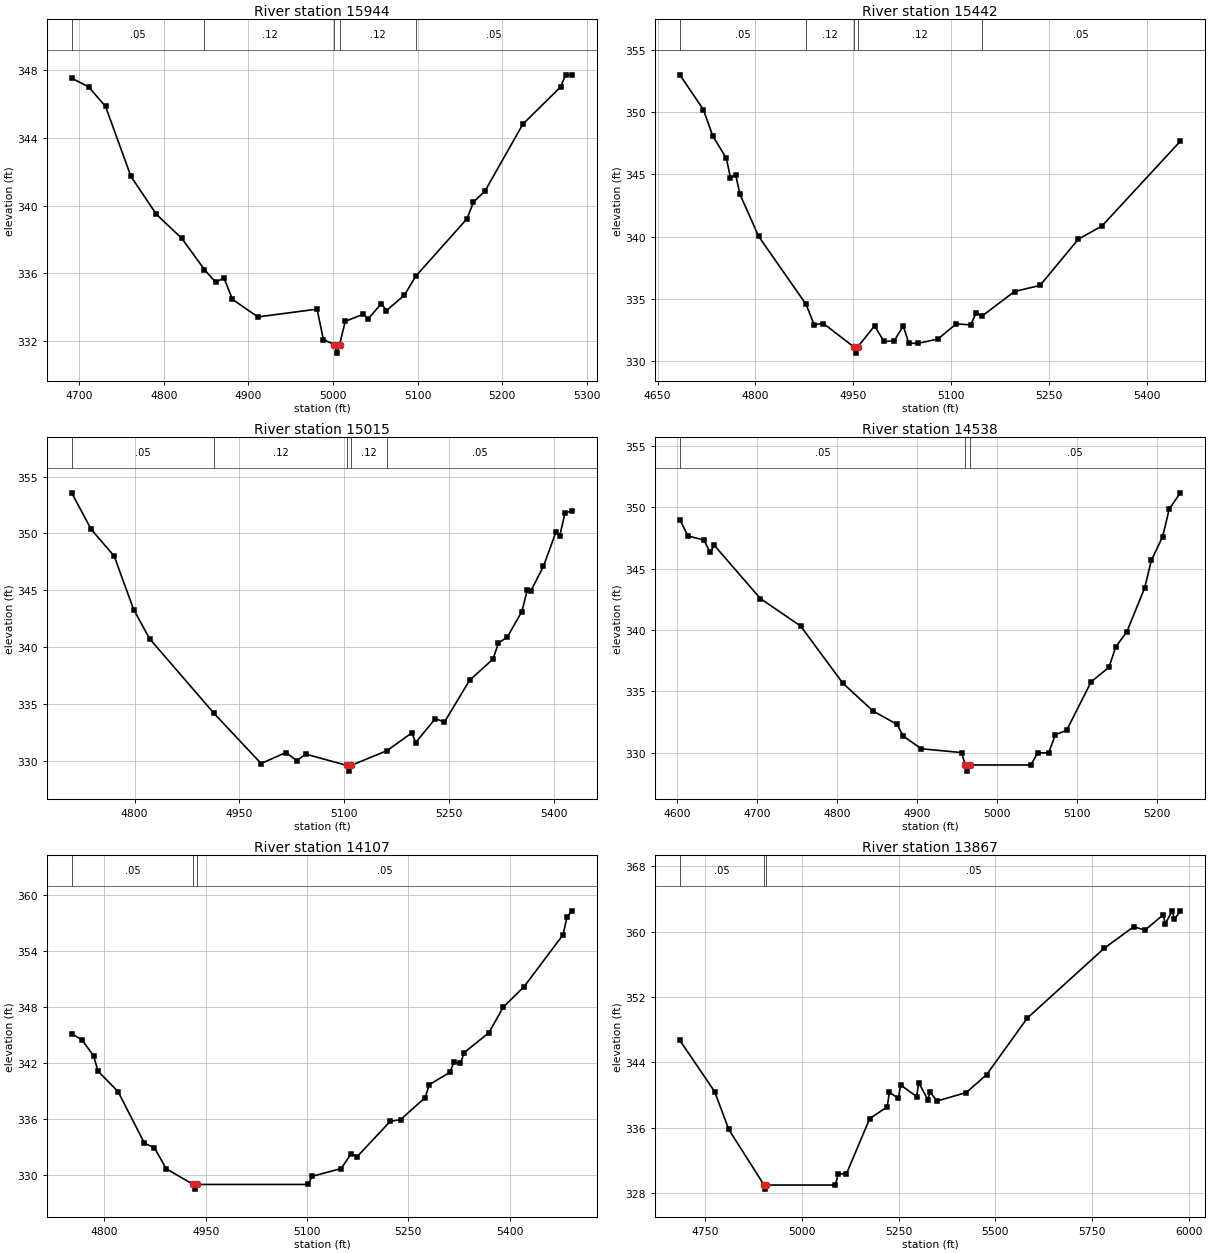
Type RM Length L Ch R = 1,15944,502,502,502
BEGIN DESCRIPTION:
UNT 0481 IN LACR 33.0
END DESCRIPTION:
XS GIS Cut Line= 3
      3710299.62     10659910.19      3709999.61     10659910.19
      3709749.58     10660060.21
#Sta/Elev= 30
  4691.1  347.54  4711.1  347.03  4731.1  345.87  4761.1  341.74  4791.1  339.50
  4821.1  338.08  4848.0  336.23  4861.1  335.48  4871.1  335.73  4881.1  334.47
  4911.1  333.43  4981.1  333.89  4988.6  332.09  5001.7  331.79  5004.5  331.29
  5007.7  331.79  5014.4  333.17  5035.8  333.59  5041.6  333.32  5057.2  334.22
  5063.0  333.80  5084.4  334.72  5097.8  335.84  5158.3  339.23  5166.0  340.22
  5179.6  340.87  5224.4  344.83  5269.1  347.03  5274.9  347.74  5282.7  347.73
#Mann=5,-1,0
  4691.1    0.05       0  4848.0    0.12       0  5001.7    0.07       0
  5007.7    0.12       0  5097.8    0.05       0
Bank Sta=5001.7,5007.7
Exp/Cntr=0.3,0.1

Type RM Length L Ch R = 1,15442,427,427,427
BEGIN DESCRIPTION:
UNT 0481 IN LACR 32.0
END DESCRIPTION:
XS GIS Cut Line= 3
      3710099.60     10659210.21      3709899.61     10659460.19
      3709499.65     10659660.17
#Sta/Elev= 30
  4684.1  353.00  4720.1  350.21  4734.5  348.10  4755.3  346.30  4761.7  344.75
  4769.7  344.95  4776.1  343.42  4804.9  340.02  4877.7  334.55  4889.8  332.93
  4904.2  333.02  4950.8  331.14  4953.6  330.64  4956.8  331.14  4982.6  332.83
  4997.0  331.58  5012.6  331.62  5026.6  332.83  5035.0  331.43  5049.0  331.43
  5079.7  331.77  5107.7  332.99  5130.0  332.91  5138.4  333.89  5147.4  333.62
  5197.1  335.59  5236.2  336.08  5294.9  339.79  5331.3  340.86  5451.4  347.67
#Mann=5,-1,0
  4684.1    0.05       0  4877.7    0.12       0  4950.8    0.07       0
  4956.8    0.12       0  5147.4    0.05       0
Bank Sta=4950.8,4956.8
Exp/Cntr=0.3,0.1

Type RM Length L Ch R = 1,15015,477,477,477
BEGIN DESCRIPTION:
UNT 0481 IN LACR 31.0
END DESCRIPTION:
XS GIS Cut Line= 3
      3710049.57     10659010.20      3709749.61     10659060.19
      3709349.62     10658960.19
#Sta/Elev= 30
  4710.1  353.58  4737.9  350.37  4770.9  348.01  4798.8  343.30  4821.6  340.73
  4913.9  334.15  4981.2  329.74  5016.8  330.71  5032.2  329.99  5045.1  330.57
  5104.0  329.57  5106.7  329.07  5110.0  329.57  5161.2  330.87  5197.2  332.45
  5202.3  331.58  5230.7  333.70  5243.5  333.38  5279.6  337.07  5313.1  338.94
  5320.9  340.34  5333.7  340.90  5354.4  343.12  5362.1  345.00  5367.2  344.94
  5385.3  347.10  5403.3  350.15  5408.5  349.75  5416.2  351.82  5426.5  352.00
#Mann=5,-1,0
  4710.1    0.05       0  4913.9    0.12       0  5104.0    0.07       0
  5110.0    0.12       0  5161.2    0.05       0
Bank Sta=5104,5110
Exp/Cntr=0.3,0.1

Type RM Length L Ch R = 1,14538,431,431,431
BEGIN DESCRIPTION:
UNT 0481 IN LACR 30.0
END DESCRIPTION:
XS GIS Cut Line= 3
      3709949.63     10658610.19      3709549.61     10658660.19
      3709349.65     10658760.17
#Sta/Elev= 30
  4603.1  348.98  4613.2  347.66  4633.4  347.32  4640.9  346.31  4646.0  346.91
  4703.9  342.56  4754.3  340.32  4807.2  335.66  4845.0  333.40  4875.2  332.30
  4882.8  331.35  4905.5  330.32  4955.8  330.01  4960.4  329.00  4963.2  328.50
  4966.4  329.00  5042.6  329.00  5051.0  329.98  5064.9  329.99  5073.3  331.47
  5087.3  331.82  5118.0  335.77  5140.4  336.96  5148.8  338.61  5162.8  339.86
  5185.1  343.43  5193.5  345.68  5207.5  347.59  5215.9  349.86  5229.8  351.17
#Mann=3,-1,0
  4603.1    0.05       0  4960.4   0.033       0  4966.4    0.05       0
Bank Sta=4960.4,4966.4
Exp/Cntr=0.3,0.1

Type RM Length L Ch R = 1,14107,240,240,240
BEGIN DESCRIPTION:
UNT 0481 IN LACR 29.0
END DESCRIPTION:
XS GIS Cut Line= 3
      3709649.57     10658160.21      3709399.61     10658260.19
      3709149.62     10658660.18
#Sta/Elev= 30
  4751.7  345.12  4766.5  344.49  4784.0  342.78  4790.7  341.12  4820.3  338.94
  4859.4  333.41  4874.2  332.92  4891.7  330.67  4931.7  329.00  4934.5  328.50
  4937.7  329.00  5101.7  329.00  5107.6  329.87  5150.6  330.70  5165.4  332.30
  5174.2  331.97  5223.2  335.75  5238.5  335.93  5275.0  338.30  5280.9  339.67
  5311.6  341.00  5317.5  342.07  5326.9  341.95  5332.8  343.11  5369.4  345.24
  5390.6  347.98  5421.3  350.15  5479.0  355.71  5484.9  357.62  5492.6  358.27
#Mann=3,-1,0
  4751.7    0.05       0  4931.7   0.033       0  4937.7    0.05       0
Bank Sta=4931.7,4937.7
Exp/Cntr=0.3,0.1

Type RM Length L Ch R = 1,13867,702,702,702
BEGIN DESCRIPTION:
UNT 0481 IN LACR 28.0
END DESCRIPTION:
XS GIS Cut Line= 3
      3709650.95     10657847.50      3709234.32     10658107.89
      3708917.10     10658846.33
#Sta/Elev= 30
  4683.7  346.70  4773.7  340.43  4810.3  335.80  4901.6  329.00  4904.3  328.50
  4907.6  329.00  5086.2  329.00  5093.3  330.39  5114.5  330.35  5174.8  337.12
  5220.3  338.57  5225.7  340.36  5249.3  339.59  5254.7  341.24  5296.4  339.83
  5301.8  341.52  5325.4  339.44  5330.8  340.40  5348.9  339.28  5425.0  340.32
  5477.6  342.52  5582.6  349.43  5781.9  357.98  5858.0  360.61  5887.0  360.18
  5934.1  362.06  5939.6  360.97  5957.7  362.55  5963.1  361.53  5978.7  362.50
#Mann=3,-1,0
  4683.7    0.05       0  4901.6   0.033       0  4907.6    0.05       0
Bank Sta=4901.6,4907.6
Exp/Cntr=0.3,0.1

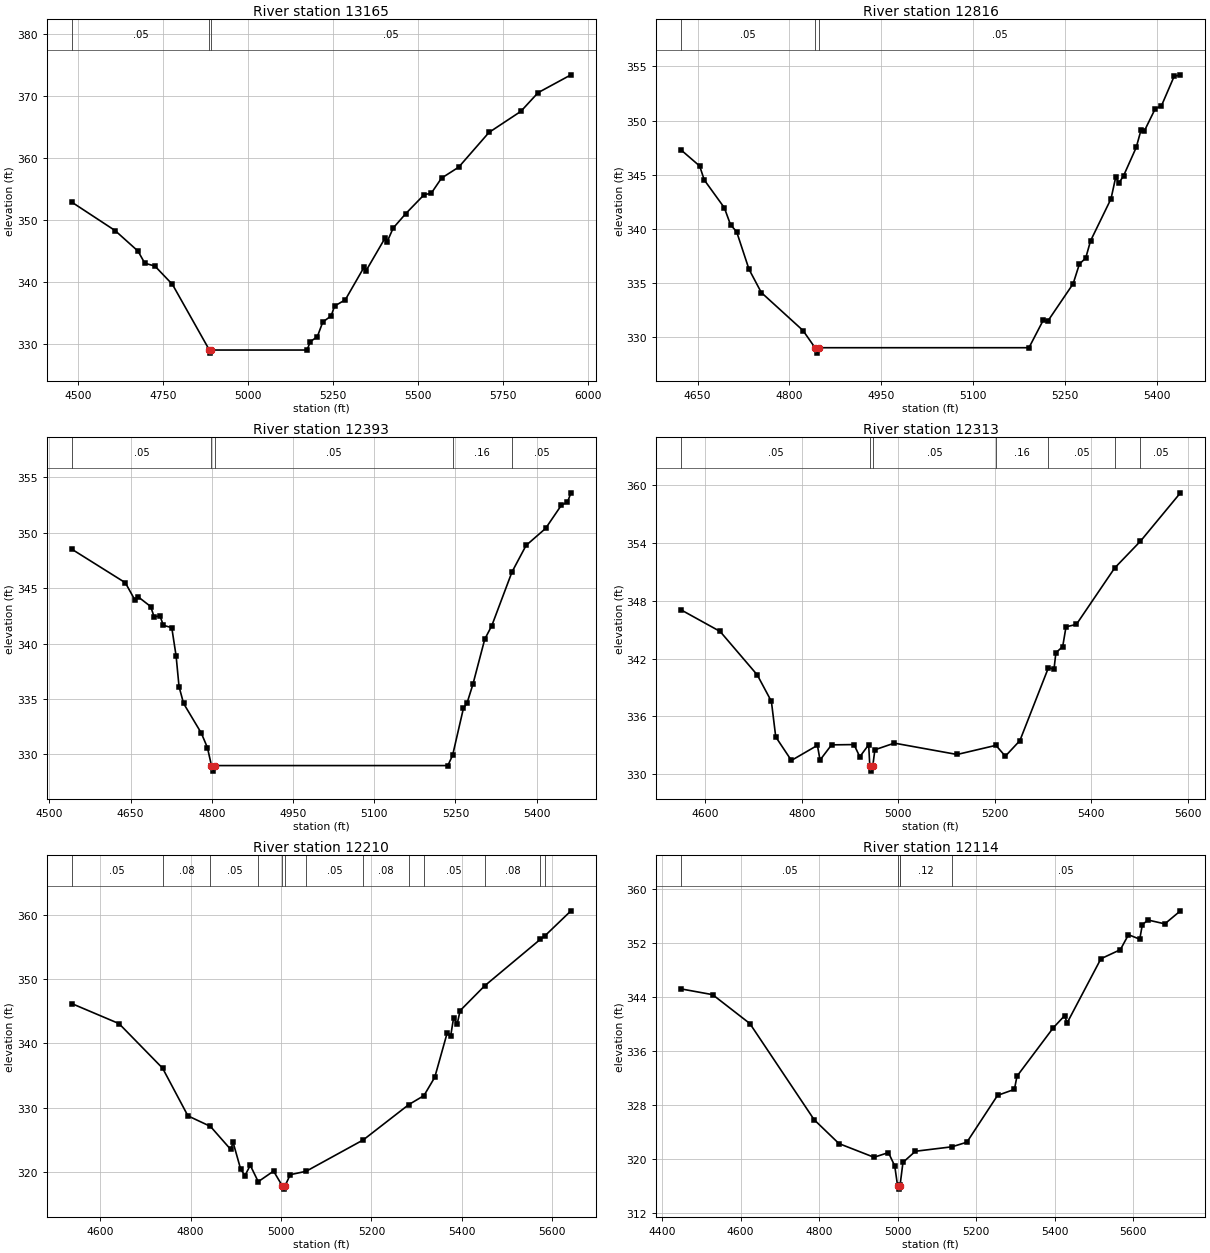
Type RM Length L Ch R = 1,13165,349,349,349
BEGIN DESCRIPTION:
UNT 0481 IN LACR 27.0
END DESCRIPTION:
XS GIS Cut Line= 2
      3709671.80     10657274.56      3708224.28     10657514.08
#Sta/Elev= 30
  4482.2  352.89  4609.8  348.29  4677.0  344.98  4697.3  343.01  4726.8  342.56
  4778.4  339.59  4886.9  329.00  4889.6  328.50  4892.9  329.00  5173.7  329.00
  5183.8  330.37  5204.1  331.15  5220.2  333.53  5244.6  334.50  5254.8  336.10
  5286.3  337.11  5342.3  342.46  5347.3  341.80  5403.3  347.09  5408.4  346.37
  5427.1  348.70  5464.3  351.04  5518.3  354.10  5538.6  354.29  5569.0  356.75
  5619.6  358.53  5708.5  364.13  5802.1  367.53  5852.8  370.55  5949.4  373.43
#Mann=3,-1,0
  4482.2    0.05       0  4886.9   0.033       0  4892.9    0.05       0
Bank Sta=4886.9,4892.9
Exp/Cntr=0.3,0.1

Type RM Length L Ch R = 1,12816,423,423,423
BEGIN DESCRIPTION:
UNT 0481 IN LACR 26.0
END DESCRIPTION:
XS GIS Cut Line= 3
      3709499.65     10657060.19      3709099.61     10657010.19
      3708699.57     10657110.20
#Sta/Elev= 30
  4623.2  347.28  4653.5  345.80  4661.0  344.51  4693.8  341.94  4703.9  340.37
  4713.9  339.72  4734.1  336.25  4754.2  334.10  4822.3  330.59  4841.9  329.00
  4844.7  328.50  4847.9  329.00  5191.3  329.00  5214.5  331.53  5222.2  331.47
  5263.4  334.91  5273.7  336.74  5284.0  337.29  5291.8  338.87  5325.3  342.77
  5333.0  344.77  5338.2  344.22  5345.9  344.91  5366.5  347.52  5374.2  349.11
  5379.4  349.00  5397.4  351.08  5407.7  351.37  5428.4  354.09  5438.7  354.23
#Mann=3,-1,0
  4623.2    0.05       0  4841.9   0.033       0  4847.9    0.05       0
Bank Sta=4841.9,4847.9
Exp/Cntr=0.3,0.1

Type RM Length L Ch R = 1,12393,80,80,80
BEGIN DESCRIPTION:
UNT 0481 IN LACR 25.0
END DESCRIPTION:
XS GIS Cut Line= 2
      3709439.20     10656427.33      3708593.55     10656794.70
#Sta/Elev= 30
  4541.3  348.51  4640.4  345.48  4658.4  343.90  4663.8  344.22  4687.3  343.33
  4693.5  342.41  4704.4  342.48  4710.7  341.64  4726.2  341.43  4734.2  338.88
  4739.6  336.12  4748.0  334.60  4780.7  331.93  4792.0  330.62  4799.5  329.00
  4802.3  328.50  4805.5  329.00  5235.9  329.00  5244.7  329.92  5264.8  334.18
  5271.3  334.62  5282.2  336.32  5304.1  340.39  5317.2  341.62  5354.4  346.45
  5380.4  348.84  5416.4  350.37  5445.8  352.48  5456.7  352.73  5463.3  353.58
#Mann=5,-1,0
  4541.3    0.05       0  4799.5   0.033       0  4805.5    0.05       0
  5244.7    0.16       0  5354.4    0.05       0
Bank Sta=4799.5,4805.5
Exp/Cntr=0.3,0.1

Type RM Length L Ch R = 1,12313,103,103,103
BEGIN DESCRIPTION:
Mapping XS 287167f8
END DESCRIPTION:
XS GIS Cut Line= 3
      3709400.95     10656364.85      3708689.18     10656659.98
      3708494.71     10656840.55
#Sta/Elev= 30
  4549.4  347.06  4630.3  344.82  4707.4  340.30  4736.7  337.55  4745.7  333.86
  4778.2  331.41  4832.2  332.98  4837.6  331.45  4861.5  333.03  4908.1  333.06
  4920.1  331.79  4938.5  333.04  4940.9  330.80  4943.7  330.30  4946.9  330.80
  4951.4  332.52  4991.7  333.21  5121.9  332.03  5202.5  332.98  5222.0  331.85
  5252.2  333.47  5311.4  341.05  5323.0  340.90  5326.9  342.61  5341.0  343.24
  5347.9  345.30  5369.4  345.55  5448.9  351.42  5502.3  354.20  5585.3  359.23
#Mann=7,-1,0
  4549.4    0.05       0  4940.9   0.033       0  4946.9    0.05       0
  5202.5    0.16       0  5311.4    0.05       0  5448.9    0.08       0
  5502.3    0.05       0
Bank Sta=4940.9,4946.9
Exp/Cntr=0.3,0.1

Type RM Length L Ch R = 1,12210,96,96,96
BEGIN DESCRIPTION:
Mapping XS a064f36b
END DESCRIPTION:
XS GIS Cut Line= 3
      3709394.02     10656291.93      3708876.68     10656465.53
      3708450.42     10656825.95
#Sta/Elev= 30
  4537.2  346.21  4641.9  343.08  4738.3  336.13  4794.3  328.70  4844.0  327.06
  4888.9  323.46  4894.2  324.56  4911.0  320.36  4920.5  319.40  4932.1  321.00
  4949.7  318.44  4983.6  320.09  5003.0  317.78  5005.7  317.28  5009.0  317.78
  5020.4  319.53  5055.5  320.06  5182.1  324.96  5282.6  330.46  5316.0  331.85
  5340.0  334.72  5367.4  341.62  5375.2  341.18  5381.7  344.01  5389.5  343.01
  5396.0  345.10  5450.0  348.95  5573.1  356.20  5583.9  356.79  5641.1  360.66
#Mann=13,-1,0
  4537.2    0.05       0  4738.3    0.08       0  4844.0    0.05       0
  4949.7    0.08       0  5003.0    0.07       0  5009.0    0.08       0
  5055.5    0.05       0  5182.1    0.08       0  5282.6    0.16       0
  5316.0    0.05       0  5450.0    0.08       0  5573.1    0.05       0
  5583.9    0.08       0
Bank Sta=5003,5009
Exp/Cntr=0.3,0.1

Type RM Length L Ch R = 1,12114,117,117,117
BEGIN DESCRIPTION:
UNT 0481 IN LACR 24.0
END DESCRIPTION:
XS GIS Cut Line= 3
      3709435.75     10656177.32      3708793.35     10656392.61
      3708333.09     10656769.82
#Sta/Elev= 30
  4448.3  345.26  4528.6  344.41  4623.5  340.13  4787.4  325.88  4850.5  322.35
  4939.9  320.32  4976.7  321.01  4992.7  319.04  5000.0  316.10  5002.7  315.60
  5006.0  316.10  5006.3  316.17  5013.7  319.56  5045.4  321.21  5138.5  321.87
  5176.6  322.55  5254.8  329.49  5297.8  330.38  5304.3  332.33  5396.9  339.51
  5425.6  341.29  5432.1  340.23  5518.2  349.73  5567.7  351.07  5588.5  353.29
  5617.2  352.63  5623.7  354.76  5638.0  355.47  5681.1  354.90  5720.9  356.83
#Mann=5,-1,0
  4448.3    0.05       0  5000.0    0.04       0  5006.0    0.05       0
  5006.3    0.12       0  5138.5    0.05       0
Bank Sta=5000,5006
Exp/Cntr=0.3,0.1

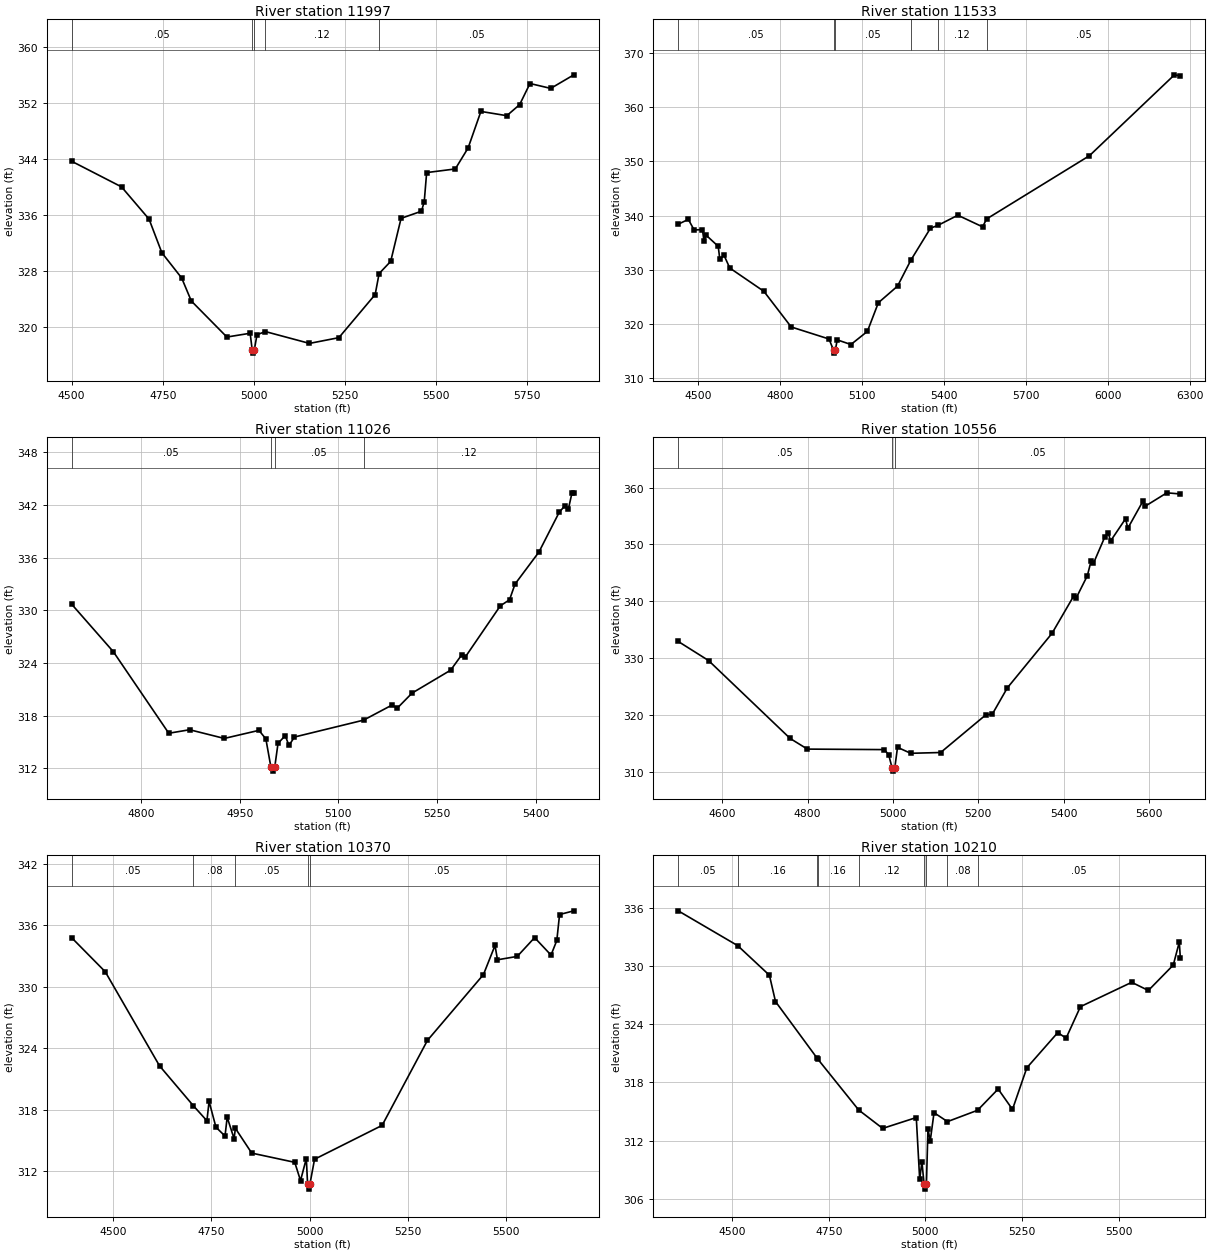
Type RM Length L Ch R = 1,11997,464,464,464
BEGIN DESCRIPTION:
Mapping XS bc8ef341
END DESCRIPTION:
XS GIS Cut Line= 3
      3709411.37     10656121.79      3708775.98     10656288.45
      3708235.87     10656766.24
#Sta/Elev= 30
  4500.3  343.73  4636.8  340.08  4712.4  335.47  4747.6  330.66  4801.9  327.06
  4828.4  323.77  4926.0  318.62  4989.9  319.16  4995.4  316.82  4998.1  316.32
  5001.4  316.82  5008.7  318.95  5031.7  319.40  5152.7  317.71  5233.4  318.53
  5333.0  324.69  5343.8  327.69  5375.6  329.43  5404.1  335.58  5460.1  336.60
  5467.7  337.97  5474.3  342.12  5552.9  342.64  5588.1  345.64  5623.2  350.86
  5694.3  350.25  5729.5  351.83  5757.9  354.85  5814.8  354.15  5878.3  356.09
#Mann=5,-1,0
  4500.3    0.05       0  4995.4    0.03       0  5001.4    0.05       0
  5031.7    0.12       0  5343.8    0.05       0
Bank Sta=4995.4,5001.4
Exp/Cntr=0.3,0.1

Type RM Length L Ch R = 1,11533,507,507,507
BEGIN DESCRIPTION:
UNT 0481 IN LACR 23.0
END DESCRIPTION:
XS GIS Cut Line= 3
      3709515.58     10656034.98      3709157.93     10655809.28
      3707748.19     10655694.70
#Sta/Elev= 30
  4428.4  338.41  4465.3  339.30  4486.5  337.36  4517.0  337.40  4522.9  335.22
  4530.1  336.40  4574.7  334.33  4580.6  331.91  4595.9  332.67  4617.1  330.32
  4741.8  326.02  4841.8  319.44  4980.1  317.22  4997.1  315.11  4999.9  314.61
  5003.1  315.11  5010.2  317.06  5060.3  316.20  5120.5  318.62  5160.7  323.91
  5230.9  326.98  5279.5  331.76  5351.3  337.67  5378.4  338.19  5451.6  340.07
  5541.9  337.93  5557.5  339.40  5933.2  351.06  6244.2  365.99  6265.7  365.79
#Mann=6,-1,0
  4428.4    0.05       0  4997.1    0.03       0  5003.1    0.05       0
  5279.5    0.16       0  5378.4    0.12       0  5557.5    0.05       0
Bank Sta=4997.1,5003.1
Exp/Cntr=0.3,0.1

Type RM Length L Ch R = 1,11026,470,470,470
BEGIN DESCRIPTION:
UNT 0481 IN LACR 22.0
END DESCRIPTION:
XS GIS Cut Line= 3
      3709199.58     10655410.18      3708899.61     10655310.19
      3708499.62     10655510.18
#Sta/Elev= 30
  4694.6  330.67  4757.8  325.28  4842.1  316.00  4873.8  316.40  4926.5  315.41
  4979.2  316.33  4989.7  315.36  4997.3  312.19  5000.0  311.69  5003.3  312.19
  5008.2  314.85  5019.2  315.73  5024.8  314.61  5033.2  315.57  5138.2  317.49
  5181.3  319.20  5189.7  318.87  5212.0  320.57  5270.7  323.18  5287.5  324.92
  5293.1  324.69  5346.2  330.50  5360.2  331.19  5368.6  332.98  5404.9  336.62
  5435.7  341.14  5444.0  341.86  5449.6  341.49  5455.2  343.36  5458.0  343.36
#Mann=4,-1,0
  4694.6    0.05       0  4997.3    0.03       0  5003.3    0.05       0
  5138.2    0.12       0
Bank Sta=4997.3,5003.3
Exp/Cntr=0.3,0.1

Type RM Length L Ch R = 1,10556,186,186,186
BEGIN DESCRIPTION:
Mapping XS 2d7c3f43
END DESCRIPTION:
XS GIS Cut Line= 2
      3709406.23     10654972.49      3708269.01     10654672.99
#Sta/Elev= 30
  4497.0  332.91  4568.0  329.55  4759.2  315.82  4799.5  313.95  4979.5  313.86
  4989.9  312.97  4998.1  310.57  5000.9  310.07  5004.1  310.57  5010.6  314.26
  5041.6  313.21  5111.7  313.35  5217.4  319.98  5232.7  320.11  5267.8  324.73
  5372.5  334.34  5423.9  340.99  5429.1  340.57  5455.2  344.48  5464.2  347.14
  5469.4  346.65  5496.6  351.39  5504.5  351.95  5509.7  350.61  5544.8  354.53
  5550.0  352.84  5585.2  357.59  5590.3  356.71  5641.4  359.09  5673.0  358.89
#Mann=3,-1,0
  4497.0    0.05       0  4998.1    0.03       0  5004.1    0.05       0
Bank Sta=4998.1,5004.1
Exp/Cntr=0.3,0.1

Type RM Length L Ch R = 1,10370,160,160,160
BEGIN DESCRIPTION:
UNT 0481 IN LACR 21.0
END DESCRIPTION:
XS GIS Cut Line= 3
      3709445.25     10654929.07      3708972.17     10654712.06
      3708360.19     10654269.35
#Sta/Elev= 30
  4395.7  334.76  4480.7  331.46  4618.7  322.29  4704.5  318.41  4739.1  316.94
  4744.6  318.82  4762.1  316.31  4785.1  315.45  4790.6  317.28  4808.1  315.20
  4811.5  316.20  4853.0  313.79  4962.3  312.89  4977.0  311.11  4991.7  313.26
  4994.9  310.78  4997.6  310.28  5000.9  310.78  5012.6  313.19  5184.3  316.49
  5299.5  324.77  5441.8  331.18  5471.2  334.02  5477.4  332.62  5527.7  332.95
  5571.8  334.78  5613.5  333.08  5628.2  334.50  5635.2  337.03  5671.5  337.39
#Mann=5,-1,0
  4395.7    0.05       0  4704.5    0.08       0  4811.5    0.05       0
  4994.9    0.04       0  5000.9    0.05       0
Bank Sta=4994.9,5000.9
Exp/Cntr=0.3,0.1

Type RM Length L Ch R = 1,10210,255,255,255
BEGIN DESCRIPTION:
UNT 0481 IN LACR 20.0
END DESCRIPTION:
XS GIS Cut Line= 2
      3709480.01     10654833.61      3708361.32     10654174.53
#Sta/Elev= 30
  4360.9  335.68  4514.7  332.09  4596.7  329.04  4612.4  326.33  4720.4  320.47
  4721.5  320.41  4827.5  315.15  4889.6  313.25  4976.5  314.37  4985.3  308.00
  4991.1  309.81  4996.7  307.49  4999.5  306.99  5002.7  307.49  5006.7  313.22
  5012.5  311.94  5022.4  314.87  5057.2  313.95  5135.0  315.12  5188.2  317.31
  5225.3  315.21  5262.4  319.50  5342.5  323.13  5363.9  322.55  5401.0  325.80
  5533.6  328.31  5576.7  327.47  5641.1  330.09  5656.7  332.46  5659.3  330.85
#Mann=9,-1,0
  4360.9    0.05       0  4514.7    0.16       0  4720.4    0.05       0
  4721.5    0.16       0  4827.5    0.12       0  4996.7    0.07       0
  5002.7    0.12       0  5057.2    0.08       0  5135.0    0.05       0
Bank Sta=4996.7,5002.7
Exp/Cntr=0.3,0.1

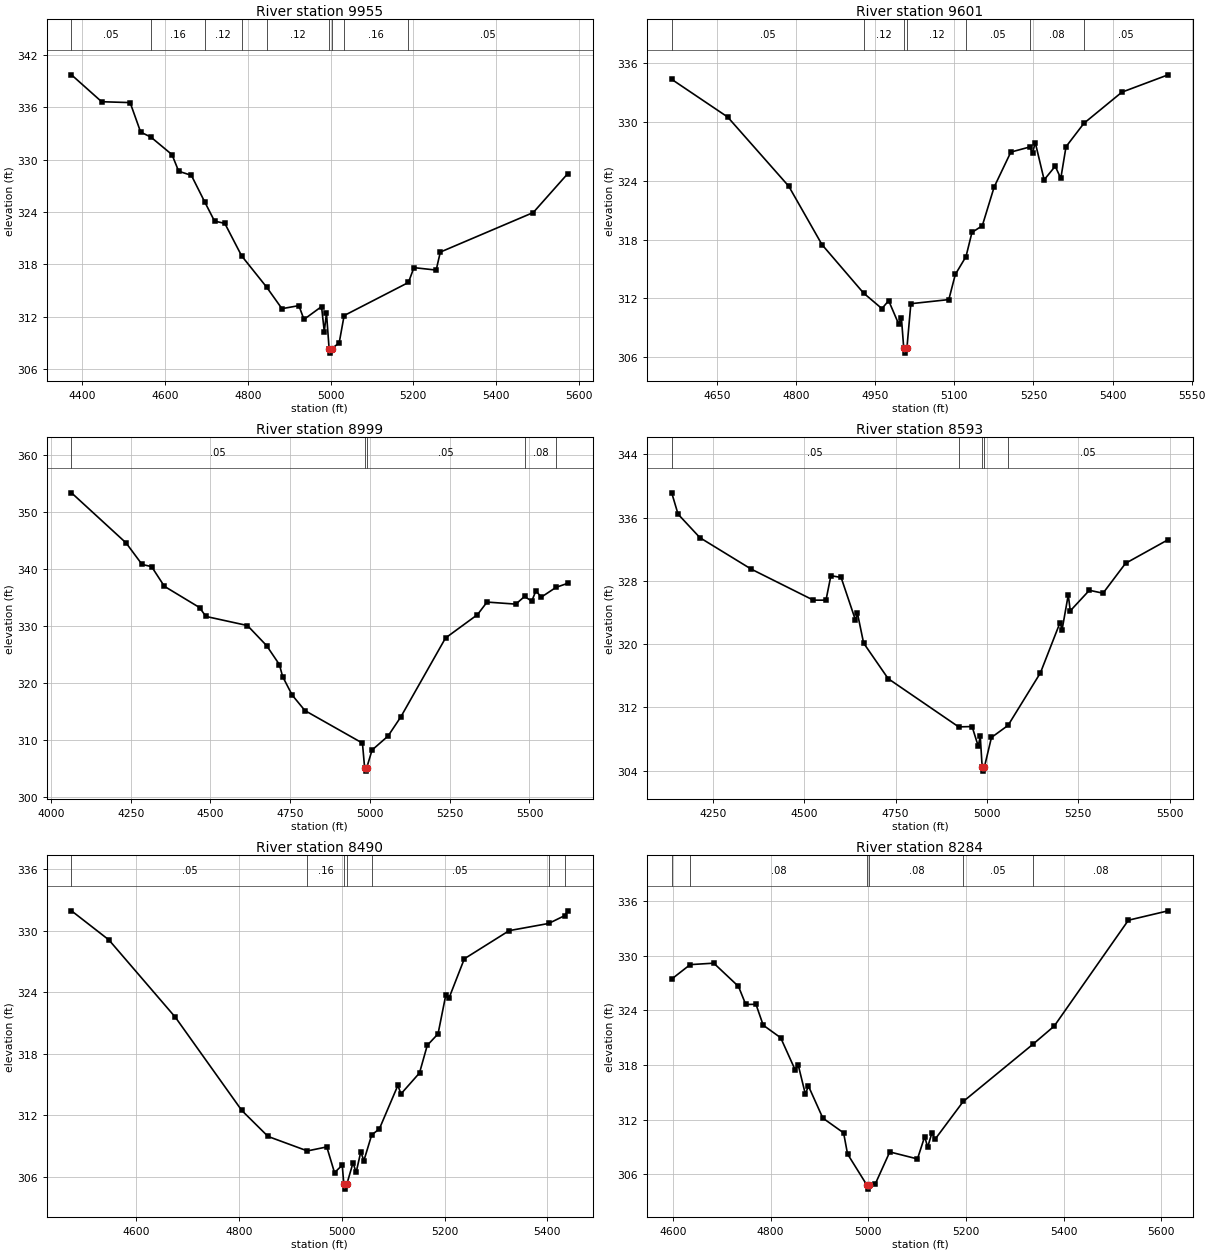
Type RM Length L Ch R = 1,9955,354,354,354
BEGIN DESCRIPTION:
Mapping XS c40a486e
END DESCRIPTION:
XS GIS Cut Line= 2
      3709558.13     10654473.35      3708429.62     10654065.35
#Sta/Elev= 30
  4373.8  339.70  4446.7  336.62  4515.6  336.52  4541.0  333.14  4565.8  332.57
  4616.8  330.56  4632.9  328.66  4663.6  328.19  4695.5  325.18  4719.6  322.95
  4744.4  322.69  4785.1  318.97  4845.5  315.39  4882.6  312.92  4923.5  313.27
  4935.8  311.69  4978.3  313.16  4984.9  310.30  4990.2  312.42  4996.6  308.33
  4999.4  307.83  5002.6  308.33  5020.9  309.00  5032.9  312.13  5188.3  315.92
  5201.6  317.62  5255.4  317.34  5265.4  319.40  5490.1  323.93  5573.8  328.40
#Mann=9,-1,0
  4373.8    0.05       0  4565.8    0.16       0  4695.5    0.12       0
  4785.1    0.16       0  4845.5    0.12       0  4996.6    0.07       0
  5002.6    0.12       0  5032.9    0.16       0  5188.3    0.05       0
Bank Sta=4996.6,5002.6
Exp/Cntr=0.3,0.1

Type RM Length L Ch R = 1,9601,602,602,602
BEGIN DESCRIPTION:
UNT 0481 IN LACR 19.0
END DESCRIPTION:
XS GIS Cut Line= 2
      3709450.38     10654061.07      3708556.33     10653765.95
#Sta/Elev= 30
  4563.8  334.34  4669.9  330.50  4785.8  323.44  4848.9  317.48  4927.6  312.55
  4962.5  310.96  4975.3  311.77  4994.2  309.40  4999.5  310.01  5003.9  306.92
  5006.7  306.42  5009.9  306.92  5017.4  311.46  5089.4  311.88  5101.7  314.44
  5122.0  316.27  5133.3  318.73  5152.9  319.41  5175.4  323.36  5207.0  326.92
  5242.8  327.44  5248.2  326.85  5253.4  327.89  5270.2  324.09  5291.2  325.48
  5301.8  324.24  5311.7  327.47  5345.7  329.86  5417.6  333.03  5505.3  334.80
#Mann=7,-1,0
  4563.8    0.05       0  4927.6    0.12       0  5003.9    0.07       0
  5009.9    0.12       0  5122.0    0.05       0  5242.8    0.08       0
  5345.7    0.05       0
Bank Sta=5003.9,5009.9
Exp/Cntr=0.3,0.1

Type RM Length L Ch R = 1,8999,406,406,406
BEGIN DESCRIPTION:
UNT 0481 IN LACR 18.0
END DESCRIPTION:
XS GIS Cut Line= 2
      3710240.39     10653488.17      3708686.55     10653410.04
#Sta/Elev= 30
  4064.5  353.37  4235.5  344.58  4285.6  340.80  4315.6  340.41  4355.6  336.96
  4465.8  333.23  4485.8  331.67  4616.0  330.07  4676.1  326.54  4716.1  323.22
  4726.2  321.12  4756.2  317.86  4796.2  315.14  4976.4  309.43  4983.4  305.01
  4986.2  304.51  4989.4  305.01  5006.5  308.21  5056.5  310.66  5096.6  314.02
  5236.8  327.88  5336.9  331.98  5366.9  334.19  5457.0  333.83  5484.5  335.17
  5507.1  334.35  5520.0  336.16  5537.1  335.06  5583.3  336.78  5620.3  337.49
#Mann=5,-1,0
  4064.5    0.05       0  4983.4    0.03       0  4989.4    0.05       0
  5484.5    0.08       0  5583.3    0.05       0
Bank Sta=4983.4,4989.4
Exp/Cntr=0.3,0.1

Type RM Length L Ch R = 1,8593,103,103,103
BEGIN DESCRIPTION:
UNT 0481 IN LACR 17.0
END DESCRIPTION:
XS GIS Cut Line= 3
      3710216.95     10652877.67      3709795.13     10652898.50
      3708956.58     10653315.17
#Sta/Elev= 30
  4137.3  339.14  4154.7  336.44  4214.7  333.46  4354.9  329.49  4525.1  325.56
  4559.6  325.56  4573.0  328.66  4601.0  328.43  4640.2  323.05  4645.8  323.88
  4662.6  320.13  4729.8  315.63  4922.7  309.53  4959.5  309.57  4976.3  307.09
  4981.9  308.32  4987.1  304.43  4989.9  303.93  4993.1  304.43  5012.5  308.19
  5058.0  309.72  5146.5  316.36  5200.3  322.73  5205.9  321.83  5222.7  326.22
  5228.3  324.21  5280.5  326.81  5317.9  326.44  5379.5  330.22  5496.0  333.21
#Mann=5,-1,0
  4137.3    0.05       0  4922.7    0.16       0  4987.1    0.07       0
  4993.1    0.16       0  5058.0    0.05       0
Bank Sta=4987.1,4993.1
Exp/Cntr=0.3,0.1

Type RM Length L Ch R = 1,8490,206,206,206
BEGIN DESCRIPTION:
Mapping XS d37d422e
END DESCRIPTION:
XS GIS Cut Line= 2
      3709831.50     10652702.53      3709025.33     10653235.65
#Sta/Elev= 30
  4473.7  331.93  4546.5  329.10  4675.9  321.57  4805.3  312.49  4856.4  309.96
  4933.0  308.55  4970.8  308.94  4985.8  306.44  5000.9  307.16  5003.9  305.33
  5006.6  304.83  5009.9  305.33  5021.9  307.40  5027.9  306.45  5037.0  308.47
  5043.0  307.60  5058.2  310.11  5073.1  310.69  5109.2  314.93  5115.2  314.10
  5151.3  316.14  5166.4  318.83  5187.4  319.95  5202.5  323.73  5208.5  323.40
  5238.6  327.26  5325.9  330.00  5402.8  330.70  5433.9  331.46  5440.2  331.92
#Mann=7,-1,0
  4473.7    0.05       0  4933.0    0.16       0  5003.9    0.07       0
  5009.9    0.16       0  5058.2    0.05       0  5402.8    0.08       0
  5433.9    0.05       0
Bank Sta=5003.9,5009.9
Exp/Cntr=0.3,0.1

Type RM Length L Ch R = 1,8284,155,155,155
BEGIN DESCRIPTION:
UNT 0481 IN LACR 16.0
END DESCRIPTION:
XS GIS Cut Line= 2
      3709788.16     10652567.94      3708954.84     10653149.53
#Sta/Elev= 30
  4597.6  327.42  4635.4  329.00  4683.7  329.16  4734.3  326.61  4749.2  324.63
  4770.1  324.65  4784.9  322.36  4820.7  320.98  4850.4  317.45  4856.4  318.04
  4871.3  314.78  4877.4  315.70  4907.0  312.17  4949.5  310.55  4957.6  308.23
  4996.5  304.88  4999.3  304.38  5002.5  304.88  5014.3  304.94  5044.0  308.46
  5100.7  307.69  5115.5  310.14  5121.6  308.98  5130.4  310.57  5136.5  309.83
  5194.4  313.99  5336.7  320.25  5380.7  322.26  5532.5  333.87  5613.8  334.90
#Mann=6,-1,0
  4597.6    0.05       0  4635.4    0.08       0  4996.5    0.07       0
  5002.5    0.08       0  5194.4    0.05       0  5336.7    0.08       0
Bank Sta=4996.5,5002.5
Exp/Cntr=0.3,0.1