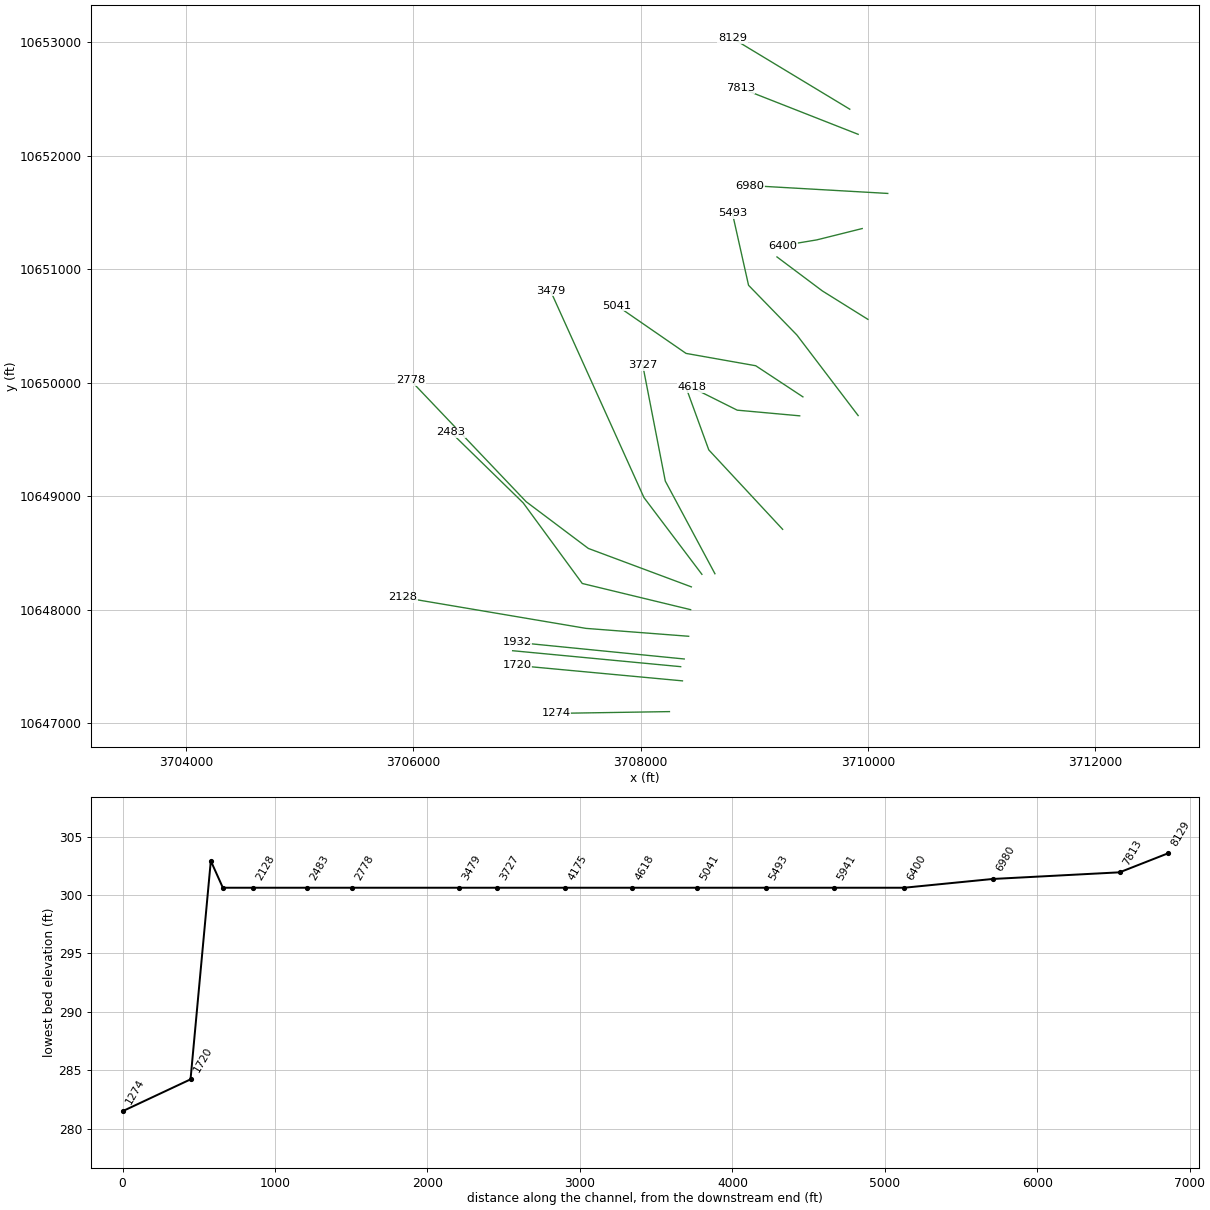
HEC-RAS study UNT 0481 IN LACR.prj: UNT 0481 IN LACR Base Level Engineering

--- UNT 0481 IN LACR.g01 (geometry) --- (continued)

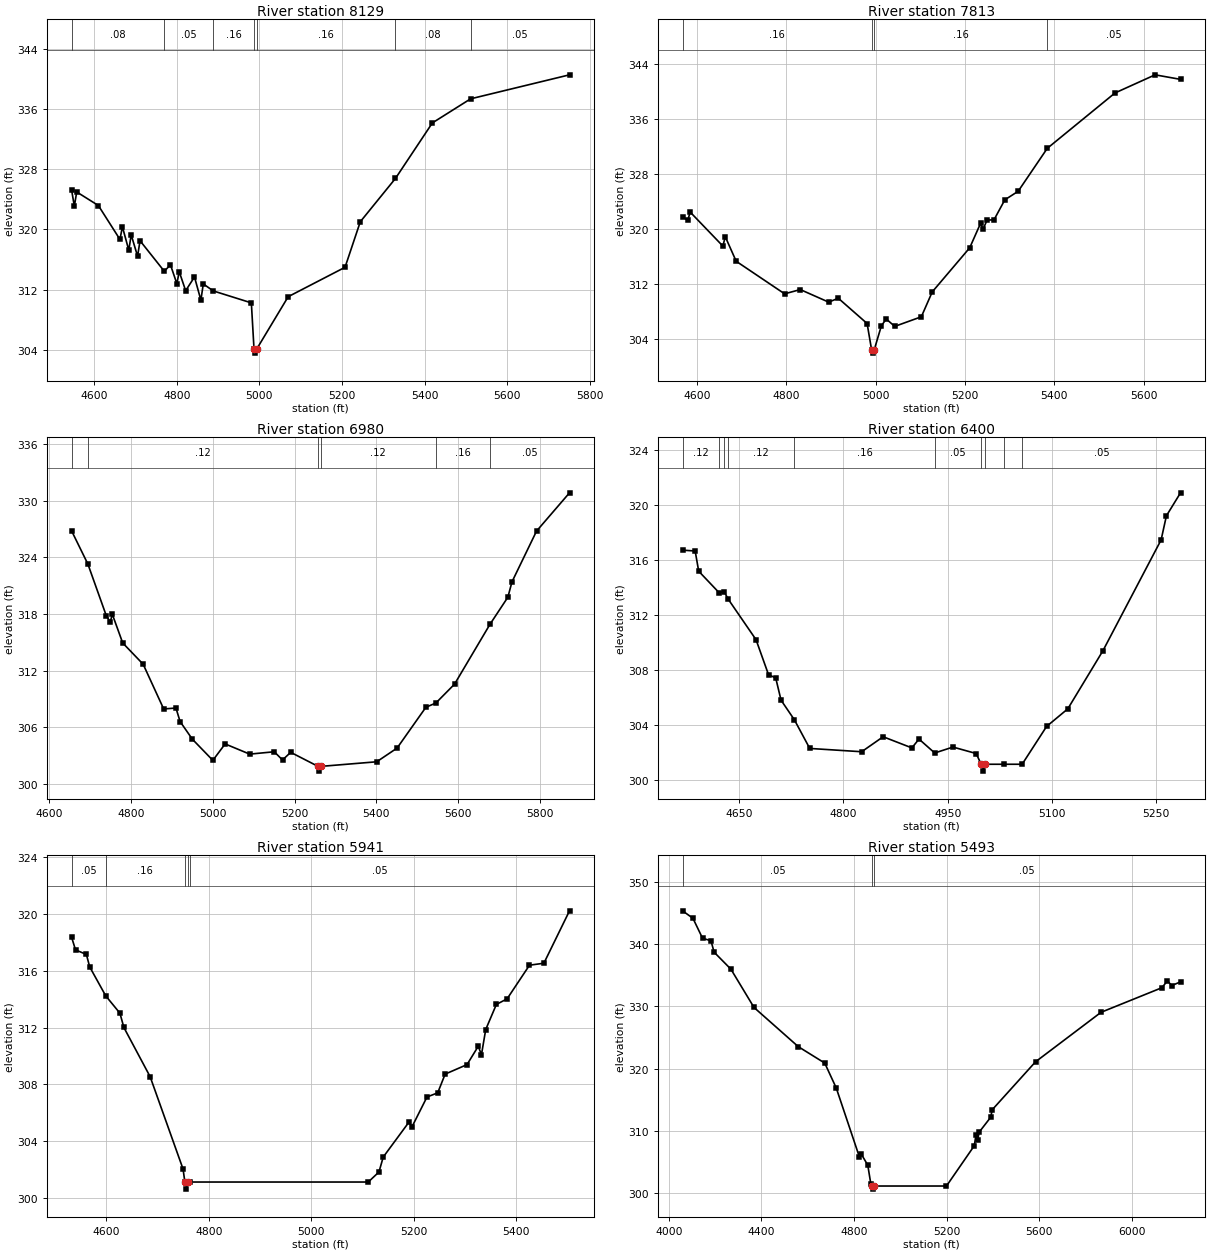
Type RM Length L Ch R = 1,8129,316,316,316
BEGIN DESCRIPTION:
UNT 0481 IN LACR 15.0
END DESCRIPTION:
XS GIS Cut Line= 2
      3709840.26     10652411.69      3708808.51     10653035.94
#Sta/Elev= 30
  4545.1  325.27  4551.8  323.10  4557.6  324.98  4610.0  323.18  4662.3  318.67
  4668.2  320.36  4683.7  317.24  4689.5  319.28  4705.0  316.44  4710.9  318.50
  4769.7  314.44  4784.6  315.30  4800.1  312.79  4805.9  314.38  4821.4  311.86
  4842.8  313.68  4858.3  310.60  4864.1  312.76  4888.1  311.83  4980.5  310.24
  4987.0  304.06  4989.7  303.56  4993.0  304.06  5069.7  311.06  5207.4  314.97
  5244.3  321.02  5329.5  326.78  5418.9  334.16  5511.5  337.36  5751.0  340.55
#Mann=7,-1,0
  4545.1    0.08       0  4769.7    0.05       0  4888.1    0.16       0
  4987.0    0.07       0  4993.0    0.16       0  5329.5    0.08       0
  5511.5    0.05       0
Bank Sta=4987,4993
Exp/Cntr=0.3,0.1

Type RM Length L Ch R = 1,7813,833,833,833
BEGIN DESCRIPTION:
Mapping XS d1581adf
END DESCRIPTION:
XS GIS Cut Line= 2
      3709914.01     10652190.36      3708876.66     10652598.35
#Sta/Elev= 30
  4567.9  321.81  4579.5  321.25  4584.9  322.47  4658.1  317.52  4663.5  318.88
  4687.9  315.31  4796.3  310.57  4831.4  311.19  4895.0  309.36  4916.5  309.93
  4981.0  306.25  4991.0  302.44  4993.7  301.94  4997.0  302.44  5013.0  305.93
  5023.9  306.91  5042.8  305.83  5102.4  307.23  5126.8  310.85  5210.7  317.27
  5235.1  320.85  5240.5  319.95  5249.6  321.32  5264.9  321.32  5289.3  324.25
  5319.1  325.49  5384.3  331.74  5535.9  339.80  5625.7  342.44  5682.6  341.78
#Mann=4,-1,0
  4567.9    0.16       0  4991.0    0.07       0  4997.0    0.16       0
  5384.3    0.05       0
Bank Sta=4991,4997
Exp/Cntr=0.3,0.1

Type RM Length L Ch R = 1,6980,580,580,580
BEGIN DESCRIPTION:
UNT 0481 IN LACR 14.0
END DESCRIPTION:
XS GIS Cut Line= 2
      3710174.43     10651669.52      3708959.12     10651738.97
#Sta/Elev= 30
  4654.7  326.81  4694.6  323.29  4739.7  317.81  4749.3  317.15  4754.3  317.98
  4779.7  314.94  4829.8  312.68  4879.9  307.95  4909.9  308.05  4920.0  306.62
  4950.0  304.75  5000.1  302.51  5030.1  304.25  5090.2  303.17  5150.3  303.42
  5170.4  302.55  5190.4  303.36  5257.5  301.87  5260.3  301.37  5263.5  301.87
  5400.7  302.36  5450.5  303.81  5520.9  308.13  5545.3  308.58  5591.0  310.58
  5677.4  316.90  5721.3  319.78  5731.3  321.40  5791.4  326.78  5872.0  330.83
#Mann=6,-1,0
  4654.7    0.05       0  4694.6    0.12       0  5257.5    0.07       0
  5263.5    0.12       0  5545.3    0.16       0  5677.4    0.05       0
Bank Sta=5257.5,5263.5
Exp/Cntr=0.3,0.1

Type RM Length L Ch R = 1,6400,459,459,459
BEGIN DESCRIPTION:
UNT 0481 IN LACR 13.0
END DESCRIPTION:
XS GIS Cut Line= 3
      3709949.63     10651360.19      3709549.61     10651260.19
      3709249.57     10651210.18
#Sta/Elev= 30
  4568.6  316.69  4586.7  316.63  4591.8  315.16  4621.1  313.60  4628.4  313.68
  4633.8  313.16  4674.3  310.18  4692.3  307.63  4702.6  307.40  4710.3  305.78
  4729.4  304.36  4751.6  302.27  4826.3  302.03  4857.2  303.12  4898.5  302.31
  4908.8  302.95  4931.4  301.94  4957.7  302.37  4991.1  301.90  4998.2  301.12
  5001.0  300.62  5004.2  301.12  5031.8  301.12  5057.2  301.12  5092.4  303.87
  5122.9  305.15  5173.5  309.38  5257.2  317.44  5264.8  319.19  5285.1  320.86
#Mann=10,-1,0
  4568.6    0.12       0  4621.1    0.05       0  4628.4    0.16       0
  4633.8    0.12       0  4729.4    0.16       0  4931.4    0.05       0
  4998.2   0.033       0  5004.2    0.05       0  5031.8    0.16       0
  5057.2    0.05       0
Bank Sta=4998.2,5004.2
Exp/Cntr=0.3,0.1

Type RM Length L Ch R = 1,5941,448,448,448
BEGIN DESCRIPTION:
UNT 0481 IN LACR 12.0
END DESCRIPTION:
XS GIS Cut Line= 3
      3709999.65     10650560.17      3709599.61     10650810.19
      3709199.64     10651110.16
#Sta/Elev= 30
  4532.3  318.37  4540.0  317.47  4561.2  317.15  4567.7  316.27  4599.0  314.23
  4626.7  313.01  4634.3  312.01  4685.6  308.54  4749.9  302.03  4753.4  301.12
  4756.2  300.62  4759.4  301.12  4763.7  301.12  5111.3  301.12  5132.2  301.83
  5140.5  302.88  5190.5  305.33  5196.8  305.02  5225.9  307.11  5246.8  307.40
  5261.3  308.72  5304.0  309.39  5325.9  310.68  5332.2  310.09  5340.5  311.86
  5361.3  313.63  5382.2  314.02  5425.9  316.39  5454.0  316.53  5504.0  320.22
#Mann=5,-1,0
  4532.3    0.05       0  4599.0    0.16       0  4753.4   0.033       0
  4759.4    0.16       0  4763.7    0.05       0
Bank Sta=4753.4,4759.4
Exp/Cntr=0.3,0.1

Type RM Length L Ch R = 1,5493,452,452,452
BEGIN DESCRIPTION:
UNT 0481 IN LACR 11.0
END DESCRIPTION:
XS GIS Cut Line= 4
      3709913.92     10649712.45      3709374.92     10650422.23
      3708949.61     10650860.19      3708807.29     10651495.72
#Sta/Elev= 30
  4058.8  345.37  4103.6  344.17  4145.2  340.96  4181.5  340.56  4195.2  338.72
  4267.9  335.98  4367.7  329.83  4559.1  323.53  4673.5  320.89  4723.4  316.87
  4823.2  305.81  4831.5  306.25  4859.6  304.47  4873.1  301.38  4878.4  301.12
  4881.2  300.62  4884.4  301.12  5199.8  301.12  5320.1  307.60  5327.1  309.27
  5334.3  308.51  5341.3  309.79  5390.9  312.17  5397.8  313.39  5584.8  321.09
  5868.0  329.05  6130.9  333.00  6154.9  334.09  6174.3  333.36  6211.8  333.95
#Mann=3,-1,0
  4058.8    0.05       0  4878.4   0.033       0  4884.4    0.05       0
Bank Sta=4878.4,4884.4
Exp/Cntr=0.3,0.1

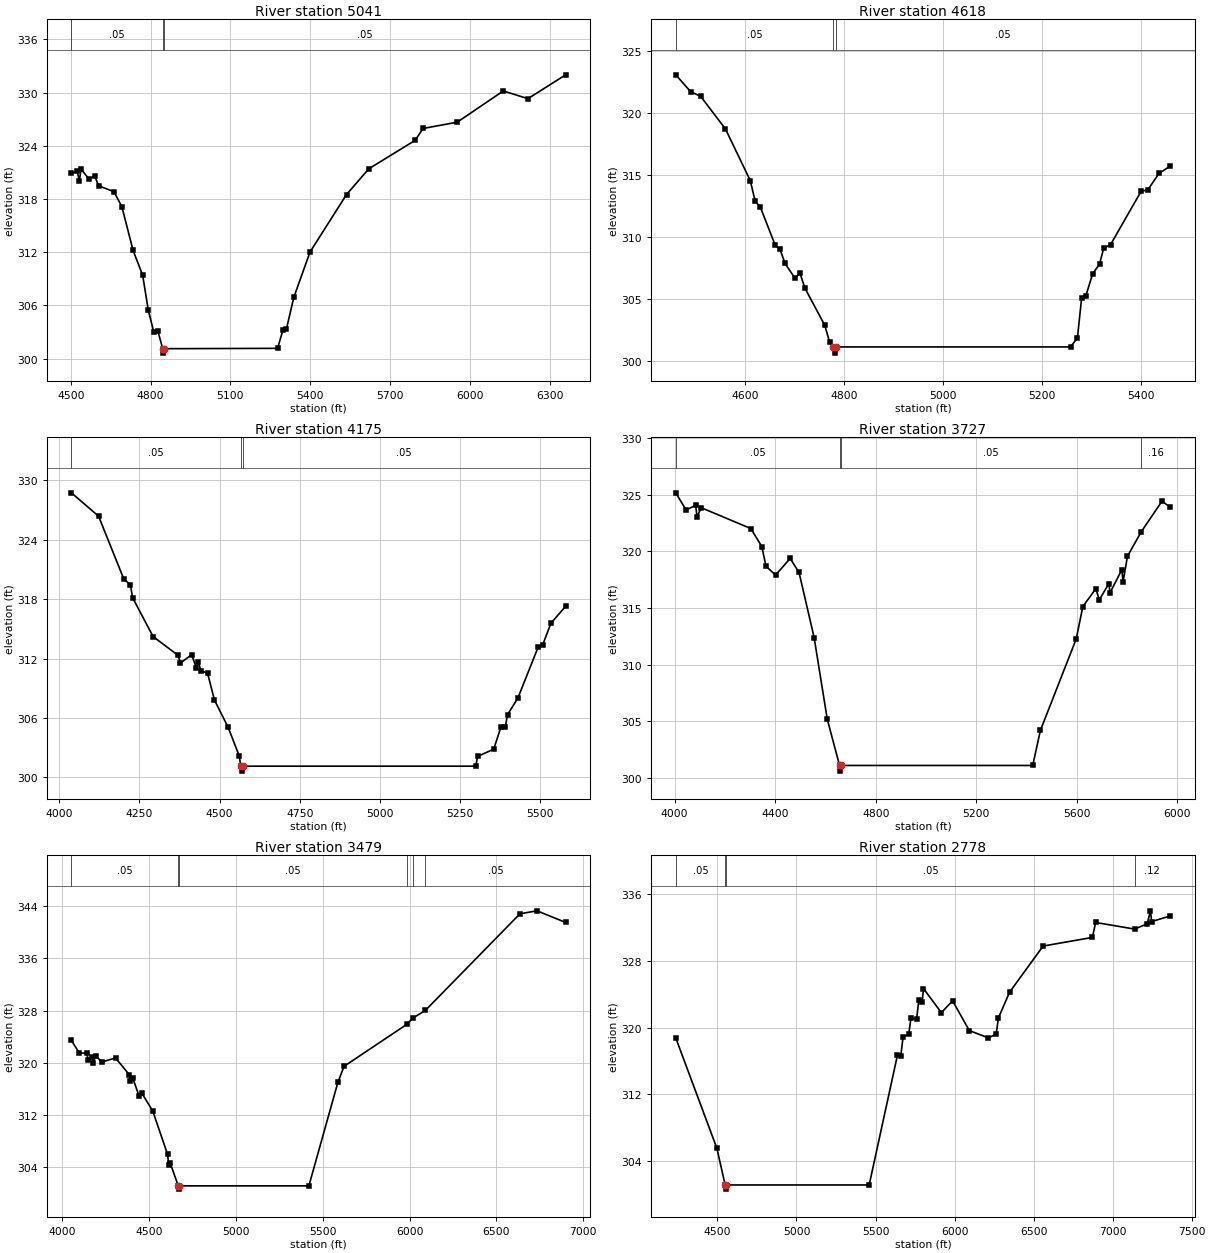
Type RM Length L Ch R = 1,5041,423,423,423
BEGIN DESCRIPTION:
UNT 0481 IN LACR 10.0
END DESCRIPTION:
XS GIS Cut Line= 4
      3709427.85     10649877.34      3709012.69     10650151.47
      3708399.61     10650260.19      3707793.05     10650679.26
#Sta/Elev= 30
  4502.5  320.90  4524.4  321.11  4532.6  320.04  4538.6  321.38  4568.7  320.26
  4589.8  320.62  4604.9  319.49  4662.1  318.84  4692.1  317.15  4734.3  312.21
  4770.4  309.40  4791.5  305.46  4812.5  302.96  4827.6  303.10  4845.7  301.12
  4848.4  300.62  4851.7  301.12  5277.3  301.16  5297.7  303.24  5310.3  303.30
  5338.3  306.90  5399.2  312.02  5536.5  318.51  5620.1  321.41  5794.3  324.62
  5824.1  325.96  5952.5  326.67  6125.5  330.19  6218.2  329.32  6359.9  332.01
#Mann=3,-1,0
  4502.5    0.05       0  4845.7   0.033       0  4851.7    0.05       0
Bank Sta=4845.7,4851.7
Exp/Cntr=0.3,0.1

Type RM Length L Ch R = 1,4618,443,443,443
BEGIN DESCRIPTION:
UNT 0481 IN LACR 9.0
END DESCRIPTION:
XS GIS Cut Line= 3
      3709399.59     10649710.19      3708849.61     10649760.19
      3708449.57     10649960.21
#Sta/Elev= 30
  4459.5  323.05  4489.6  321.69  4509.7  321.32  4559.9  318.69  4610.1  314.53
  4620.1  312.85  4630.2  312.42  4660.3  309.34  4670.3  308.98  4680.4  307.85
  4700.5  306.66  4710.5  307.07  4720.6  305.86  4760.7  302.87  4770.8  301.48
  4777.8  301.12  4780.5  300.62  4783.8  301.12  5257.7  301.12  5271.7  301.85
  5280.1  305.03  5288.5  305.21  5302.4  307.00  5316.4  307.80  5324.8  309.07
  5338.8  309.37  5400.3  313.65  5414.2  313.79  5436.6  315.10  5459.0  315.69
#Mann=3,-1,0
  4459.5    0.05       0  4777.8   0.033       0  4783.8    0.05       0
Bank Sta=4777.8,4783.8
Exp/Cntr=0.3,0.1

Type RM Length L Ch R = 1,4175,448,448,448
BEGIN DESCRIPTION:
UNT 0481 IN LACR 8.0
END DESCRIPTION:
XS GIS Cut Line= 3
      3709249.61     10648710.19      3708599.61     10649410.19
      3708399.60     10649960.21
#Sta/Elev= 30
  4038.3  328.74  4123.1  326.38  4201.3  320.06  4222.3  319.42  4229.3  318.13
  4293.1  314.21  4370.8  312.32  4378.1  311.55  4413.3  312.38  4427.5  311.07
  4434.3  311.66  4441.7  310.75  4462.6  310.54  4484.2  307.80  4526.7  305.06
  4561.8  302.13  4566.2  301.12  4568.9  300.62  4572.2  301.12  5298.8  301.12
  5304.1  302.10  5354.7  302.84  5376.6  305.03  5390.6  305.09  5397.9  306.34
  5429.8  307.99  5493.7  313.20  5507.6  313.40  5532.9  315.56  5578.8  317.28
#Mann=3,-1,0
  4038.3    0.05       0  4566.2   0.033       0  4572.2    0.05       0
Bank Sta=4566.2,4572.2
Exp/Cntr=0.3,0.1

Type RM Length L Ch R = 1,3727,248,248,248
BEGIN DESCRIPTION:
UNT 0481 IN LACR 7.0
END DESCRIPTION:
XS GIS Cut Line= 3
      3708653.73     10648319.07      3708216.96     10649135.67
      3708018.55     10650156.40
#Sta/Elev= 30
  4004.9  325.17  4045.6  323.66  4083.9  324.06  4089.5  323.04  4105.8  323.86
  4303.3  322.02  4347.2  320.43  4363.4  318.71  4401.7  317.91  4459.8  319.38
  4495.1  318.15  4555.2  312.40  4607.2  305.22  4656.3  301.12  4659.0  300.62
  4662.3  301.12  5424.6  301.12  5455.1  304.21  5597.7  312.29  5623.9  315.14
  5675.6  316.71  5689.4  315.73  5727.3  317.16  5732.3  316.36  5778.9  318.39
  5784.0  317.34  5801.5  319.58  5856.1  321.73  5939.0  324.44  5970.8  323.90
#Mann=4,-1,0
  4004.9    0.05       0  4656.3   0.033       0  4662.3    0.05       0
  5856.1    0.16       0
Bank Sta=4656.3,4662.3
Exp/Cntr=0.3,0.1

Type RM Length L Ch R = 1,3479,701,701,701
BEGIN DESCRIPTION:
UNT 0481 IN LACR 6.0
END DESCRIPTION:
XS GIS Cut Line= 3
      3708539.14     10648313.86      3708029.46     10648989.84
      3707205.84     10650813.81
#Sta/Elev= 30
  4051.4  323.42  4097.7  321.49  4141.4  321.49  4147.6  320.41  4170.5  320.85
  4176.8  319.90  4191.3  321.09  4226.7  320.12  4305.8  320.74  4384.9  318.18
  4391.2  317.13  4405.7  317.60  4441.1  314.94  4455.7  315.42  4520.2  312.60
  4605.6  305.96  4611.9  304.37  4620.2  304.67  4667.1  301.12  4669.9  300.62
  4673.1  301.12  5419.8  301.12  5587.1  317.01  5622.6  319.46  5985.0  325.91
  6017.6  326.84  6090.8  328.03  6636.2  342.86  6734.2  343.31  6899.3  341.53
#Mann=6,-1,0
  4051.4    0.05       0  4667.1   0.033       0  4673.1    0.05       0
  5985.0     0.1       0  6017.6    0.16       0  6090.8    0.05       0
Bank Sta=4667.1,4673.1
Exp/Cntr=0.3,0.1

Type RM Length L Ch R = 1,2778,295,295,295
BEGIN DESCRIPTION:
UNT 0481 IN LACR 5.0
END DESCRIPTION:
XS GIS Cut Line= 4
      3708446.10     10648203.39      3707539.87     10648541.92
      3706993.00     10648953.38      3705976.62     10650022.21
#Sta/Elev= 30
  4236.6  318.76  4496.7  305.51  4548.9  301.12  4551.7  300.62  4554.9  301.12
  5459.9  301.12  5639.0  316.71  5659.8  316.56  5674.4  318.88  5709.8  319.20
  5724.4  321.14  5759.8  321.03  5774.3  323.35  5795.2  323.11  5803.5  324.69
  5916.8  321.80  5987.5  323.22  6093.5  319.65  6214.0  318.77  6263.4  319.22
  6277.6  321.17  6348.3  324.26  6560.3  329.79  6871.7  330.83  6892.8  332.62
  7139.2  331.83  7218.4  332.46  7239.4  334.02  7246.7  332.73  7363.3  333.40
#Mann=4,-1,0
  4236.6    0.05       0  4548.9   0.033       0  4554.9    0.05       0
  7139.2    0.12       0
Bank Sta=4548.9,4554.9
Exp/Cntr=0.3,0.1

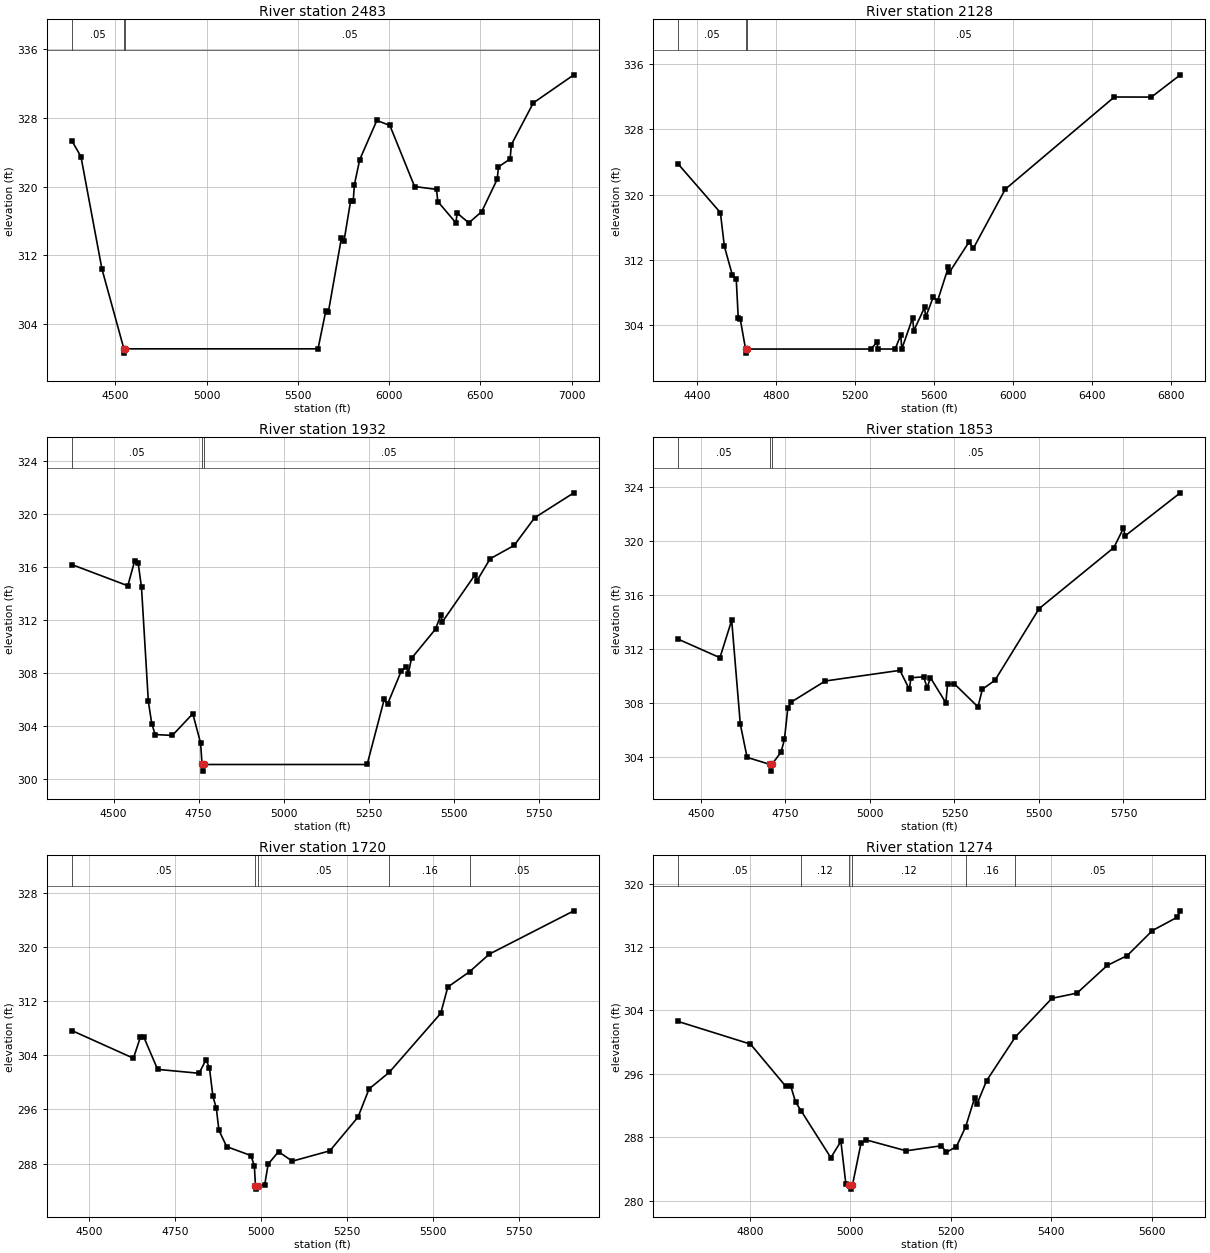
Type RM Length L Ch R = 1,2483,355,355,355
BEGIN DESCRIPTION:
UNT 0481 IN LACR 4.0
END DESCRIPTION:
XS GIS Cut Line= 4
      3708440.01     10648002.49      3707486.50     10648233.23
      3706966.96     10648942.96      3706330.59     10649565.02
#Sta/Elev= 30
  4261.9  325.38  4312.2  323.51  4426.9  310.45  4547.4  301.12  4550.1  300.62
  4553.4  301.12  5610.9  301.12  5653.4  305.53  5668.0  305.45  5739.1  314.03
  5753.7  313.73  5789.3  318.33  5803.9  318.37  5810.1  320.24  5839.4  323.16
  5933.2  327.73  6004.6  327.14  6139.9  320.03  6260.0  319.69  6267.2  318.28
  6366.2  315.80  6373.2  316.94  6436.9  315.79  6507.6  317.10  6592.5  320.87
  6599.5  322.32  6663.2  323.24  6670.2  324.91  6790.4  329.77  7012.4  333.04
#Mann=3,-1,0
  4261.9    0.05       0  4547.4   0.033       0  4553.4    0.05       0
Bank Sta=4547.4,4553.4
Exp/Cntr=0.3,0.1

Type RM Length L Ch R = 1,2128,196,196,196
BEGIN DESCRIPTION:
Mapping XS 61f2514e
END DESCRIPTION:
XS GIS Cut Line= 3
      3708422.61     10647768.12      3707519.84     10647837.57
      3705905.26     10648111.00
#Sta/Elev= 30
  4303.4  323.73  4517.0  317.79  4537.1  313.67  4577.2  310.19  4597.3  309.63
  4607.3  304.94  4617.3  304.81  4644.4  301.12  4647.2  300.62  4650.4  301.12
  5280.1  301.12  5309.9  301.96  5315.0  301.12  5401.8  301.12  5430.6  302.82
  5435.7  301.12  5491.0  304.95  5496.1  303.35  5551.4  306.21  5556.4  304.99
  5594.5  307.45  5616.8  307.00  5672.1  311.16  5677.2  310.51  5777.0  314.23
  5797.9  313.42  5959.6  320.65  6512.2  331.93  6700.0  331.92  6846.4  334.64
#Mann=3,-1,0
  4303.4    0.05       0  4644.4   0.033       0  4650.4    0.05       0
Bank Sta=4644.4,4650.4
Exp/Cntr=0.3,0.1

Type RM Length L Ch R = 1,1932,79,79,79
BEGIN DESCRIPTION:
UNT 0481 IN LACR 3.0
END DESCRIPTION:
XS GIS Cut Line= 2
      3708383.63     10647567.96      3706914.85     10647713.80
#Sta/Elev= 30
  4377.2  316.20  4542.0  314.60  4562.1  316.48  4572.2  316.35  4582.2  314.48
  4602.3  305.88  4612.4  304.19  4622.4  303.38  4672.7  303.31  4733.0  304.95
  4756.0  302.73  4760.1  301.12  4762.9  300.62  4766.1  301.12  5245.5  301.12
  5295.7  306.03  5305.8  305.69  5346.0  308.18  5361.1  308.49  5366.2  307.95
  5376.1  309.13  5446.5  311.33  5462.0  312.39  5467.0  311.89  5562.8  315.43
  5567.9  314.96  5607.2  316.64  5677.6  317.64  5737.9  319.73  5853.2  321.61
#Mann=3,-1,0
  4377.2    0.05       0  4760.1    0.03       0  4766.1    0.05       0
Bank Sta=4760.1,4766.1
Exp/Cntr=0.3,0.1

Type RM Length L Ch R = 1,1853,133,133,133
BEGIN DESCRIPTION:
UNT 0481 IN LACR 2.0
END DESCRIPTION:
XS GIS Cut Line= 2
      3708352.38     10647500.25      3706873.94     10647640.81
#Sta/Elev= 30
  4433.1  312.70  4556.4  311.33  4591.2  314.10  4616.7  306.40  4636.8  303.94
  4704.1  303.42  4706.8  302.92  4710.1  303.42  4737.2  304.33  4747.3  305.28
  4757.3  307.61  4767.4  308.04  4867.8  309.60  5088.8  310.39  5116.6  308.99
  5121.6  309.84  5159.1  309.91  5169.2  309.10  5179.2  309.84  5224.6  307.99
  5229.7  309.35  5249.5  309.40  5319.8  307.68  5332.7  308.99  5370.1  309.66
  5500.7  314.97  5721.7  319.49  5750.0  320.93  5755.0  320.36  5918.2  323.55
#Mann=3,-1,0
  4433.1    0.05       0  4704.1    0.03       0  4710.1    0.05       0
Bank Sta=4704.1,4710.1
Exp/Cntr=0.3,0.1

Type RM Length L Ch R = 1,1720,446,446,446
BEGIN DESCRIPTION:
Mapping XS 46383275
END DESCRIPTION:
XS GIS Cut Line= 2
      3708368.04     10647375.25      3706914.83     10647510.67
#Sta/Elev= 30
  4450.8  307.69  4630.0  303.59  4650.1  306.68  4660.1  306.73  4700.3  301.94
  4820.8  301.36  4840.9  303.35  4851.0  302.18  4861.0  297.98  4871.0  296.18
  4878.6  292.91  4901.2  290.50  4971.5  289.18  4981.5  287.68  4984.8  284.71
  4987.5  284.21  4990.8  284.71  5011.6  284.84  5021.7  287.91  5051.8  289.75
  5091.9  288.35  5201.0  289.88  5282.8  294.87  5315.1  299.05  5373.7  301.50
  5523.4  310.24  5543.9  314.13  5607.5  316.41  5664.5  319.00  5910.3  325.41
#Mann=5,-1,0
  4450.8    0.05       0  4984.8    0.03       0  4990.8    0.05       0
  5373.7    0.16       0  5607.5    0.05       0
Bank Sta=4984.8,4990.8
Exp/Cntr=0.3,0.1

Type RM Length L Ch R = 1,1274,0,0,0
BEGIN DESCRIPTION:
UNT 0481 IN LACR 1.0
END DESCRIPTION:
XS GIS Cut Line= 2
      3708253.39     10647104.42      3707254.02     10647088.80
#Sta/Elev= 30
  4657.3  302.61  4801.1  299.76  4871.1  294.46  4881.1  294.50  4891.1  292.43
  4901.6  291.38  4961.1  285.44  4981.1  287.50  4991.1  282.07  4998.1  281.98
  5000.9  281.48  5004.1  281.98  5021.1  287.24  5031.1  287.69  5111.1  286.31
  5181.1  286.95  5191.2  286.12  5211.2  286.85  5229.5  289.34  5247.2  292.95
  5252.2  292.23  5271.2  295.15  5328.4  300.66  5401.2  305.53  5451.2  306.19
  5511.2  309.67  5551.2  310.92  5601.2  314.07  5651.2  315.77  5656.8  316.56
#Mann=6,-1,0
  4657.3    0.05       0  4901.6    0.12       0  4998.1    0.07       0
  5004.1    0.12       0  5229.5    0.16       0  5328.4    0.05       0
Bank Sta=4998.1,5004.1
Exp/Cntr=0.3,0.1

Chan Stop Cuts=-1