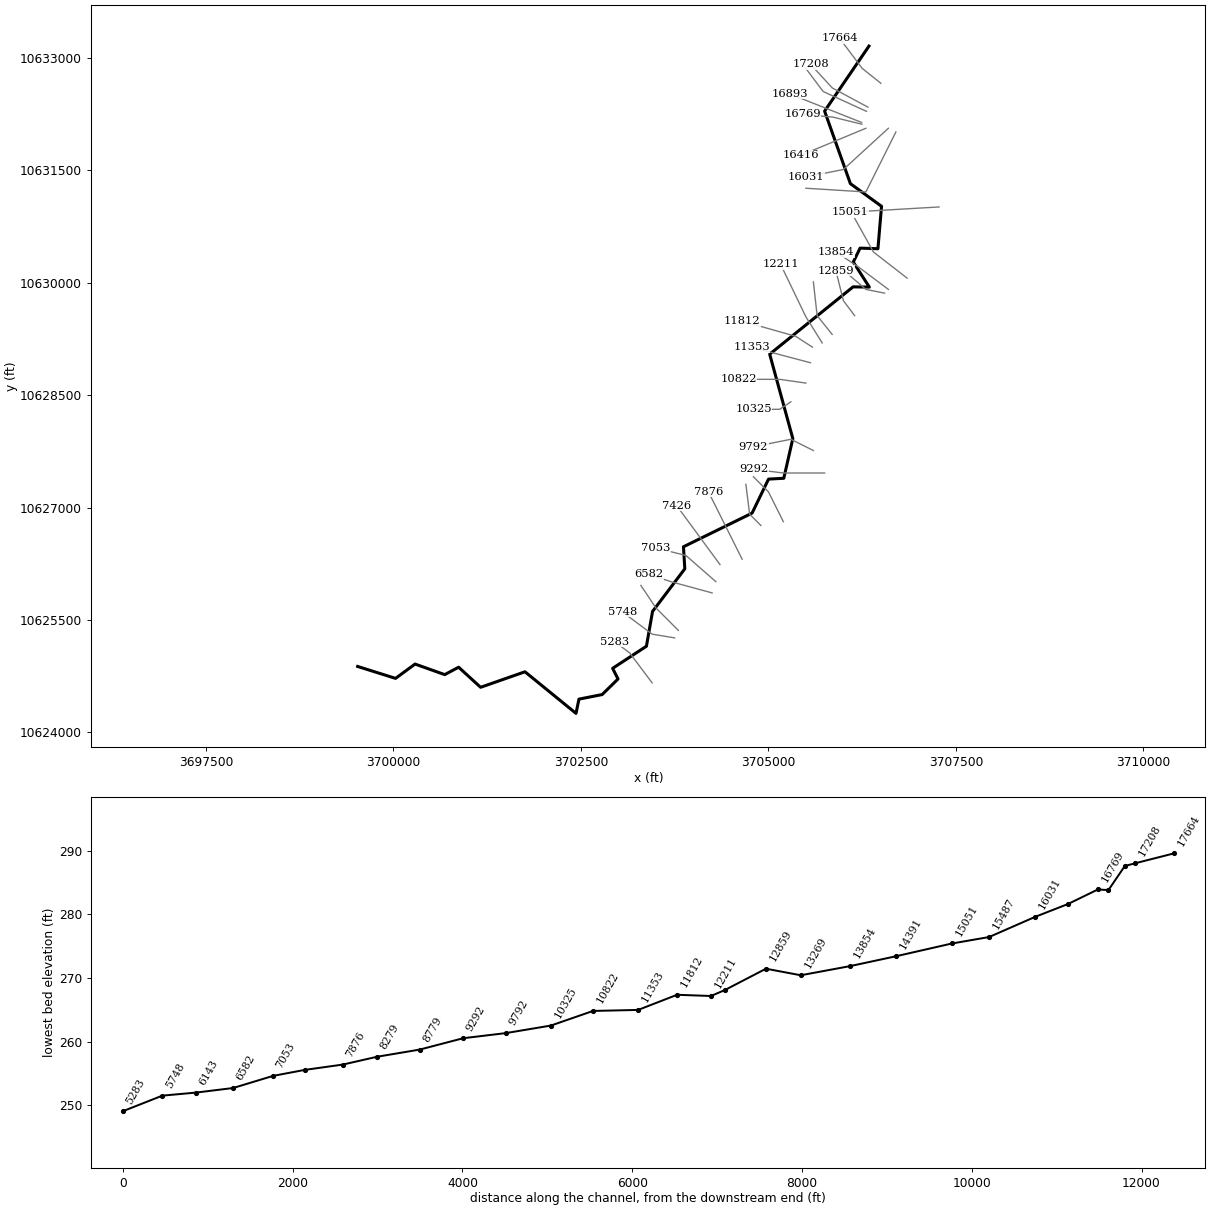
--- UNT 0482 IN LACR.prj (project) ---

Proj Title=UNT 0482 IN LACR Base Level Engineering
Current Plan=p01
Default Exp/Contr=0.3,0.1
English Units
Geom File=g01
Flow File=f01
Plan File=p01
Y Axis Title=Elevation
X Axis Title(PF)=Main Channel Distance
X Axis Title(XS)=Station
BEGIN DESCRIPTION:
UNT 0482 IN LACR
END DESCRIPTION:
DSS Export Rating Curves= 0
DSS Export Rating Curve Sorted= 0
DSS Export Volume Flow Curves= 0
DXF OffsetX= 0
DXF OffsetY= 0
DXF ScaleX= 1
DXF ScaleY= 10

--- UNT 0482 IN LACR.p01 (plan) ---

Plan Title=Multiple Run
Short Identifier=Multiple
Geom File=g01
Flow File=f01
Subcritical Flow
K Sum by GR= 0
Std Step Tol= 0.01
Critical Tol= 0.01
Num of Std Step Trials= 20
Max Error Tol= 0.3
Flow Tol Ratio= 0.001
Split Flow NTrial= 30
Split Flow Tol= 0.02
Split Flow Ratio= 0.02
Log Output Level= 0
Friction Slope Method= 1
Unsteady Friction Slope Method= 2
Unsteady Bridges Friction Slope Method= 1
Parabolic Critical Depth
Global Vel Dist=  1 , 1 , 1
Global Log Level= 0
CheckData=True
Encroach Param= -1, 0, 0, 0
BEGIN DESCRIPTION:
Multiple Run
END DESCRIPTION:

--- UNT 0482 IN LACR.f01 (steady flow) ---

Flow Title=Multiple
Number of Profiles=7
Profile Names=10-year,25-year,50-year,1pct_min,100-year,1pct_plu,500-year
River Rch & RM= UNT 0482 IN LACR,Reach-1,17664
     672     902    1090     966    1306    1767    1884
River Rch & RM= UNT 0482 IN LACR,Reach-1,7876
     794    1074    1302    1158    1566    2117    2273
Boundary for River Rch & Prof#=UNT 0482 IN LACR,Reach-1,1
Up Type=0
Dn Type=3
Dn Slope=0.005
Boundary for River Rch & Prof#=UNT 0482 IN LACR,Reach-1,2
Up Type=0
Dn Type=3
Dn Slope=0.005
Boundary for River Rch & Prof#=UNT 0482 IN LACR,Reach-1,3
Up Type=0
Dn Type=3
Dn Slope=0.005
Boundary for River Rch & Prof#=UNT 0482 IN LACR,Reach-1,4
Up Type=0
Dn Type=3
Dn Slope=0.005
Boundary for River Rch & Prof#=UNT 0482 IN LACR,Reach-1,5
Up Type=0
Dn Type=3
Dn Slope=0.005
Boundary for River Rch & Prof#=UNT 0482 IN LACR,Reach-1,6
Up Type=0
Dn Type=3
Dn Slope=0.005
Boundary for River Rch & Prof#=UNT 0482 IN LACR,Reach-1,7
Up Type=0
Dn Type=3
Dn Slope=0.005

--- UNT 0482 IN LACR.g01 (geometry) ---

Geom Title=Existing Conditions
Program Version=4.10

River Reach=UNT 0482 IN LACR,Reach-1
Reach XY= 30
        3706341.       10633157.      3705749.25       10632289.
      3706093.25       10631321.      3706508.25       10631019.
      3706460.25       10630453.       3706222.5       10630461.
       3706131.5       10630275.      3706345.75       10629941.
      3706128.75       10629944.        3705017.       10629046.
       3705325.5       10627920.        3705205.       10627390.
      3705001.75       10627379.      3704782.25       10626925.
      3703867.25       10626476.      3703885.25       10626182.
        3703455.       10625613.       3703373.5       10625149.
      3702922.75       10624854.      3702994.75       10624712.
        3702783.       10624504.      3702473.75       10624443.
       3702434.5       10624253.        3701754.       10624808.
      3701162.25       10624601.      3700869.25       10624869.
        3700684.       10624770.      3700288.25       10624911.
      3700028.25       10624720.        3699523.       10624879.

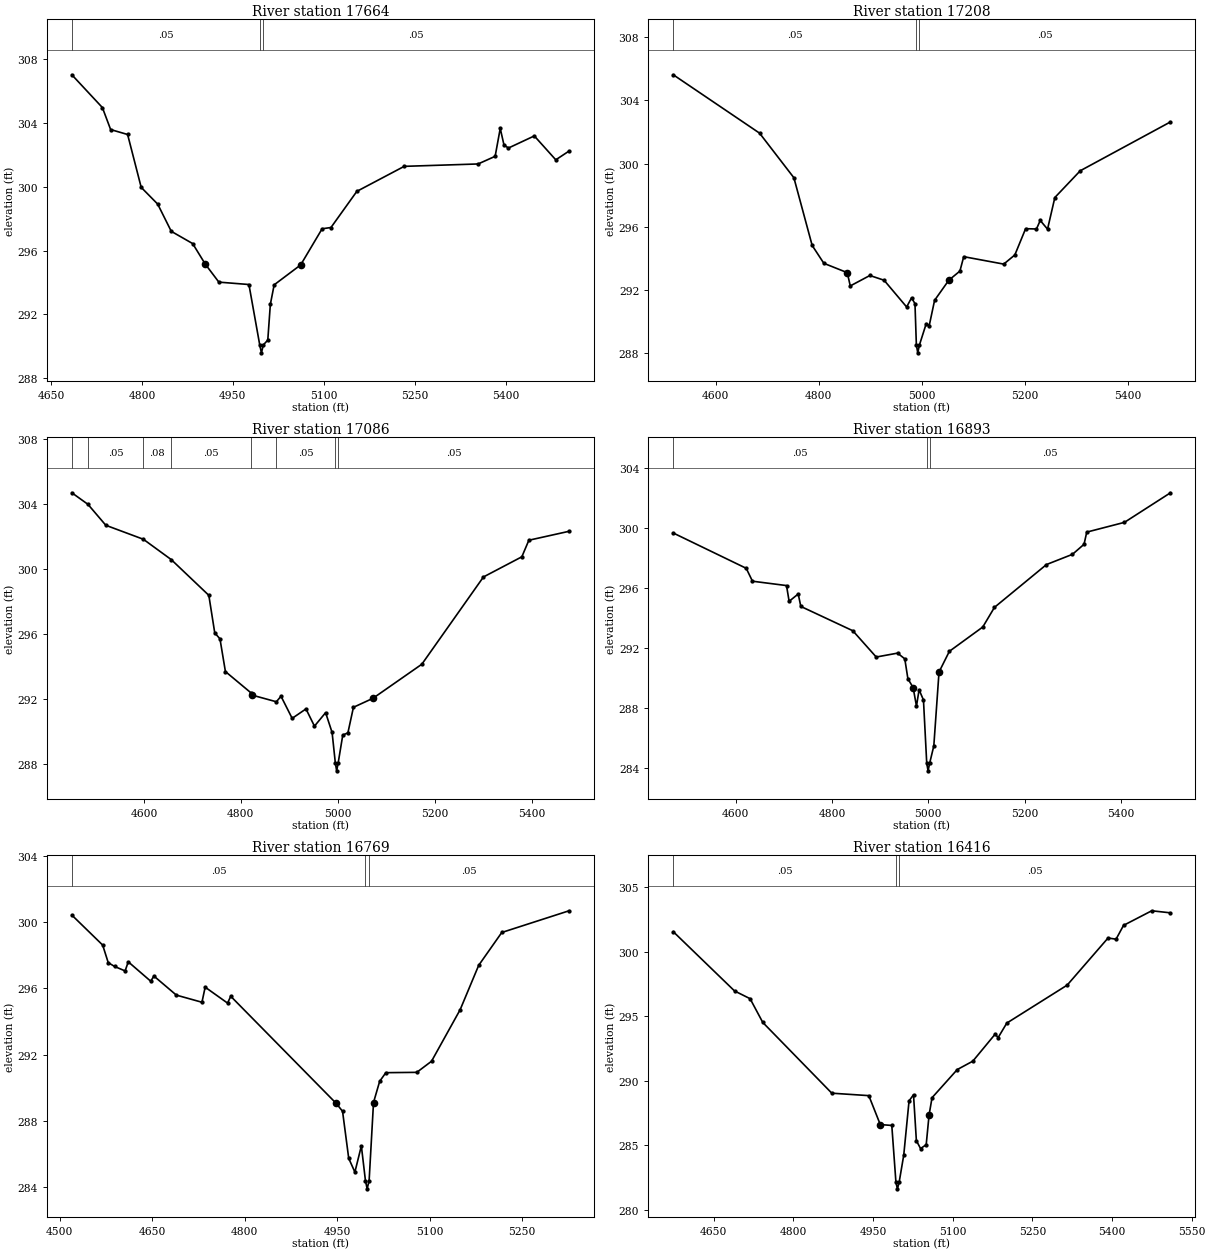
Type RM Length L Ch R = 1 ,17664   ,456,456,456
BEGIN DESCRIPTION:
UNT 0482 IN LACR 36.0
END DESCRIPTION:
XS GIS Cut Line= 3
      3706499.57     10632660.22      3706249.61     10632860.19
      3705949.61     10633260.18
#Sta/Elev= 30
  4684.4  307.04  4734.8  304.98  4748.4   303.6  4776.4  303.29  4798.8  299.97
    4826  298.92  4848.4  297.21  4883.7  296.44  4904.5  295.15  4926.9  294.02
  4976.5  293.87  4994.3  290.08  4997.1  289.58  5000.3  290.08  5007.6  290.38
  5011.8  292.62  5018.1  293.85  5061.8   295.1  5097.2  297.37  5111.8  297.45
  5154.5  299.72  5232.6  301.29  5354.5  301.44  5382.6  301.92    5391  303.67
  5397.2  302.63  5404.5  302.44  5447.2   303.2  5482.6   301.7  5504.5  302.25
#Mann= 3 ,-1 , 0
  4684.4     .05       0  4994.3     .03       0  5000.3     .05       0
Bank Sta=4904.5,5061.8
XS Rating Curve= 0 ,0
Exp/Cntr=0.3,0.1

Type RM Length L Ch R = 1 ,17208   ,122,122,122
BEGIN DESCRIPTION:
Mapping XS 3494b5c3
END DESCRIPTION:
XS GIS Cut Line= 3
      3706327.13     10632342.04      3705851.87     10632598.12
      3705563.96     10632912.01
#Sta/Elev= 30
  4517.6  305.61  4685.2  301.92  4751.9   299.1  4787.4  294.82  4810.1  293.69
  4855.6   293.1  4861.4  292.26  4899.5  292.92  4927.1  292.62  4970.9  290.93
  4980.5  291.51  4987.1  291.14  4989.8  288.53  4992.5  288.03  4995.8  288.53
    5009  289.88  5014.7  289.74  5025.2  291.35  5052.8  292.62  5074.4   293.2
  5081.8  294.11  5159.5  293.64  5181.1  294.22    5202  295.88  5223.1  295.86
  5230.4   296.4  5244.6  295.85  5258.8  297.85  5308.1  299.54  5483.4  302.63
#Mann= 3 ,-1 , 0
  4517.6     .05       0  4989.8     .03       0  4995.8     .05       0
Bank Sta=4855.6,5052.8
XS Rating Curve= 0 ,0
Exp/Cntr=0.3,0.1

Type RM Length L Ch R = 1 ,17086   ,193,193,193
BEGIN DESCRIPTION:
UNT 0482 IN LACR 35.0
END DESCRIPTION:
XS GIS Cut Line= 3
      3706307.59     10632285.63      3705730.34     10632550.38
      3705495.96     10632862.89
#Sta/Elev= 30
  4451.3  304.71  4484.5     304  4521.4  302.71  4598.8  301.85  4656.3   300.6
  4733.9   298.4  4746.1  296.09  4756.9  295.72  4768.1  293.71  4820.4  292.41
  4823.1  292.26  4873.2  291.85  4882.8  292.19  4905.8  290.83  4934.3  291.41
  4951.8  290.35  4974.8  291.18  4988.2  289.96  4994.8   288.1  4997.6   287.6
  5000.8   288.1  5010.2   289.8  5020.8  289.94  5032.2  291.51  5072.3  292.06
  5173.3  294.16  5300.4  299.53  5379.6  300.77  5394.1  301.79    5477  302.34
#Mann= 8 ,-1 , 0
  4451.3     .08       0  4484.5     .05       0  4598.8     .08       0
  4656.3     .05       0  4820.4     .08       0  4873.2     .05       0
  4994.8     .03       0  5000.8     .05       0
Bank Sta=4823.1,5072.3
XS Rating Curve= 0 ,0
Exp/Cntr=0.3,0.1

Type RM Length L Ch R = 1 ,16893   ,124,124,124
BEGIN DESCRIPTION:
UNT 0482 IN LACR 34.0
END DESCRIPTION:
XS GIS Cut Line= 2
      3706242.47     10632138.06      3705282.83     10632519.32
#Sta/Elev= 30
  4470.3  299.65  4621.8   297.3  4634.8  296.44  4705.5  296.15  4710.9   295.1
  4729.8  295.59  4735.2  294.76  4843.2  293.14  4891.8  291.39  4936.1  291.65
  4951.1  291.27  4957.6  289.94  4968.4  289.36  4975.4  288.12  4980.8  289.21
  4989.9  288.53  4996.7  284.31  4999.5  283.81  5002.7  284.31  5011.4  285.47
  5022.2  290.39  5043.7  291.77  5113.1  293.39  5137.4   294.7  5245.4  297.55
  5299.3  298.23  5323.4   298.9    5329  299.71  5407.3  300.36  5502.9  302.33
#Mann= 3 ,-1 , 0
  4470.3     .05       0  4996.7     .03       0  5002.7     .05       0
Bank Sta=4968.4,5022.2
XS Rating Curve= 0 ,0
Exp/Cntr=0.3,0.1

Type RM Length L Ch R = 1 ,16769   ,353,353,353
BEGIN DESCRIPTION:
Mapping XS c68bee2b
END DESCRIPTION:
XS GIS Cut Line= 3
      3706246.88     10632114.17      3705858.38     10632209.67
      3705453.62      10632244.3
#Sta/Elev= 30
  4519.5  300.43  4569.5  298.62  4578.5  297.56  4588.8  297.33  4605.9  297.06
    4611  297.61  4647.4  296.44  4652.6  296.75    4689   295.6  4730.5  295.17
  4735.7  296.08    4772  295.12  4777.2  295.53  4948.4  289.06  4958.5  288.59
  4968.5  285.75  4978.5  284.92    4989   286.5  4995.6  284.41  4998.4  283.91
  5001.6  284.41  5008.7  289.12  5018.7   290.4  5028.7  290.92  5078.9  290.94
  5102.8  291.61  5149.2  294.72  5179.3   297.4  5216.7  299.38  5325.8  300.69
#Mann= 3 ,-1 , 0
  4519.5     .05       0  4995.6     .03       0  5001.6     .05       0
Bank Sta=4948.4,5008.7
XS Rating Curve= 0 ,0
Exp/Cntr=0.3,0.1

Type RM Length L Ch R = 1 ,16416   ,385,385,385
BEGIN DESCRIPTION:
UNT 0482 IN LACR 33.0
END DESCRIPTION:
XS GIS Cut Line= 2
      3706299.62     10632060.19      3705434.99     10631700.42
#Sta/Elev= 30
  4573.6  301.54    4689  296.95  4718.3  296.35  4742.2  294.51  4872.2  289.03
  4941.9  288.84  4963.5   286.6  4985.2  286.53    4993  282.12  4995.8  281.62
    4999  282.12  5007.7  284.23  5017.7  288.43  5026.1  288.91  5031.5  285.35
  5039.4  284.74    5050  285.04  5055.4  287.34    5061  288.68  5108.5  290.86
  5137.8  291.51    5180  293.61  5185.4  293.33  5201.8  294.46  5315.5   297.4
  5392.5  301.05  5407.6  300.96  5421.7  302.03  5474.8  303.16  5510.1     303
#Mann= 3 ,-1 , 0
  4573.6     .05       0    4993     .03       0    4999     .05       0
Bank Sta=4963.5,5055.4
XS Rating Curve= 0 ,0
Exp/Cntr=0.3,0.1

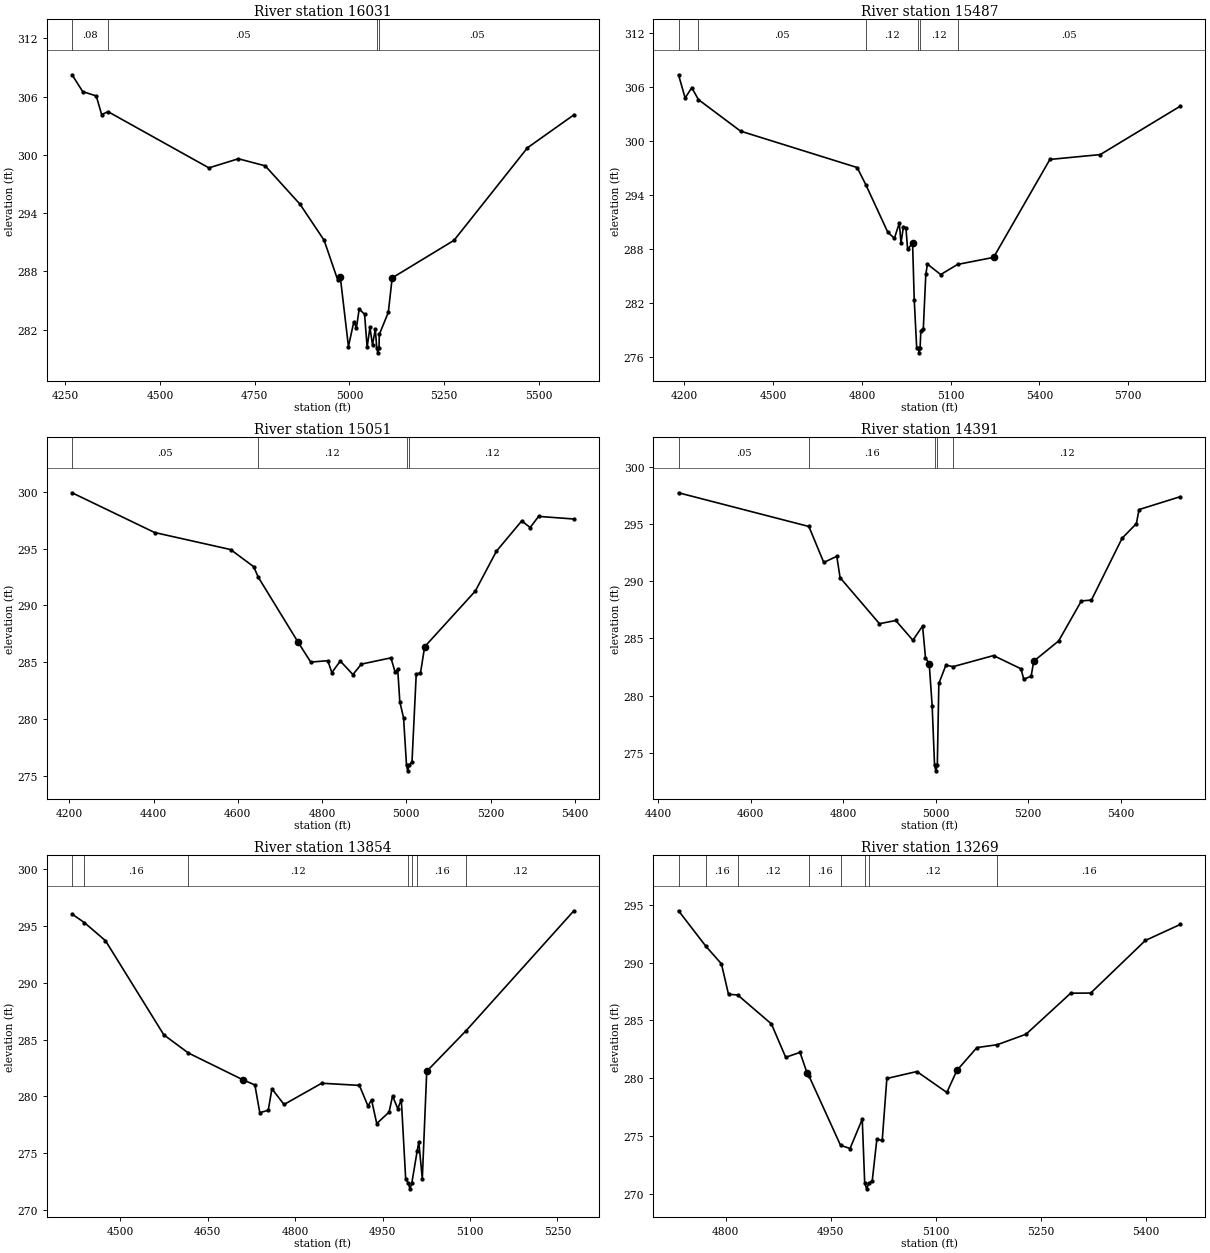
Type RM Length L Ch R = 1 ,16031   ,544,544,544
BEGIN DESCRIPTION:
UNT 0482 IN LACR 32.0
END DESCRIPTION:
XS GIS Cut Line= 3
      3706599.58     10632060.16      3705999.61     10631510.19
      3705499.61     10631410.19
#Sta/Elev= 30
  4268.3  308.25  4296.3  306.52  4332.1  306.07  4346.3  304.15  4363.2  304.45
  4629.3  298.66    4707   299.6  4777.9  298.87  4869.8  294.91  4933.3   291.2
    4969  287.13  4975.8  287.46  4997.4  280.26  5011.6  282.81  5018.4  282.17
  5025.8  284.12    5040  283.58  5046.7  280.19  5054.1  282.22  5060.9  280.43
  5068.3  282.05  5072.1  280.11  5074.9  279.61  5078.1  280.11  5078.8   281.5
  5102.6  283.78  5112.8  287.33    5276   291.2  5469.7  300.73  5592.1  304.12
#Mann= 4 ,-1 , 0
  4268.3     .08       0  4363.2     .05       0  5072.1     .03       0
  5078.1     .05       0
Bank Sta=4975.8,5112.8
XS Rating Curve= 0 ,0
Exp/Cntr=0.3,0.1

Type RM Length L Ch R = 1 ,15487   ,436,436,436
BEGIN DESCRIPTION:
UNT 0482 IN LACR 31.0
END DESCRIPTION:
XS GIS Cut Line= 3
      3706699.59     10632010.15      3706299.61     10631210.19
      3705499.66     10631260.19
#Sta/Elev= 30
  4180.3  307.37  4202.6  304.78    4225  305.94  4247.4  304.61  4389.9   301.1
    4784  297.05  4813.5  295.12  4887.4  289.86  4909.8  289.17  4926.5  290.88
  4932.1  288.65  4940.5  290.48  4948.9  290.32  4954.5  287.94  4971.3  288.65
  4976.9  282.33  4985.2  276.98  4990.6  276.93  4993.4  276.43  4996.6  276.93
  4999.2   278.9  5007.6  279.13    5016  285.17  5021.6   286.3  5066.3  285.14
  5123.6  286.27    5245  287.05  5435.4  297.95  5605.7  298.49  5876.2  303.88
#Mann= 6 ,-1 , 0
  4180.3     .08       0  4247.4     .05       0  4813.5     .12       0
  4990.6     .07       0  4996.6     .12       0  5123.6     .05       0
Bank Sta=4971.3,5245
XS Rating Curve= 0 ,0
Exp/Cntr=0.3,0.1

Type RM Length L Ch R = 1 ,15051   ,660,660,660
BEGIN DESCRIPTION:
UNT 0482 IN LACR 30.0
END DESCRIPTION:
XS GIS Cut Line= 2
      3707275.28     10631010.32      3706086.01     10630940.87
#Sta/Elev= 30
  4206.5  299.91  4402.5  296.41  4582.8  294.91  4637.7   293.4  4648.3  292.49
  4743.1  286.75  4773.1     285  4813.7  285.12  4823.2  284.07  4843.3  285.09
  4873.3   283.9  4893.3  284.82  4963.5  285.37  4973.5  284.11  4979.6  284.37
  4984.6  281.51  4993.5  280.08  5000.5  275.92  5003.3  275.42  5006.5  275.92
  5013.5  276.19  5023.6  283.96  5033.6  284.02  5043.6  286.35  5163.8  291.25
  5213.9  294.76    5274  297.43    5294  296.85  5314.1  297.83  5397.8   297.6
#Mann= 4 ,-1 , 0
  4206.5     .05       0  4648.3     .12       0  5000.5     .07       0
  5006.5     .12       0
Bank Sta=4743.1,5043.6
XS Rating Curve= 0 ,0
Exp/Cntr=0.3,0.1

Type RM Length L Ch R = 1 ,14391   ,537,537,537
BEGIN DESCRIPTION:
UNT 0482 IN LACR 29.0
END DESCRIPTION:
XS GIS Cut Line= 3
      3706849.61     10630060.19      3706399.61     10630410.19
      3706149.59     10630860.22
#Sta/Elev= 30
  4444.1  297.75  4725.9   294.8  4758.1  291.65  4786.2  292.19  4793.4  290.32
  4878.5  286.29  4913.7  286.57  4950.8  284.84  4971.7  286.09    4978  283.33
  4986.1  282.77  4992.5  279.07  4997.6  273.91  5000.4  273.41  5003.6  273.91
  5006.9  281.06  5022.2  282.66  5037.7  282.53  5125.1   283.5  5184.6  282.34
  5190.4  281.43  5206.4  281.69  5212.1  283.01  5265.9  284.78    5315  288.28
  5336.8  288.36  5403.1  293.77    5434  295.05  5439.7  296.28    5529  297.41
#Mann= 5 ,-1 , 0
  4444.1     .05       0  4725.9     .16       0  4997.6     .07       0
  5003.6     .16       0  5037.7     .12       0
Bank Sta=4986.1,5212.1
XS Rating Curve= 0 ,0
Exp/Cntr=0.3,0.1

Type RM Length L Ch R = 1 ,13854   ,585,585,585
BEGIN DESCRIPTION:
UNT 0482 IN LACR 28.0
END DESCRIPTION:
XS GIS Cut Line= 3
       3706599.6     10629910.19      3706199.61     10630210.19
      3705899.65     10630410.16
#Sta/Elev= 30
  4417.6  296.04  4438.7  295.29  4474.9   293.7  4574.9  285.42    4617  283.82
  4710.3  281.47  4731.1  281.01  4739.5  278.57    4754  278.78  4760.3  280.67
  4781.1  279.29  4845.7  281.16  4910.3  280.97  4925.1  279.15  4931.1   279.7
  4940.1  277.61  4961.2  278.62  4967.2  280.04  4976.2  278.92  4982.2  279.72
  4989.7  272.73  4994.2  272.37    4997  271.87  5000.2  272.37  5009.3  275.17
  5012.2     276  5018.2  272.74  5025.8  282.21  5093.1  285.77  5278.1  296.33
#Mann= 7 ,-1 , 0
  4417.6     .05       0  4438.7     .16       0    4617     .12       0
  4994.2     .07       0  5000.2     .12       0  5009.3     .16       0
  5093.1     .12       0
Bank Sta=4710.3,5025.8
XS Rating Curve= 0 ,0
Exp/Cntr=0.3,0.1

Type RM Length L Ch R = 1 ,13269   ,410,410,410
BEGIN DESCRIPTION:
UNT 0482 IN LACR 27.0
END DESCRIPTION:
XS GIS Cut Line= 3
      3706549.57      10629860.2      3706299.61     10629910.19
       3705949.6     10630210.19
#Sta/Elev= 30
  4732.8  294.48  4771.8  291.41    4794  289.89  4804.1  287.25  4817.1   287.2
  4865.3  284.69  4885.7   281.8  4906.1  282.23  4916.3  280.42  4918.8   280.2
  4963.9  274.19  4977.5  273.91  4994.9  276.45  4998.4  270.92  5001.2  270.42
  5004.4  270.92  5009.1  271.08  5015.7  274.69  5023.4  274.62    5030  279.97
  5072.8  280.57  5115.6  278.76  5129.9  280.66  5158.4  282.64  5187.5  282.89
  5228.6   283.8  5292.3  287.35  5320.8  287.36  5398.8  291.91  5448.7   293.3
#Mann= 8 ,-1 , 0
  4732.8     .05       0  4771.8     .16       0  4817.1     .12       0
  4918.8     .16       0  4963.9     .12       0  4998.4     .07       0
  5004.4     .12       0  5187.5     .16       0
Bank Sta=4916.3,5129.9
XS Rating Curve= 0 ,0
Exp/Cntr=0.3,0.1

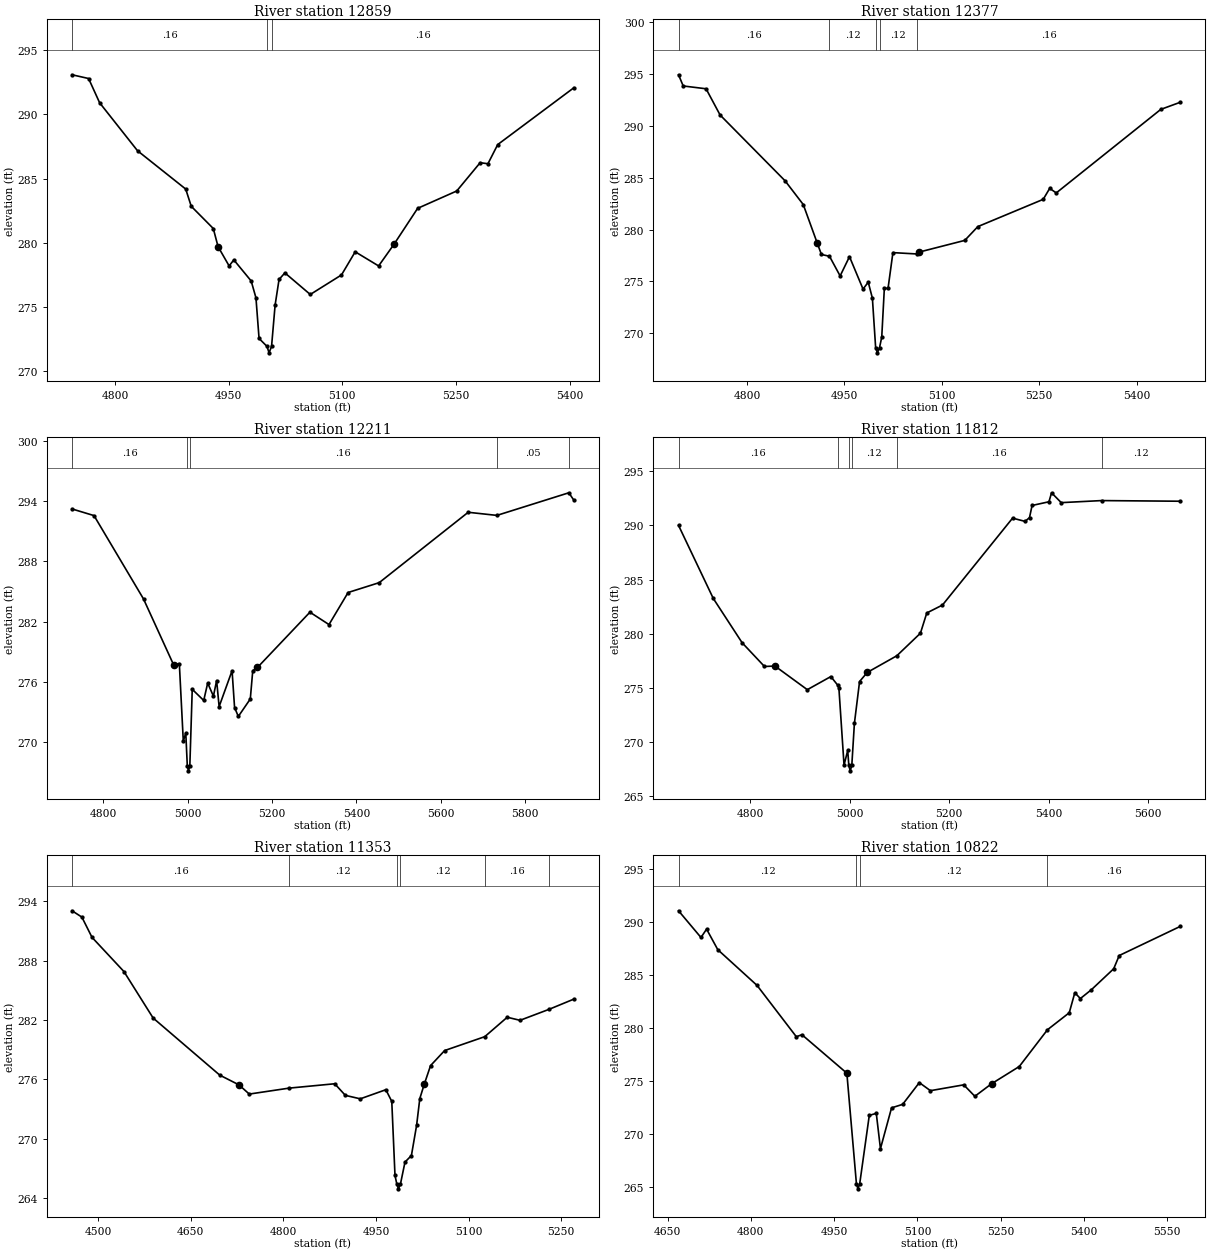
Type RM Length L Ch R = 1 ,12859   ,482,482,482
BEGIN DESCRIPTION:
UNT 0482 IN LACR 26.0
END DESCRIPTION:
XS GIS Cut Line= 3
      3706149.59     10629560.21      3705999.61     10629760.19
       3705899.6     10630160.21
#Sta/Elev= 30
  4743.4  293.08  4765.2  292.79  4779.8   290.9  4829.8  287.17  4893.4  284.19
  4900.7  282.85  4929.8  281.12  4936.1  279.71  4950.7  278.21  4956.9  278.68
  4979.8  277.04  4986.1  275.73  4990.2  272.57  5000.7  271.95  5003.4  271.45
  5006.7  271.95  5011.4  275.17  5016.6  277.16  5024.3  277.67  5057.8  275.99
    5099  277.51  5117.1  279.31    5148  278.21  5168.6  279.92  5199.5  282.69
  5251.1  284.04    5282  286.24  5292.3  286.16  5305.2  287.65  5405.7  292.07
#Mann= 3 ,-1 , 0
  4743.4     .16       0  5000.7     .07       0  5006.7     .16       0
Bank Sta=4936.1,5168.6
XS Rating Curve= 0 ,0
Exp/Cntr=0.3,0.1

Type RM Length L Ch R = 1 ,12377   ,166,166,166
BEGIN DESCRIPTION:
UNT 0482 IN LACR 25.0
END DESCRIPTION:
XS GIS Cut Line= 3
      3705849.62     10629310.17      3705649.61     10629560.19
      3705599.61     10630010.15
#Sta/Elev= 30
  4694.6  294.94  4701.8  293.86    4737  293.59  4758.6  291.06  4858.7  284.71
  4886.7  282.42  4908.3  278.69  4914.7   277.6  4927.1  277.43  4943.5  275.53
  4957.9  277.39  4978.8  274.26  4986.8  274.93  4993.2  273.38  4998.2  268.61
  5000.9  268.11  5004.2  268.61  5007.6  269.63  5011.6  274.33  5017.3  274.33
  5024.8  277.78  5061.7  277.65  5065.1  277.83  5135.5  278.96  5155.6  280.29
  5256.3  282.92  5266.3  283.98  5276.4  283.54  5437.4   291.6  5467.5  292.29
#Mann= 5 ,-1 , 0
  4694.6     .16       0  4927.1     .12       0  4998.2     .07       0
  5004.2     .12       0  5061.7     .16       0
Bank Sta=4908.3,5065.1
XS Rating Curve= 0 ,0
Exp/Cntr=0.3,0.1

Type RM Length L Ch R = 1 ,12211   ,399,399,399
BEGIN DESCRIPTION:
Mapping XS c8ed90b9
END DESCRIPTION:
XS GIS Cut Line= 3
       3705717.1     10629196.07      3705500.09      10629543.3
      3705161.82     10630245.84
#Sta/Elev= 30
    4726  293.21    4778  292.55  4895.3  284.26  4966.7   277.7  4980.2  277.83
  4989.6  270.12  4995.5  270.92  4999.1  267.66  5001.8  267.16  5005.1  267.66
  5010.8  275.27    5038  274.16  5047.4  275.89    5061  274.59  5068.6  276.14
  5074.5  273.55  5105.2  277.12  5111.1  273.46    5120  272.57  5148.4  274.31
  5154.2  277.12  5165.3  277.44  5289.7  282.94  5334.9  281.71  5380.2   284.9
  5453.9  285.88  5664.8  292.88  5732.8  292.57  5903.3  294.82  5915.2  294.08
#Mann= 5 ,-1 , 0
    4726     .16       0  4999.1     .07       0  5005.1     .16       0
  5732.8     .05       0  5903.3     .12       0
Bank Sta=4966.7,5165.3
XS Rating Curve= 0 ,0
Exp/Cntr=0.3,0.1

Type RM Length L Ch R = 1 ,11812   ,459,459,459
BEGIN DESCRIPTION:
UNT 0482 IN LACR 24.0
END DESCRIPTION:
XS GIS Cut Line= 3
      3705586.91     10629139.64      3705362.51      10629284.7
      3704649.42     10629486.87
#Sta/Elev= 30
  4656.2     290    4726  283.26    4784  279.17  4828.9  276.98    4850  277.02
    4915  274.84  4962.3  276.05    4976  275.26  4978.4  275.03  4988.8  267.88
  4996.2  269.23  4998.4  267.85  5001.2  267.35  5004.4  267.85  5009.6  271.72
    5020  275.59  5035.4  276.43  5094.9  277.97  5142.3  280.05  5155.1  281.92
  5186.6  282.65  5327.5  290.67  5352.6  290.37  5361.5  290.72  5366.7  291.84
  5400.6  292.18  5405.8  293.01  5425.3   292.1  5506.2  292.29  5664.6  292.23
#Mann= 6 ,-1 , 0
  4656.2     .16       0    4976     .12       0  4998.4     .07       0
  5004.4     .12       0  5094.9     .16       0  5506.2     .12       0
Bank Sta=4850,5035.4
XS Rating Curve= 0 ,0
Exp/Cntr=0.3,0.1

Type RM Length L Ch R = 1 ,11353   ,531,531,531
BEGIN DESCRIPTION:
UNT 0482 IN LACR 23.0
END DESCRIPTION:
XS GIS Cut Line= 2
      3705560.84     10628931.33      3704775.29     10629139.65
#Sta/Elev= 30
  4457.8  293.02  4473.7  292.38  4490.1  290.34  4541.8  286.89  4589.1   282.2
    4697  276.44  4728.1  275.46  4744.8  274.53  4809.3  275.13  4883.2  275.57
  4900.4   274.4  4924.6  274.05    4966  274.97  4975.6  273.79  4980.8  266.32
  4983.7  265.47  4986.4  264.97  4989.7  265.47    4997  267.67  5007.4  268.33
  5015.8  271.37    5021  274.08  5028.1   275.5  5038.4   277.4  5061.2  278.92
  5126.2  280.32  5162.6  282.28  5183.3  281.97  5230.4  283.08  5270.5  284.11
#Mann= 6 ,-1 , 0
  4457.8     .16       0  4809.3     .12       0  4983.7     .07       0
  4989.7     .12       0  5126.2     .16       0  5230.4     .05       0
Bank Sta=4728.1,5028.1
XS Rating Curve= 0 ,0
Exp/Cntr=0.3,0.1

Type RM Length L Ch R = 1 ,10822   ,497,497,497
BEGIN DESCRIPTION:
UNT 0482 IN LACR 22.0
END DESCRIPTION:
XS GIS Cut Line= 3
      3705499.61     10628660.19      3705149.61     10628710.19
      3704599.57     10628710.19
#Sta/Elev= 30
  4669.8  291.04  4710.2  288.52  4720.3  289.31  4740.5  287.37  4811.2     284
  4881.9  279.16    4892  279.35  4972.9  275.72  4990.1  265.31  4992.8  264.81
  4996.1  265.31  5013.3  271.74  5025.9  271.93  5033.4   268.6  5053.4  272.45
  5073.4  272.78  5103.4  274.83  5123.4  274.07  5183.4  274.62  5203.4  273.54
  5233.4  274.72  5283.4  276.35  5334.2  279.82  5373.4  281.42  5383.4  283.31
  5393.4  282.76  5413.4   283.6  5453.4  285.57  5463.4  286.82  5573.4  289.57
#Mann= 4 ,-1 , 0
  4669.8     .12       0  4990.1     .07       0  4996.1     .12       0
  5334.2     .16       0
Bank Sta=4972.9,5233.4
XS Rating Curve= 0 ,0
Exp/Cntr=0.3,0.1

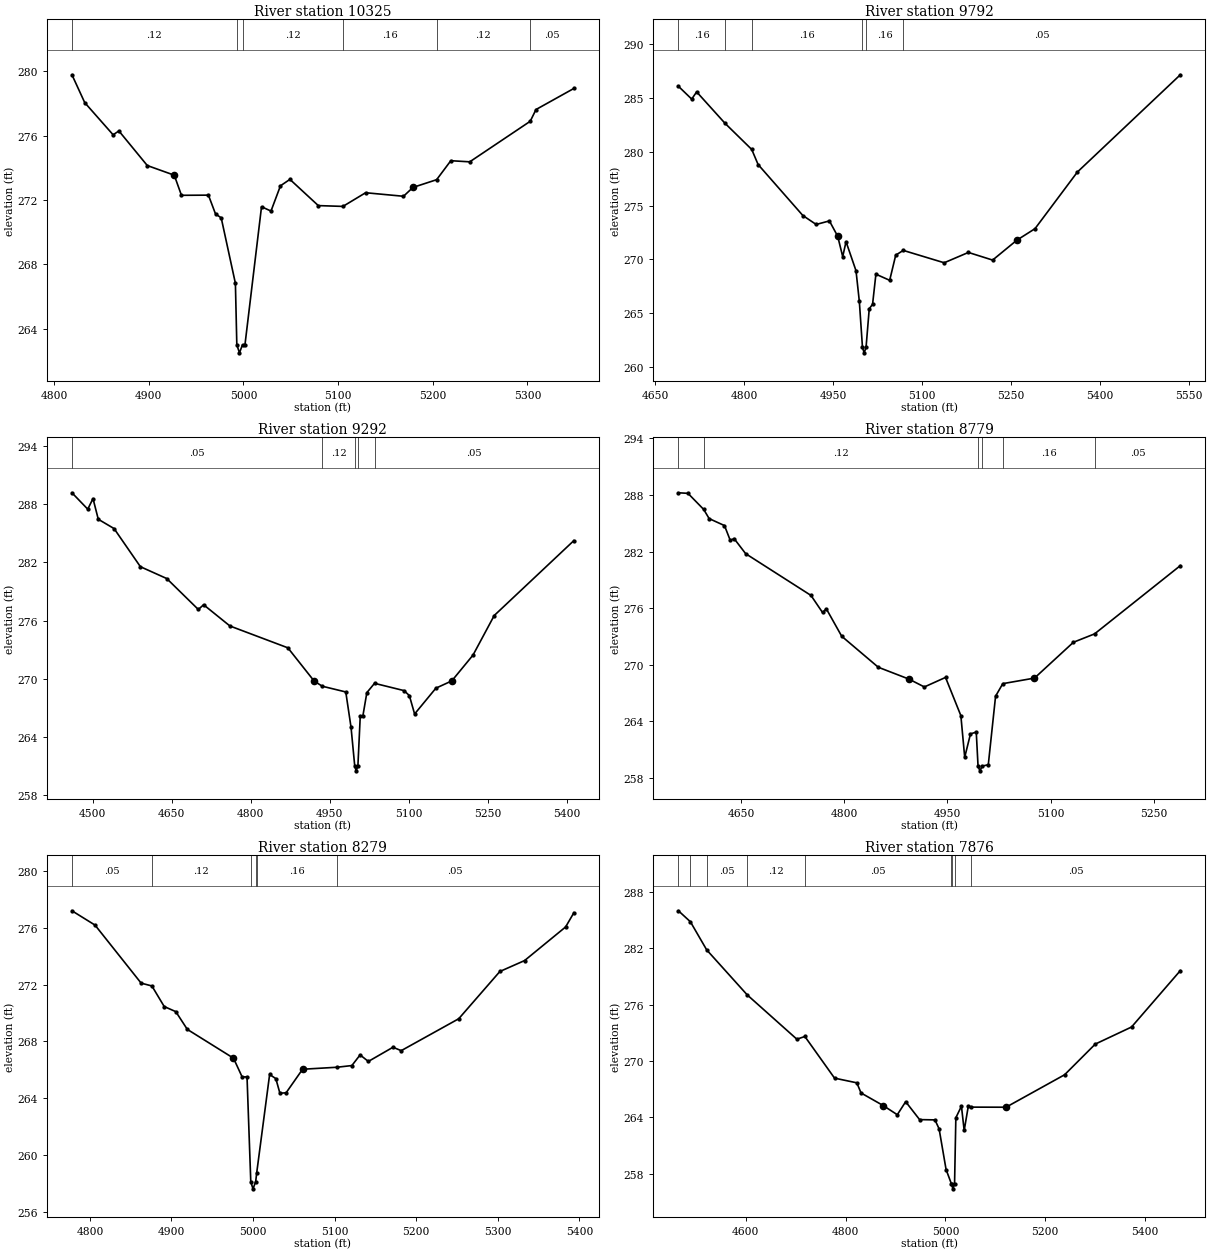
Type RM Length L Ch R = 1 ,10325   ,533,533,533
BEGIN DESCRIPTION:
UNT 0482 IN LACR 21.0
END DESCRIPTION:
XS GIS Cut Line= 3
      3705299.59     10628410.18      3705149.61     10628310.19
      3704799.56     10628310.19
#Sta/Elev= 30
  4818.8  279.79  4832.3  278.06  4862.3  276.06  4868.4   276.3  4898.4  274.15
  4926.9  273.55  4934.5   272.3    4963  272.31  4970.5  271.14  4976.5   270.9
  4991.5  266.83    4993  263.01  4995.8  262.51    4999  263.01  5001.6  263.01
  5019.1  271.59  5029.1  271.32  5039.1  272.89  5049.1  273.29  5079.1  271.66
  5105.1  271.61  5129.1  272.46  5169.1  272.24  5179.1  272.79  5204.1  273.27
  5219.1  274.45  5239.1  274.38    5303   276.9  5309.1  277.63  5349.1  278.94
#Mann= 6 ,-1 , 0
  4818.8     .12       0    4993     .07       0    4999     .12       0
  5105.1     .16       0  5204.1     .12       0    5303     .05       0
Bank Sta=4926.9,5179.1
XS Rating Curve= 0 ,0
Exp/Cntr=0.3,0.1

Type RM Length L Ch R = 1 ,9792    ,500,500,500
BEGIN DESCRIPTION:
UNT 0482 IN LACR 20.0
END DESCRIPTION:
XS GIS Cut Line= 3
       3705599.6     10627760.19      3705299.61     10627910.19
      3704799.61     10627810.19
#Sta/Elev= 30
  4689.5  286.09  4711.9   284.9  4720.2  285.57    4768  282.65    4813  280.22
  4823.7  278.82  4899.1  274.08  4921.5  273.25  4943.8  273.58  4957.8  272.15
  4966.2  270.26  4971.8  271.65  4988.6  268.95  4994.2   266.1  4999.5  261.82
  5002.3  261.32  5005.5  261.82  5010.9  265.42  5016.5  265.83  5022.1  268.63
  5045.3  268.06  5055.5   270.4  5068.2  270.84  5137.1  269.69  5177.9  270.65
  5218.7  269.94  5259.5  271.79  5290.1  272.86  5361.4  278.12  5534.8  287.16
#Mann= 6 ,-1 , 0
  4689.5     .16       0    4768     .05       0    4813     .16       0
  4999.5     .07       0  5005.5     .16       0  5068.2     .05       0
Bank Sta=4957.8,5259.5
XS Rating Curve= 0 ,0
Exp/Cntr=0.3,0.1

Type RM Length L Ch R = 1 ,9292    ,513,513,513
BEGIN DESCRIPTION:
UNT 0482 IN LACR 19.0
END DESCRIPTION:
XS GIS Cut Line= 3
      3705749.57     10627460.19      3705199.61     10627460.19
      3704799.59     10627510.19
#Sta/Elev= 30
  4460.5  289.18  4490.5  287.49  4500.5  288.58  4510.5  286.45  4540.5  285.49
  4590.5  281.56  4640.5  280.34  4700.5  277.15  4710.5  277.64  4760.5  275.45
  4870.5   273.2  4920.5  269.77  4935.9  269.24  4980.5  268.65  4990.5     265
  4997.5  261.02  5000.2  260.52  5003.5  261.02    5008  266.19    5013  266.19
  5020.5  268.58  5035.1  269.54  5091.1  268.79  5101.2  268.28  5111.2  266.38
  5151.6  269.04  5181.8  269.79  5222.1  272.45  5262.4  276.53  5413.6  284.25
#Mann= 5 ,-1 , 0
  4460.5     .05       0  4935.9     .12       0  4997.5     .07       0
  5003.5     .12       0  5035.1     .05       0
Bank Sta=4920.5,5181.8
XS Rating Curve= 0 ,0
Exp/Cntr=0.3,0.1

Type RM Length L Ch R = 1 ,8779    ,500,500,500
BEGIN DESCRIPTION:
UNT 0482 IN LACR 18.0
END DESCRIPTION:
XS GIS Cut Line= 3
      3705199.59     10626810.22      3704999.61     10627210.19
      3704799.62     10627410.17
#Sta/Elev= 30
  4558.7  288.23  4572.6  288.17  4595.5  286.46  4603.4  285.49  4625.7  284.75
  4634.1  283.18  4639.7  283.37  4656.5  281.77  4751.5  277.34  4768.3  275.53
  4773.9  275.91  4796.2  273.01  4849.4  269.72  4894.1  268.46  4916.4  267.63
  4947.2  268.64  4969.5  264.59  4975.1  260.17  4983.5  262.65  4991.9  262.84
  4994.5  259.23  4997.2  258.73  5000.5  259.23  5009.4  259.38    5020  266.65
  5030.5  267.98  5076.6  268.57  5133.2  272.37    5164  273.26  5288.7   280.5
#Mann= 6 ,-1 , 0
  4558.7     .05       0  4595.5     .12       0  4994.5     .07       0
  5000.5     .12       0  5030.5     .16       0    5164     .05       0
Bank Sta=4894.1,5076.6
XS Rating Curve= 0 ,0
Exp/Cntr=0.3,0.1

Type RM Length L Ch R = 1 ,8279    ,403,403,403
BEGIN DESCRIPTION:
UNT 0482 IN LACR 17.0
END DESCRIPTION:
XS GIS Cut Line= 3
      3704899.59      10626760.2      3704749.61     10626910.19
      3704699.61     10627310.16
#Sta/Elev= 30
    4778  277.21  4806.3   276.2  4862.8  272.11    4876  271.91  4891.1  270.46
  4905.3   270.1  4919.4  268.85    4976  266.82  4986.6   265.5  4992.6   265.5
  4997.2  258.11  4999.9  257.61  5003.2  258.11  5004.4  258.71  5020.3  265.67
  5027.9  265.38  5032.9  264.35  5040.5  264.38  5060.7  266.04  5102.7  266.18
  5121.1   266.3  5131.2  267.05  5141.3  266.59  5171.5  267.59  5181.6  267.35
  5252.1   269.6  5302.5  272.93  5332.8   273.7  5383.1  276.07  5393.2  277.07
#Mann= 6 ,-1 , 0
    4778     .05       0    4876     .12       0  4997.2     .07       0
  5003.2     .12       0  5004.4     .16       0  5102.7     .05       0
Bank Sta=4976,5060.7
XS Rating Curve= 0 ,0
Exp/Cntr=0.3,0.1

Type RM Length L Ch R = 1 ,7876    ,450,450,450
BEGIN DESCRIPTION:
UNT 0482 IN LACR 16.0
END DESCRIPTION:
XS GIS Cut Line= 3
      3704649.59     10626310.23      3704399.61     10626810.19
       3704199.6      10627210.2
#Sta/Elev= 30
  4464.8  286.02  4488.8  284.85  4521.5  281.85  4602.8  277.05  4702.3  272.33
  4718.3  272.62  4777.8  268.18  4822.5  267.68  4830.9   266.6  4875.6  265.25
  4903.6  264.28  4920.4  265.67  4948.3  263.76  4979.1  263.73  4987.4  262.78
  5001.4  258.44  5011.9  256.94  5012.4  256.88  5015.1  256.38  5018.4  256.88
    5021  263.96  5032.2  265.19  5037.7   262.6  5046.1  265.24    5051  265.09
  5121.6  265.08    5239  268.54  5300.5  271.81  5373.2  273.63    5471  279.64
#Mann= 9 ,-1 , 0
  4464.8     .05       0  4488.8     .12       0  4521.5     .05       0
  4602.8     .12       0  4718.3     .05       0  5011.9     .12       0
  5012.4     .03       0  5018.4     .12       0    5051     .05       0
Bank Sta=4875.6,5121.6
XS Rating Curve= 0 ,0
Exp/Cntr=0.3,0.1

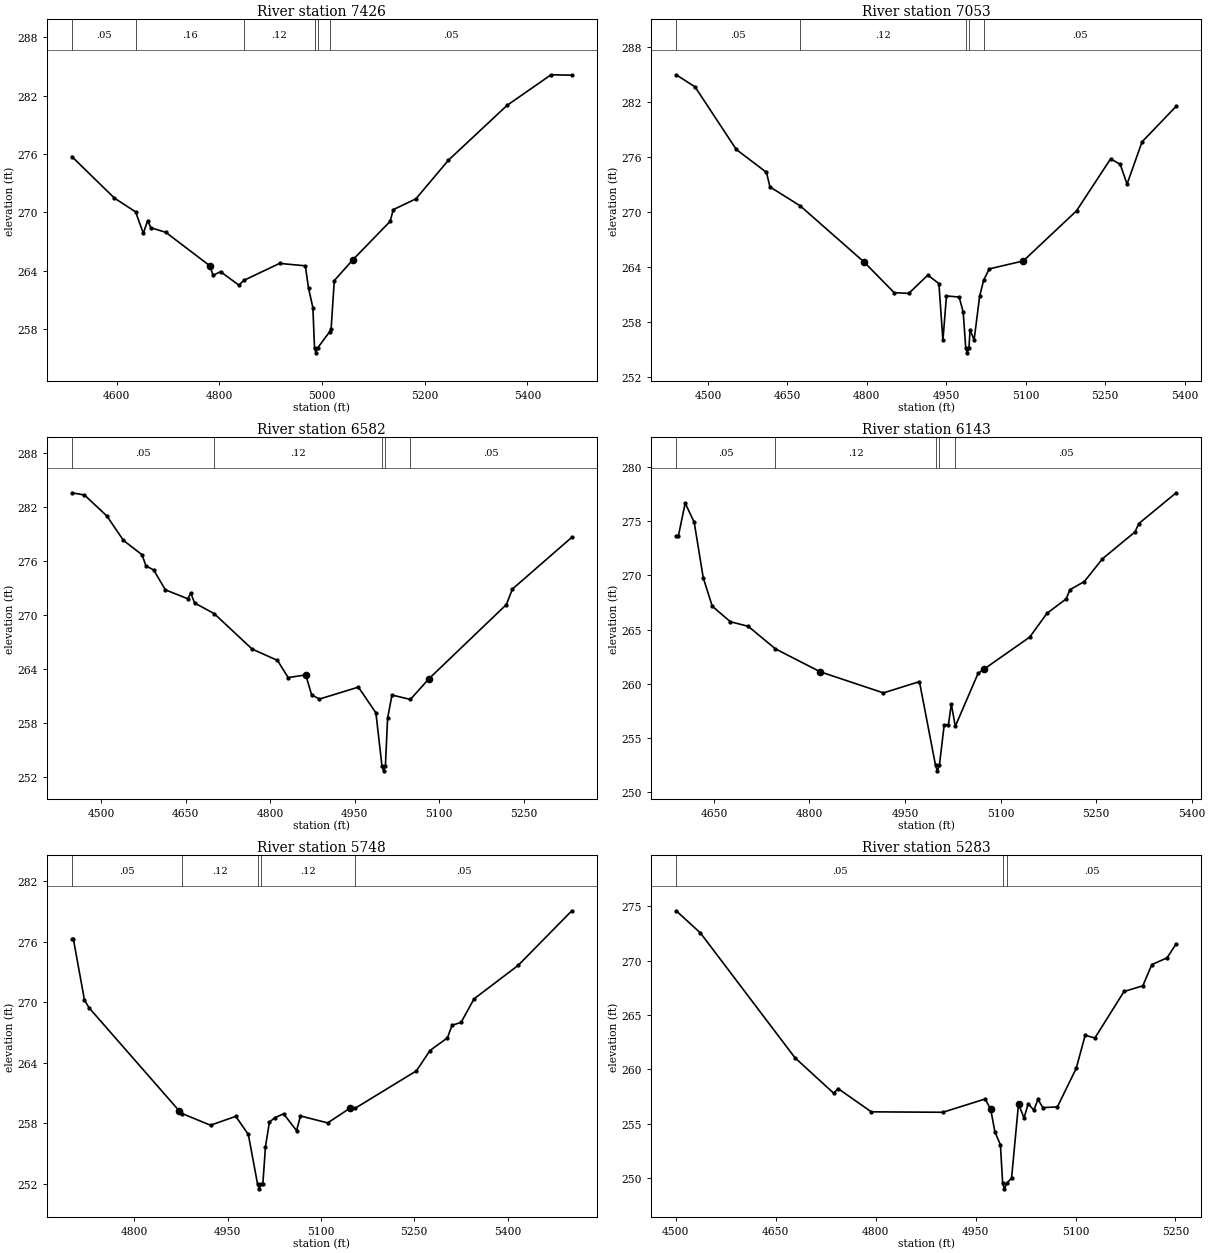
Type RM Length L Ch R = 1 ,7426    ,373,373,373
BEGIN DESCRIPTION:
UNT 0482 IN LACR 15.0
END DESCRIPTION:
XS GIS Cut Line= 2
      3704354.02       10626239.      3703777.61     10627023.75
#Sta/Elev= 30
  4512.7  275.73  4595.5  271.46  4636.8  270.04  4651.9  267.83  4660.3  269.14
  4666.5  268.41  4695.8  267.93  4781.5  264.49  4787.7  263.51  4802.3  263.89
  4837.8  262.51  4847.9     263  4917.3  264.74  4967.4  264.49  4973.6   262.2
  4982.1  260.19  4985.3  256.04    4988  255.54  4991.3  256.04  5014.5  257.69
  5017.6     258  5023.8  262.97  5060.1  265.12  5132.5  269.06  5138.8  270.27
  5182.7  271.38  5246.2  275.36  5360.2  280.99  5445.9  284.14  5486.4   284.1
#Mann= 6 ,-1 , 0
  4512.7     .05       0  4636.8     .16       0  4847.9     .12       0
  4985.3     .07       0  4991.3     .12       0  5014.5     .05       0
Bank Sta=4781.5,5060.1
XS Rating Curve= 0 ,0
Exp/Cntr=0.3,0.1

Type RM Length L Ch R = 1 ,7053    ,471,471,471
BEGIN DESCRIPTION:
UNT 0482 IN LACR 14.0
END DESCRIPTION:
XS GIS Cut Line= 3
      3704299.62     10626010.18      3703899.61     10626360.19
      3703499.64     10626460.18
#Sta/Elev= 30
  4440.1  284.95  4475.7  283.63  4553.5   276.8  4610.5   274.3  4617.1  272.71
  4674.3  270.64  4794.6  264.52  4851.6  261.17  4879.1  261.09  4915.1  263.08
    4936  262.16  4943.6  255.96  4950.3  260.81  4974.2  260.69  4981.9  259.05
  4986.7   255.1  4989.4   254.6  4992.7   255.1  4994.8  257.11  5002.5  256.01
  5012.9  260.77  5020.4  262.51  5030.9  263.76  5095.3  264.63  5195.8   270.1
  5260.2  275.78  5278.3  275.17  5291.2  273.02  5319.5  277.63  5383.9  281.51
#Mann= 5 ,-1 , 0
  4440.1     .05       0  4674.3     .12       0  4986.7     .07       0
  4992.7     .12       0  5020.4     .05       0
Bank Sta=4794.6,5095.3
XS Rating Curve= 0 ,0
Exp/Cntr=0.3,0.1

Type RM Length L Ch R = 1 ,6582    ,439,439,439
BEGIN DESCRIPTION:
UNT 0482 IN LACR 13.0
END DESCRIPTION:
XS GIS Cut Line= 3
      3704249.59     10625860.19      3703699.61     10626010.19
      3703399.61     10626110.19
#Sta/Elev= 30
  4448.5  283.61  4470.9  283.36  4510.7  281.02    4540  278.31  4572.9  276.72
  4579.8  275.49  4593.6  275.02  4614.3  272.82  4654.1  271.82  4659.2  272.46
  4666.2  271.35  4700.9  270.17  4768.1  266.23    4813  264.97    4832  263.06
  4863.1  263.36  4873.5  261.15  4887.3  260.67  4956.4     262  4987.5  259.14
  4998.3  253.19    5001  252.69  5004.3  253.19  5008.2  258.53    5016  261.12
  5048.6  260.63  5081.8  262.95  5218.8  271.18  5229.4   272.9  5334.8  278.66
#Mann= 5 ,-1 , 0
  4448.5     .05       0  4700.9     .12       0  4998.3     .07       0
  5004.3     .12       0  5048.6     .05       0
Bank Sta=4863.1,5081.8
XS Rating Curve= 0 ,0
Exp/Cntr=0.3,0.1

Type RM Length L Ch R = 1 ,6143    ,395,395,395
BEGIN DESCRIPTION:
UNT 0482 IN LACR 12.0
END DESCRIPTION:
XS GIS Cut Line= 3
      3703799.61     10625360.18      3703499.61     10625660.19
      3703299.62     10625960.17
#Sta/Elev= 30
  4590.8  273.65  4594.3  273.65  4604.9  276.67  4619.1  274.89  4633.2  269.79
  4647.4  267.16  4675.7  265.73  4703.9   265.3  4746.6  263.22  4817.1   261.1
  4916.1  259.16  4972.6   260.2  4997.9  252.47  5000.7  251.97  5003.9  252.47
  5011.5  256.21  5018.1  256.21  5022.6  258.13  5028.9  256.08  5064.6  260.95
  5073.7  261.34  5145.8  264.31  5172.8   266.5  5202.9  267.83  5208.9  268.68
  5231.4  269.43  5259.9  271.53    5311  274.01    5317  274.78  5375.6  277.62
#Mann= 5 ,-1 , 0
  4590.8     .05       0  4746.6     .12       0  4997.9     .07       0
  5003.9     .12       0  5028.9     .05       0
Bank Sta=4817.1,5073.7
XS Rating Curve= 0 ,0
Exp/Cntr=0.3,0.1

Type RM Length L Ch R = 1 ,5748    ,465,465,465
BEGIN DESCRIPTION:
UNT 0482 IN LACR 11.0
END DESCRIPTION:
XS GIS Cut Line= 3
      3703749.58     10625260.19      3703449.61     10625310.19
      3703049.62     10625610.18
#Sta/Elev= 30
  4699.3  276.25  4701.8  276.25  4719.6  270.21  4727.2  269.43  4871.6  259.25
  4876.5  258.96  4922.3   257.8  4962.9  258.68  4983.1  256.89  4997.9  251.99
  5000.6  251.49  5003.9  251.99  5006.5  251.99  5010.7  255.68    5017  258.09
  5025.3  258.54  5039.9  258.93  5060.7  257.26    5067  258.72  5110.7  258.03
  5146.1  259.47  5155.4   259.5  5253.4  263.19  5275.3  265.21  5303.4  266.47
  5310.7  267.71  5325.3     268  5346.1  270.33    5417  273.65  5503.4  279.07
#Mann= 5 ,-1 , 0
  4699.3     .05       0  4876.5     .12       0  4997.9     .07       0
  5003.9     .12       0  5155.4     .05       0
Bank Sta=4871.6,5146.1
XS Rating Curve= 0 ,0
Exp/Cntr=0.3,0.1

Type RM Length L Ch R = 1 ,5283    ,310,310,310
BEGIN DESCRIPTION:
UNT 0482 IN LACR 10.0
END DESCRIPTION:
XS GIS Cut Line= 3
      3703449.58     10624660.22      3703149.61     10625060.19
      3702949.57     10625210.22
#Sta/Elev= 30
    4501  274.57  4537.4  272.53  4679.1  261.08  4737.4  257.81  4743.7  258.25
  4793.7  256.11    4901  256.07  4964.5  257.29  4972.8  256.34  4979.1  254.26
  4987.4  253.08  4990.7  249.54  4993.4  249.04  4996.7  249.54  5004.1  250.03
  5014.5  256.83  5022.8  255.55  5029.1  256.86  5037.4  256.26  5043.7  257.26
    5051   256.5  5072.8  256.56    5101  260.09  5114.5  263.14  5129.1  262.89
  5172.8  267.16    5201  267.68  5214.5  269.63  5237.4  270.25    5251  271.54
#Mann= 3 ,-1 , 0
    4501     .05       0  4990.7     .03       0  4996.7     .05       0
Bank Sta=4972.8,5014.5
XS Rating Curve= 0 ,0
Exp/Cntr=0.3,0.1