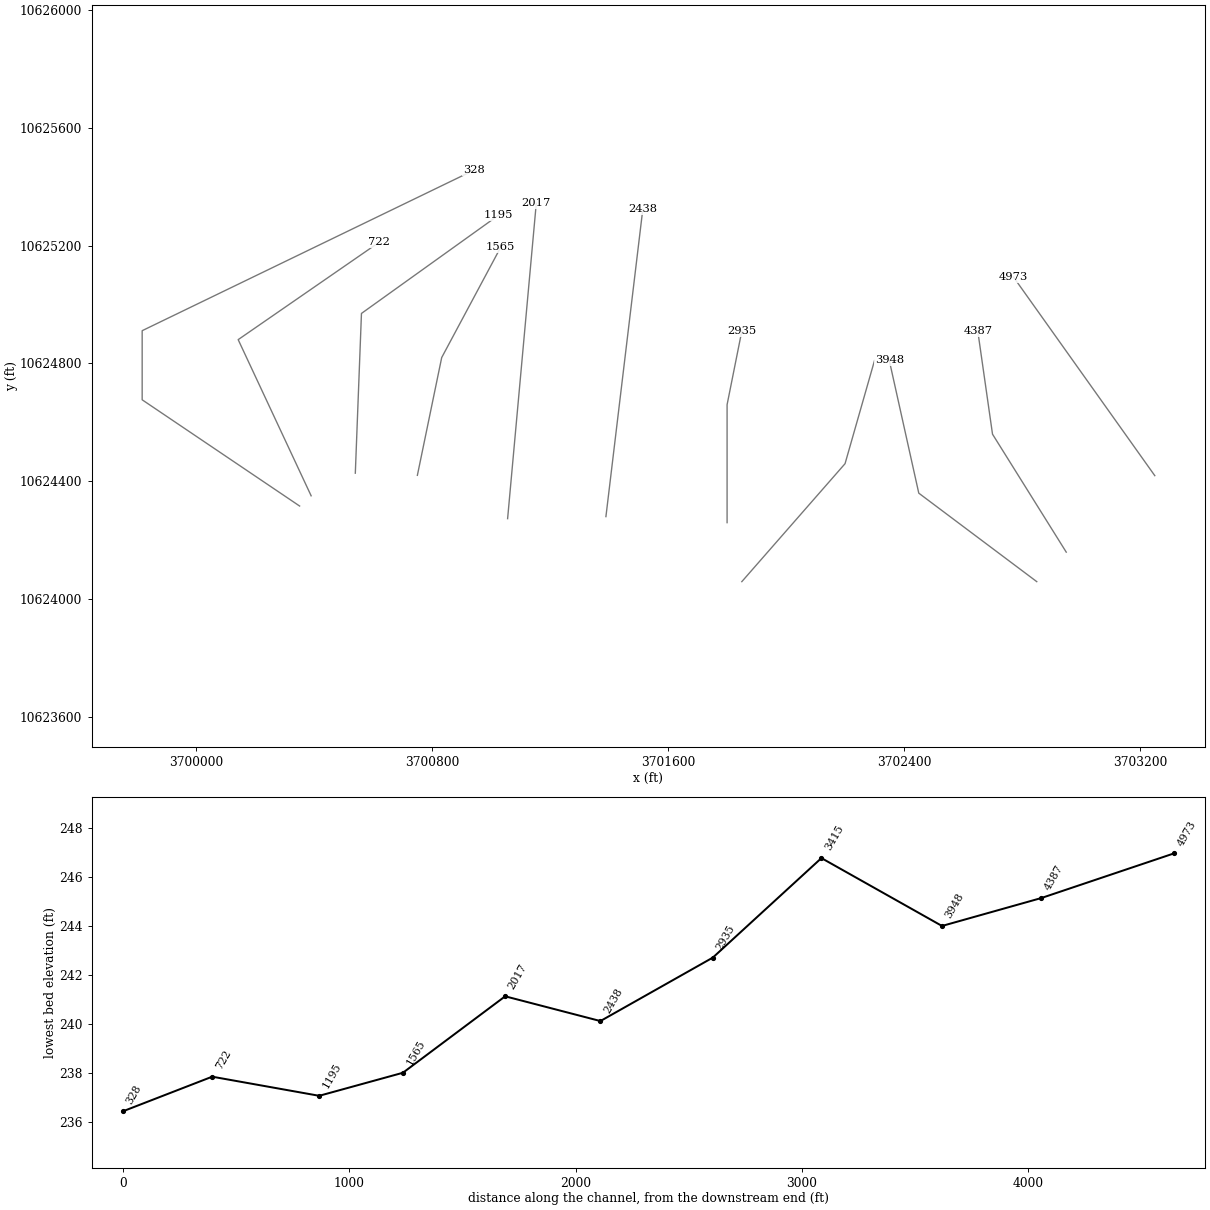
HEC-RAS study UNT 0482 IN LACR.prj: UNT 0482 IN LACR Base Level Engineering

--- UNT 0482 IN LACR.g01 (geometry) --- (continued)

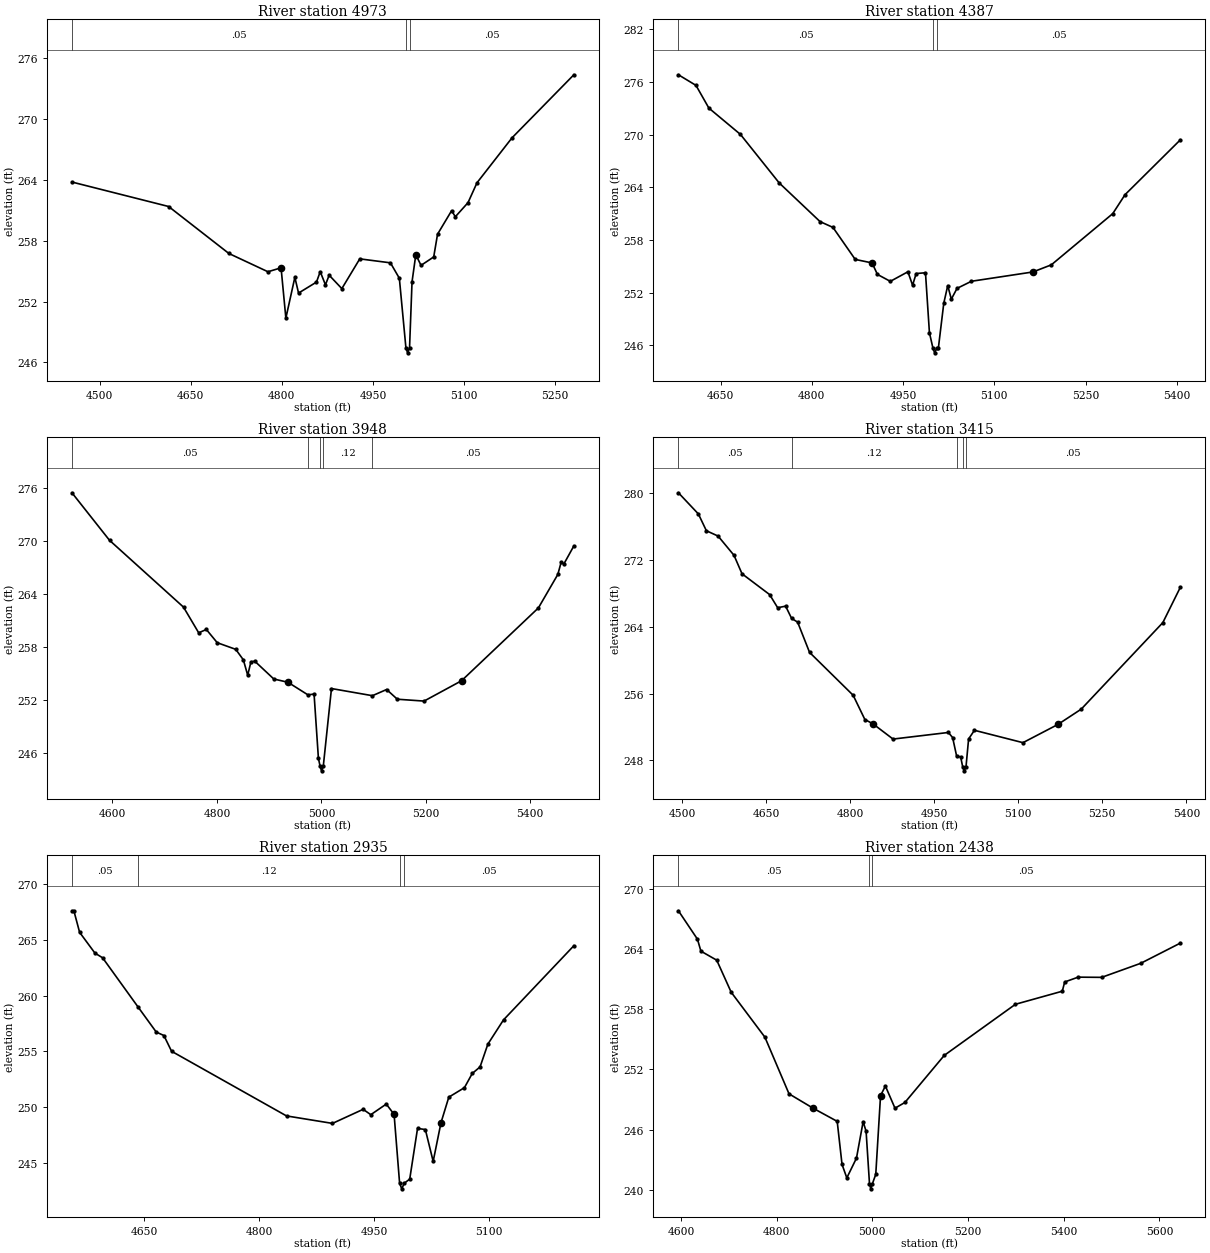
Type RM Length L Ch R = 1 ,4973    ,586,586,586
BEGIN DESCRIPTION:
UNT 0482 IN LACR 9.0
END DESCRIPTION:
XS GIS Cut Line= 2
      3703249.85     10624419.56      3702770.72     10625093.13
#Sta/Elev= 30
  4454.3  263.78  4613.5  261.37  4712.8  256.74  4777.1  254.94  4798.7  255.33
  4806.6  250.37  4821.4  254.39  4827.5  252.84    4857  253.92  4863.2  254.95
  4871.8  253.65  4877.9   254.6  4898.8  253.28  4928.3  256.21  4978.8  255.82
  4993.5   254.3  5004.3  247.45  5007.1  246.95  5010.3  247.45  5014.4  253.95
  5020.6  256.62  5029.2  255.57  5050.1   256.4  5056.4  258.64  5079.6  260.96
  5085.7  260.36  5106.6  261.75  5121.4  263.71  5179.1  268.14  5280.9  274.35
#Mann= 3 ,-1 , 0
  4454.3     .05       0  5004.3     .03       0  5010.3     .05       0
Bank Sta=4798.7,5020.6
XS Rating Curve= 0 ,0
Exp/Cntr=0.3,0.1

Type RM Length L Ch R = 1 ,4387    ,439,439,439
BEGIN DESCRIPTION:
UNT 0482 IN LACR 8.0
END DESCRIPTION:
XS GIS Cut Line= 3
       3702949.6     10624160.21      3702699.61     10624560.19
      3702649.61     10624910.16
#Sta/Elev= 30
  4580.6  276.83  4609.5  275.62  4630.7  273.03  4682.6  270.03  4746.3   264.5
  4813.5  260.09  4834.7  259.43  4871.3  255.78    4899  255.38  4907.8  254.07
    4929  253.28  4957.9  254.37  4965.6  252.84  4971.5  254.17  4986.8  254.26
  4993.3  247.42  4999.2  245.63  5001.9  245.13  5005.2  245.63  5008.1  245.73
  5016.9  250.79  5023.4   252.8  5029.3  251.25  5038.7  252.48  5062.4  253.29
  5163.4  254.35  5193.7  255.16  5294.7     261  5314.9  263.16  5405.8  269.41
#Mann= 3 ,-1 , 0
  4580.6     .05       0  4999.2     .03       0  5005.2     .05       0
Bank Sta=4899,5163.4
XS Rating Curve= 0 ,0
Exp/Cntr=0.3,0.1

Type RM Length L Ch R = 1 ,3948    ,533,533,533
BEGIN DESCRIPTION:
UNT 0482 IN LACR 7.0
END DESCRIPTION:
XS GIS Cut Line= 3
      3702849.63     10624060.17      3702449.61     10624360.19
      3702349.61     10624810.18
#Sta/Elev= 30
  4522.4  275.48  4594.3   270.1    4736  262.53  4765.1  259.62  4779.7     260
  4800.6   258.5    4836  257.75  4850.6  256.56  4858.9  254.82  4865.1  256.33
  4872.4  256.41  4908.9  254.39    4936  254.02  4974.1   252.6    4986  252.68
  4994.3  245.41  4997.6  244.49  5000.3  243.99  5003.6  244.49  5019.3  253.31
  5097.7   252.5  5124.9   253.2  5145.4   252.1  5196.6  251.89  5268.3  254.19
  5415.5  262.44  5452.7  266.23  5459.1  267.62  5464.2  267.41  5483.4  269.46
#Mann= 5 ,-1 , 0
  4522.4     .05       0  4974.1     .12       0  4997.6     .07       0
  5003.6     .12       0  5097.7     .05       0
Bank Sta=4936,5268.3
XS Rating Curve= 0 ,0
Exp/Cntr=0.3,0.1

Type RM Length L Ch R = 1 ,3415    ,480,480,480
BEGIN DESCRIPTION:
UNT 0482 IN LACR 6.0
END DESCRIPTION:
XS GIS Cut Line= 3
      3701849.58     10624060.15      3702199.61     10624460.19
      3702299.62     10624810.23
#Sta/Elev= 30
  4493.6  280.02  4529.2  277.49  4543.5  275.48  4564.4  274.84  4592.8  272.54
  4607.1  270.33  4656.4  267.84  4670.7  266.27  4684.9  266.46  4695.6  264.99
  4706.3  264.55  4727.6  260.93  4805.4   255.8  4826.3   252.9  4840.6  252.39
  4876.6  250.56  4975.3  251.35  4982.9  250.74  4990.2  248.48  4997.2  248.44
  5000.8  247.26  5003.6  246.76  5006.8  247.26  5011.4  250.57  5021.8  251.61
  5108.4  250.13  5170.8  252.31  5212.4  254.14    5358  264.49  5389.2  268.71
#Mann= 5 ,-1 , 0
  4493.6     .05       0  4695.6     .12       0  4990.2     .05       0
  5000.8     .03       0  5006.8     .05       0
Bank Sta=4840.6,5170.8
XS Rating Curve= 0 ,0
Exp/Cntr=0.3,0.1

Type RM Length L Ch R = 1 ,2935    ,497,497,497
BEGIN DESCRIPTION:
UNT 0482 IN LACR 5.0
END DESCRIPTION:
XS GIS Cut Line= 3
      3701799.61     10624260.17      3701799.61     10624660.19
      3701849.62     10624910.22
#Sta/Elev= 30
  4555.8   267.6  4558.3   267.6  4565.8  265.67  4585.8  263.81  4595.8  263.39
  4641.7  259.02  4665.8  256.74  4675.8  256.43  4685.8  255.02  4835.8  249.23
  4895.8  248.56  4935.8  249.82  4945.8  249.34    4966  250.29  4976.2  249.37
  4983.4   243.2  4986.2   242.7  4989.4   243.2  4996.6  243.57  5006.8  248.11
    5017  248.01  5027.2  245.16  5037.4  248.62  5047.6  250.91    5068  251.76
  5078.2  253.03  5088.4  253.62  5098.6  255.66    5119  257.83  5210.8  264.47
#Mann= 4 ,-1 , 0
  4555.8     .05       0  4641.7     .12       0  4983.4     .03       0
  4989.4     .05       0
Bank Sta=4976.2,5037.4
XS Rating Curve= 0 ,0
Exp/Cntr=0.3,0.1

Type RM Length L Ch R = 1 ,2438    ,421,421,421
BEGIN DESCRIPTION:
UNT 0482 IN LACR 4.0
END DESCRIPTION:
XS GIS Cut Line= 2
      3701388.75     10624280.67      3701513.74     10625322.29
#Sta/Elev= 30
  4594.6   267.8  4634.4  264.97  4641.6  263.78  4674.7  262.88  4704.9  259.69
  4775.4  255.21  4825.8  249.57  4876.1  248.14  4926.5  246.83  4936.6  242.54
  4946.6   241.2  4966.8  243.17  4980.7   246.8  4986.9  245.84    4994  240.61
  4996.7  240.11    5000  240.61  5007.1  241.55  5017.1  249.39  5027.2  250.35
  5047.3  248.14    5068  248.71  5150.3   253.4  5299.1  258.49    5397  259.79
    5402  260.71  5430.1  261.19  5479.3  261.17    5561  262.57  5643.7  264.58
#Mann= 3 ,-1 , 0
  4594.6     .05       0    4994     .03       0    5000     .05       0
Bank Sta=4876.1,5017.1
XS Rating Curve= 0 ,0
Exp/Cntr=0.3,0.1

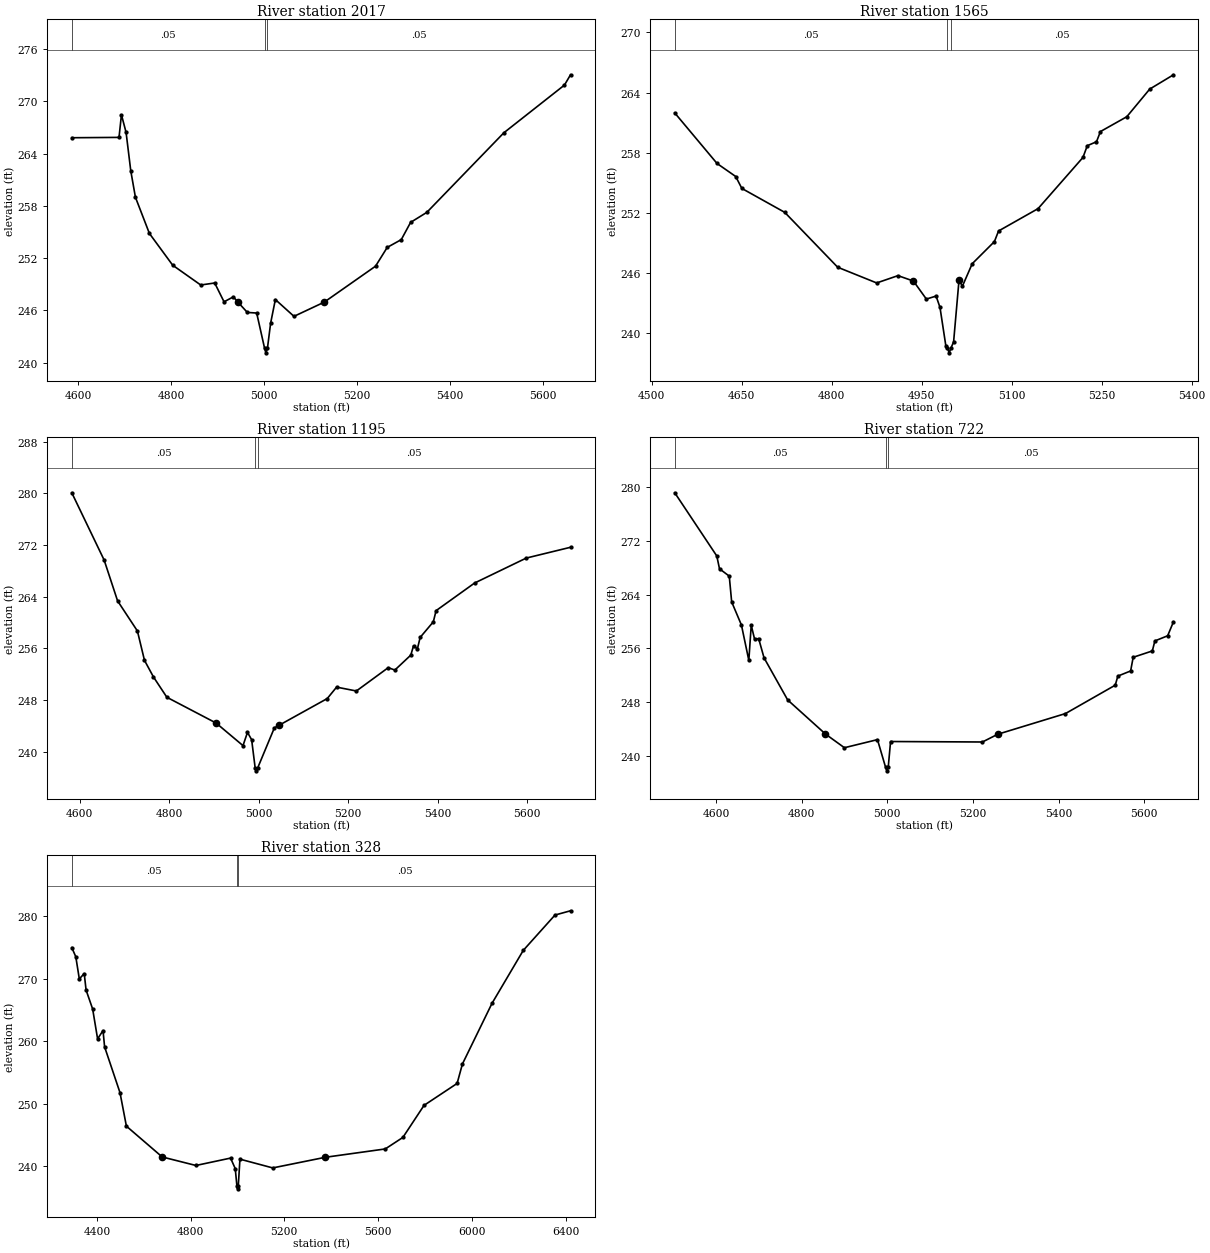
Type RM Length L Ch R = 1 ,2017    ,452,452,452
BEGIN DESCRIPTION:
UNT 0482 IN LACR 3.0
END DESCRIPTION:
XS GIS Cut Line= 2
      3701055.41     10624273.73      3701152.63     10625343.12
#Sta/Elev= 30
  4586.1  265.82  4687.8  265.86    4693  268.46    4703  266.43  4713.1  262.02
  4723.1  258.99  4753.2  254.83  4803.4  251.18  4863.7  248.91  4893.8  249.14
  4913.9  246.98    4934  247.55    4944  246.93  4964.1  245.76  4984.2  245.69
  5001.3  241.62    5004  241.12  5007.3  241.62  5014.2  244.52  5024.4  247.24
  5064.5  245.31  5129.6  246.94  5240.1  251.07  5265.3  253.23  5295.5  254.12
  5315.6   256.1  5350.5  257.25  5516.4  266.39  5646.9  271.87  5659.9  273.05
#Mann= 3 ,-1 , 0
  4586.1     .05       0  5001.3     .03       0  5007.3     .05       0
Bank Sta=4944,5129.6
XS Rating Curve= 0 ,0
Exp/Cntr=0.3,0.1

Type RM Length L Ch R = 1 ,1565    ,370,370,370
BEGIN DESCRIPTION:
Mapping XS 8d803e6d
END DESCRIPTION:
XS GIS Cut Line= 3
      3700749.43     10624420.66       3700831.9     10624819.99
      3701031.57     10625193.29
#Sta/Elev= 30
  4538.5  261.96    4609  256.91  4640.1  255.61  4650.3  254.42  4721.8  252.03
    4810  246.55    4875  244.98  4910.5  245.71  4936.2  245.17  4957.8  243.37
    4974  243.67  4980.5  242.54  4990.3  238.68    4993   238.5  4995.7     238
    4999   238.5  5003.2   239.1  5012.2  245.26  5017.9  244.66  5034.2   246.9
  5071.2  249.11  5078.1  250.17  5143.9   252.4  5218.7  257.51    5226  258.69
  5241.3  259.08  5247.9   260.1  5291.8  261.58    5330  264.34  5369.6  265.77
#Mann= 3 ,-1 , 0
  4538.5     .05       0    4993     .03       0    4999     .05       0
Bank Sta=4936.2,5012.2
XS Rating Curve= 0 ,0
Exp/Cntr=0.3,0.1

Type RM Length L Ch R = 1 ,1195    ,473,473,473
BEGIN DESCRIPTION:
UNT 0482 IN LACR 2.0
END DESCRIPTION:
XS GIS Cut Line= 3
        3700539.     10624427.94      3700559.84     10624969.65
       3701024.9     10625302.83
#Sta/Elev= 30
  4582.4  280.07  4654.7  269.66  4684.7  263.35    4729  258.69  4744.8  254.15
  4764.8  251.59  4794.8  248.44  4904.9  244.45  4964.9  240.96  4974.9  243.01
  4984.2  241.88    4992  237.56  4994.7  237.06    4998  237.56    5035  243.71
    5045  244.09  5153.1  248.24    5174  250.01  5218.2  249.41  5289.4  253.02
  5304.2  252.65  5339.8  254.96  5345.9  256.41  5354.5  255.92  5360.7   257.7
  5390.1  260.11  5396.3  261.84  5482.3  266.11  5597.7  269.97  5696.6  271.64
#Mann= 3 ,-1 , 0
  4582.4     .05       0    4992     .03       0    4998     .05       0
Bank Sta=4904.9,5045
XS Rating Curve= 0 ,0
Exp/Cntr=0.3,0.1

Type RM Length L Ch R = 1 ,722     ,394,394,394
BEGIN DESCRIPTION:
Mapping XS ab8c90f7
END DESCRIPTION:
XS GIS Cut Line= 3
      3700389.19     10624351.26       3700141.8     10624880.76
      3700619.19     10625210.59
#Sta/Elev= 30
  4503.6   279.1  4601.8  269.72  4608.1  267.82  4630.9  266.73  4636.5  262.91
  4659.3  259.48  4676.6  254.23  4682.2  259.45  4690.1  257.36  4699.5  257.47
  4712.1  254.61  4767.3  248.36  4855.6   243.3  4899.8  241.27    4977  242.47
  4996.1  238.34  4998.9  237.84  5002.1  238.34  5007.6  242.19  5222.1  242.12
  5257.9  243.27  5416.1  246.34  5532.3  250.55  5538.4   251.9  5568.2  252.66
  5574.2  254.69  5618.9  255.63  5624.9  257.12  5654.7  257.88  5668.3  259.96
#Mann= 3 ,-1 , 0
  4503.6     .05       0  4996.1     .03       0  5002.1     .05       0
Bank Sta=4855.6,5257.9
XS Rating Curve= 0 ,0
Exp/Cntr=0.3,0.1

Type RM Length L Ch R = 1 ,328     ,0,0,0
BEGIN DESCRIPTION:
UNT 0482 IN LACR 1.0
END DESCRIPTION:
XS GIS Cut Line= 4
      3700350.14     10624316.51      3699816.27     10624676.76
      3699816.27     10624911.14      3700941.18     10625455.47
#Sta/Elev= 30
  4293.2  274.95  4310.3  273.49  4325.3  269.95  4346.3   270.8  4354.2  268.17
  4382.3  265.13  4403.3  260.38  4426.5   261.7  4433.2   259.1  4498.9  251.79
  4526.2  246.44    4679  241.52  4822.9  240.16  4970.7  241.34  4990.7  239.66
  4997.7  236.93  5000.4  236.43  5003.7  236.93  5010.7  241.17  5150.7  239.77
  5375.3  241.47  5630.8   242.8    5706  244.64  5796.3  249.76  5937.4  253.26
    5960  256.36  6086.3  266.05  6219.6   274.5  6355.1  280.15  6421.3  280.83
#Mann= 3 ,-1 , 0
  4293.2     .05       0  4997.7     .03       0  5003.7     .05       0
Bank Sta=4679,5375.3
XS Rating Curve= 0 ,0
Exp/Cntr=0.3,0.1

Chan Stop Cuts=-1
Use User Specified Reach Order=0
Composite Channel Slope=5