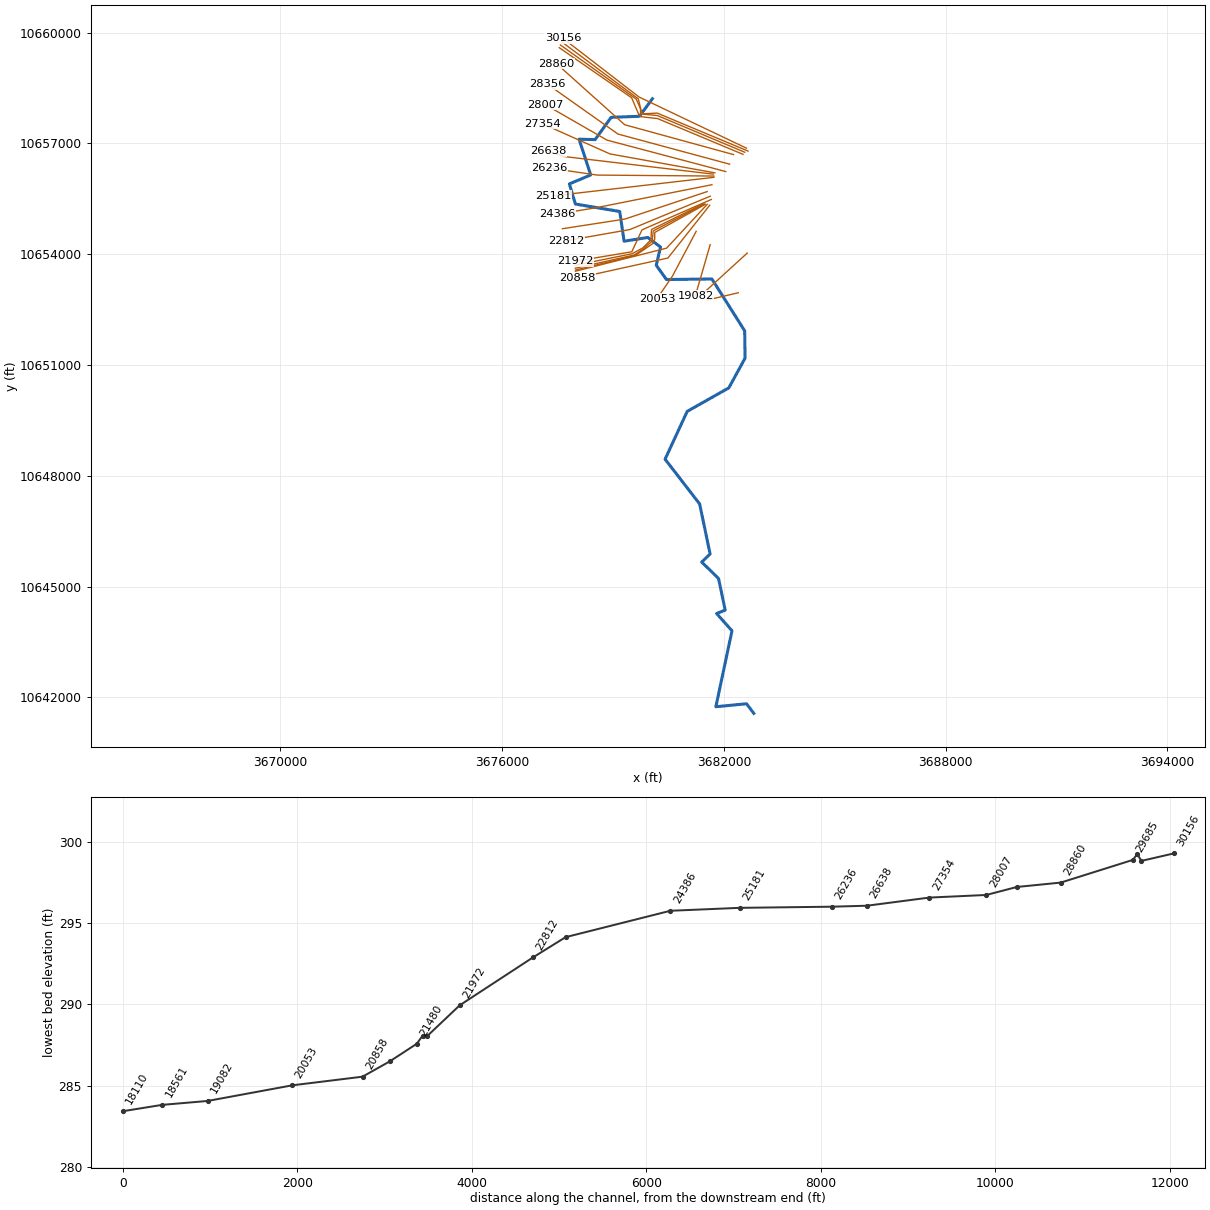
--- UNT 0484 IN LACR.prj (project) ---

Proj Title=UNT 0484 IN LACR Base Level Engineering
Current Plan=p01
Default Exp/Contr=0.3,0.1
English Units
Geom File=g01
Flow File=f01
Plan File=p01
Y Axis Title=Elevation
X Axis Title(PF)=Main Channel Distance
X Axis Title(XS)=Station
BEGIN DESCRIPTION:
UNT 0484 IN LACR
END DESCRIPTION:
DSS Export Rating Curves= 0
DSS Export Rating Curve Sorted= 0
DSS Export Volume Flow Curves= 0
DXF OffsetX= 0
DXF OffsetY= 0
DXF ScaleX= 1
DXF ScaleY= 10

--- UNT 0484 IN LACR.p01 (plan) ---

Plan Title=Multiple Run
Short Identifier=Multiple
Geom File=g01
Flow File=f01
Subcritical Flow
K Sum by GR= 0
Std Step Tol= 0.01
Critical Tol= 0.01
Num of Std Step Trials= 20
Max Error Tol= 0.3
Flow Tol Ratio= 0.001
Split Flow NTrial= 30
Split Flow Tol= 0.02
Split Flow Ratio= 0.02
Log Output Level= 0
Friction Slope Method= 1
Unsteady Friction Slope Method= 2
Unsteady Bridges Friction Slope Method= 1
Parabolic Critical Depth
Global Vel Dist=  1 , 1 , 1
Global Log Level= 0
CheckData=True
Encroach Param= -1, 0, 0, 0
BEGIN DESCRIPTION:
Multiple Run
END DESCRIPTION:

--- UNT 0484 IN LACR.f01 (steady flow) ---

Flow Title=Multiple
Number of Profiles=7
Profile Names=10-year,25-year,50-year,1pct_min,100-year,1pct_plu,500-year
River Rch & RM= UNT 0484 IN LACR,Reach-1,30156
     383     501     595     519     701     949     980
River Rch & RM= UNT 0484 IN LACR,Reach-1,28356
     494     653     780     684     925    1250    1305
River Rch & RM= UNT 0484 IN LACR,Reach-1,21171
     673     903    1089     964    1303    1762    1874
River Rch & RM= UNT 0484 IN LACR,Reach-1,14566
     832    1130    1376    1227    1660    2244    2426
River Rch & RM= UNT 0484 IN LACR,Reach-1,7263
    1335    1852    2286    2064    2792    3775    4185
Boundary for River Rch & Prof#=UNT 0484 IN LACR,Reach-1,1
Up Type=0
Dn Type=3
Dn Slope=0.005
Boundary for River Rch & Prof#=UNT 0484 IN LACR,Reach-1,2
Up Type=0
Dn Type=3
Dn Slope=0.005
Boundary for River Rch & Prof#=UNT 0484 IN LACR,Reach-1,3
Up Type=0
Dn Type=3
Dn Slope=0.005
Boundary for River Rch & Prof#=UNT 0484 IN LACR,Reach-1,4
Up Type=0
Dn Type=3
Dn Slope=0.005
Boundary for River Rch & Prof#=UNT 0484 IN LACR,Reach-1,5
Up Type=0
Dn Type=3
Dn Slope=0.005
Boundary for River Rch & Prof#=UNT 0484 IN LACR,Reach-1,6
Up Type=0
Dn Type=3
Dn Slope=0.005
Boundary for River Rch & Prof#=UNT 0484 IN LACR,Reach-1,7
Up Type=0
Dn Type=3
Dn Slope=0.005

--- UNT 0484 IN LACR.g01 (geometry) ---

Geom Title=Existing Conditions
Program Version=4.10

River Reach=UNT 0484 IN LACR,Reach-1
Reach XY= 30
        3680066.       10658208.      3679715.75       10657734.
       3678950.5       10657706.      3678516.75       10657102.
      3678083.25       10657114.       3678397.5       10656146.
       3677820.5       10655903.        3677983.       10655358.
      3679182.75       10655157.        3679301.       10654352.
        3679943.       10654453.       3680286.5       10654194.
      3680170.25       10653701.      3680446.75       10653315.
      3681677.25       10653329.        3682563.       10651926.
       3682573.5       10651186.      3682134.25       10650381.
        3681008.       10649745.        3680410.       10648450.
       3681344.5       10647239.       3681627.5       10645886.
      3681401.25       10645666.      3681856.25       10645219.
      3682036.25       10644365.        3681804.       10644272.
      3682219.75       10643805.      3681783.75       10641749.
        3682614.       10641829.       3682810.5       10641569.

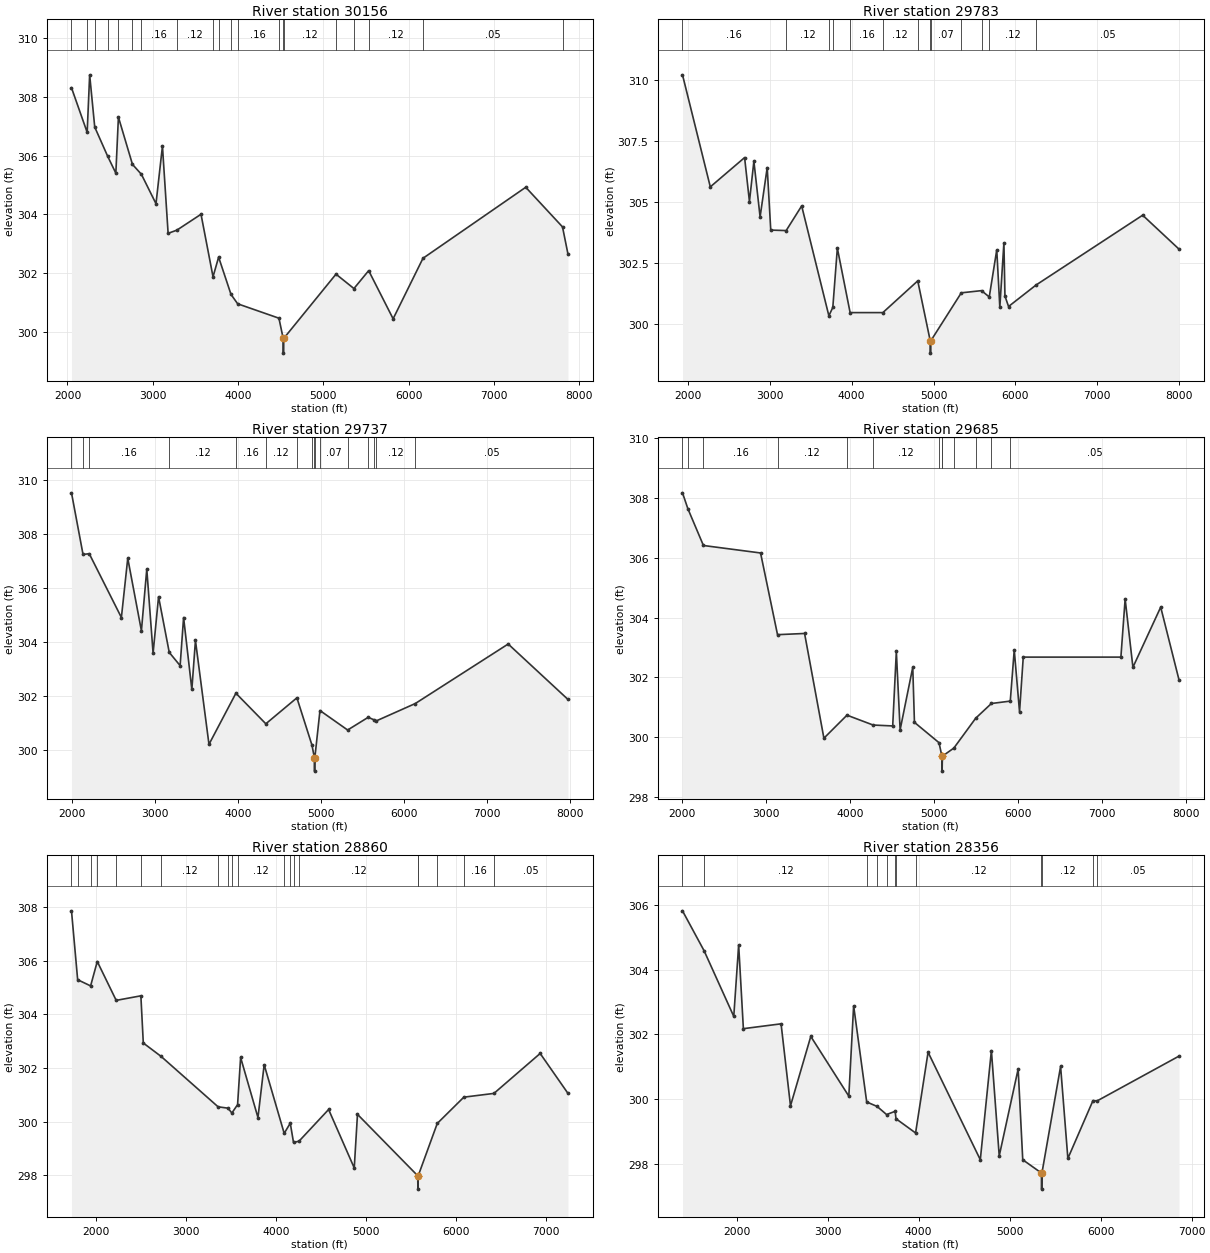
Type RM Length L Ch R = 1 ,30156   ,373,373,373
BEGIN DESCRIPTION:
UNT 0484 IN LACR 39.0
END DESCRIPTION:
XS GIS Cut Line= 3
      3682611.78     10656870.57      3679705.57     10658255.97
      3677648.31     10659844.48
#Sta/Elev= 30
  2047.4  308.31  2231.1  306.79  2260.3  308.75  2319.8  306.97  2472.3  305.97
  2567.2   305.4  2597.3  307.31  2761.9   305.7  2866.9  305.36  3037.7  304.36
  3113.3  306.32  3179.8  303.35  3282.8  303.46  3565.3     304  3706.1  301.87
  3771.6  302.54  3916.8  301.27  3994.9  300.95  4478.5  300.46  4528.3  299.77
    4531  299.27  4534.3  299.77  5147.2  301.96  5357.5  301.47  5530.2  302.08
  5816.7  300.44  6166.4   302.5  7370.9  304.92  7801.7  303.57  7866.1  302.64
#Mann= 20 ,-1 , 0
  2047.4     .16       0  2231.1     .12       0  2319.8     .16       0
  2472.3     .12       0  2597.3     .16       0  2761.9     .05       0
  2866.9     .16       0  3282.8     .12       0  3706.1     .16       0
  3771.6     .05       0  3916.8     .05       0  3994.9     .16       0
  4478.5     .12       0  4528.3     .07       0  4534.3     .12       0
  5147.2     .12       0  5357.5     .07       0  5530.2     .12       0
  6166.4     .05       0  7801.7      .1       0
Bank Sta=4528.3,4534.3
XS Rating Curve= 0 ,0
Exp/Cntr=0.3,0.1

Type RM Length L Ch R = 1 ,29783   ,46,46,46
BEGIN DESCRIPTION:
Mapping XS cc1c7e07
END DESCRIPTION:
XS GIS Cut Line= 6
      3682653.46     10656792.44      3680195.98      10657820.6
      3679839.21     10657802.37      3679776.71     10657828.41
      3679685.57     10658206.01      3677615.38     10659747.83
#Sta/Elev= 30
  1935.9  310.21  2275.3  305.62  2693.9  306.82  2753.1  305.02  2807.3  306.67
  2883.1  304.39  2969.9  306.41  3013.2  303.85  3201.4  303.83  3390.6  304.84
  3722.6  300.34  3770.7  300.68  3826.2  303.11  3982.1  300.47  4381.7  300.47
  4807.6  301.77  4960.2  299.31  4962.9  298.81  4966.2  299.31  5339.3  301.28
  5586.3  301.37  5680.5  301.11  5772.1  303.04  5809.5  300.69  5859.4  303.33
  5872.1  301.15    5916  300.72  6251.9   301.6    7553  304.46  7996.8  303.07
#Mann= 13 ,-1 , 0
  1935.9     .16       0  3201.4     .12       0  3722.6     .05       0
  3770.7     .12       0  3982.1     .16       0  4381.7     .12       0
  4807.6     .07       0  4960.2     .07       0  4966.2     .07       0
  5339.3     .12       0  5586.3     .07       0  5680.5     .12       0
  6251.9     .05       0
Bank Sta=4960.2,4966.2
XS Rating Curve= 0 ,0
Exp/Cntr=0.3,0.1

Type RM Length L Ch R = 1 ,29737   ,52,52,52
BEGIN DESCRIPTION:
Mapping XS a6ac9c45
END DESCRIPTION:
XS GIS Cut Line= 6
      3682564.97     10656761.17      3680198.59     10657755.49
      3679748.07     10657797.16      3679742.86     10657937.78
      3679630.88      10658198.2      3677579.01     10659663.75
#Sta/Elev= 30
  1996.8  309.52  2135.8  307.24  2210.4  307.27  2597.3  304.91    2674   307.1
  2838.3  304.42  2902.9   306.7  2978.8  303.59  3044.6  305.68  3173.3  303.62
  3304.2  303.13  3345.9  304.91  3445.3  302.25  3488.6  304.06  3651.4  300.22
  3975.5  302.11  4335.8  300.98  4709.6  301.94  4891.1  300.19  4919.7  299.73
  4922.5  299.23  4925.7  299.73  4987.3  301.47  5320.3  300.75  5567.8  301.22
  5635.2  301.13  5667.3  301.09  6134.9  301.73  7252.4  303.93  7972.3  301.88
#Mann= 16 ,-1 , 0
  1996.8     .16       0  2135.8     .12       0  2210.4     .16       0
  3173.3     .12       0  3975.5     .16       0  4335.8     .12       0
  4709.6     .07       0  4891.1     .12       0  4919.7     .07       0
  4925.7     .12       0  4987.3     .07       0  5320.3     .12       0
  5567.8     .05       0  5635.2     .07       0  5667.3     .12       0
  6134.9     .05       0
Bank Sta=4919.7,4925.7
XS Rating Curve= 0 ,0
Exp/Cntr=0.3,0.1

Type RM Length L Ch R = 1 ,29685   ,825,825,825
BEGIN DESCRIPTION:
Mapping XS d1ca881b
END DESCRIPTION:
XS GIS Cut Line= 6
      3682518.06     10656703.89      3680207.78     10657671.58
      3679758.56     10657723.67      3679700.09     10657777.79
      3679504.66     10658235.38      3677547.52     10659590.94
#Sta/Elev= 30
  2004.1  308.17    2068  307.64  2253.4  306.41  2934.3  306.16  3136.4  303.43
  3458.8  303.47  3689.1  299.97    3964  300.74  4275.7  300.41  4508.9  300.38
  4552.2  302.87  4597.3  300.25  4747.9  302.34  4767.9   300.5  5060.8  299.82
  5094.9  299.37  5097.7  298.87  5100.9  299.37  5237.5  299.64  5498.3  300.64
  5685.1  301.13  5909.8  301.21  5957.1  302.92  6020.2  300.85  6064.5  302.68
    7228  302.68  7278.6  304.62  7371.2  302.34  7702.3  304.35  7920.4  301.92
#Mann= 13 ,-1 , 0
  2004.1     .16       0    2068     .12       0  2253.4     .16       0
  3136.4     .12       0    3964     .16       0  4275.7     .12       0
  5060.8     .07       0  5094.9     .07       0  5100.9     .07       0
  5237.5     .12       0  5498.3     .05       0  5685.1     .12       0
  5909.8     .05       0
Bank Sta=5094.9,5100.9
XS Rating Curve= 0 ,0
Exp/Cntr=0.3,0.1

Type RM Length L Ch R = 1 ,28860   ,504,504,504
BEGIN DESCRIPTION:
Mapping XS bf581e4e
END DESCRIPTION:
XS GIS Cut Line= 3
      3682259.82     10656697.81      3679317.11      10657505.1
      3677476.86     10659154.39
#Sta/Elev= 30
  1727.5  307.86  1796.1  305.29  1940.1  305.06  2014.2  305.97  2224.8  304.52
  2499.2  304.69  2526.2  302.93  2724.2  302.43  3358.2  300.55  3467.2   300.5
  3511.6  300.32  3574.9  300.63  3608.6  302.39  3801.6  300.15  3870.6  302.12
  4093.4  299.56    4161  299.94  4197.1  299.22  4258.9  299.27  4587.4  300.45
  4872.6  298.27  4908.5  300.27  5578.3  297.98    5581  297.48  5584.3  297.98
    5796  299.93  6091.6  300.91  6426.2  301.05  6940.5  302.54  7250.1  301.05
#Mann= 20 ,-1 , 0
  1727.5     .16       0  1796.1     .12       0  1940.1     .16       0
  2014.2     .12       0  2224.8     .16       0  2499.2     .16       0
  2724.2     .12       0  3358.2     .16       0  3467.2     .12       0
  3511.6     .16       0  3574.9     .12       0  4093.4     .05       0
    4161     .12       0  4197.1     .05       0  4258.9     .12       0
  5578.3     .07       0  5584.3     .12       0    5796     .12       0
  6091.6     .16       0  6426.2     .05       0
Bank Sta=5578.3,5584.3
XS Rating Curve= 0 ,0
Exp/Cntr=0.3,0.1

Type RM Length L Ch R = 1 ,28356   ,349,349,349
BEGIN DESCRIPTION:
UNT 0484 IN LACR 38.0
END DESCRIPTION:
XS GIS Cut Line= 3
      3682155.62      10656437.4      3679134.82     10657253.37
      3677234.17     10658598.58
#Sta/Elev= 30
  1403.9  305.83  1641.9  304.59  1967.5  302.56  2021.3  304.77  2073.1  302.18
  2487.4  302.33    2591  299.79    2814  301.94  3232.1  300.09    3285  302.89
  3428.6  299.91  3543.6  299.77  3647.2  299.52  3741.2  299.62  3750.8  299.39
    3966  298.95  4103.3  301.45  4677.4  298.12  4799.3   301.5  4885.4  298.24
  5093.4  300.93  5143.9  298.12  5348.9  297.71  5351.6  297.21  5354.9  297.71
  5559.9  301.01  5639.9  298.16  5915.5  299.95  5959.8  299.94  6861.5  301.33
#Mann= 12 ,-1 , 0
  1403.9     .16       0  1641.9     .12       0  3428.6     .16       0
  3543.6     .05       0  3647.2     .12       0  3741.2     .05       0
  3750.8     .16       0    3966     .12       0  5348.9     .07       0
  5354.9     .12       0  5915.5     .16       0  5959.8     .05       0
Bank Sta=5348.9,5354.9
XS Rating Curve= 0 ,0
Exp/Cntr=0.3,0.1

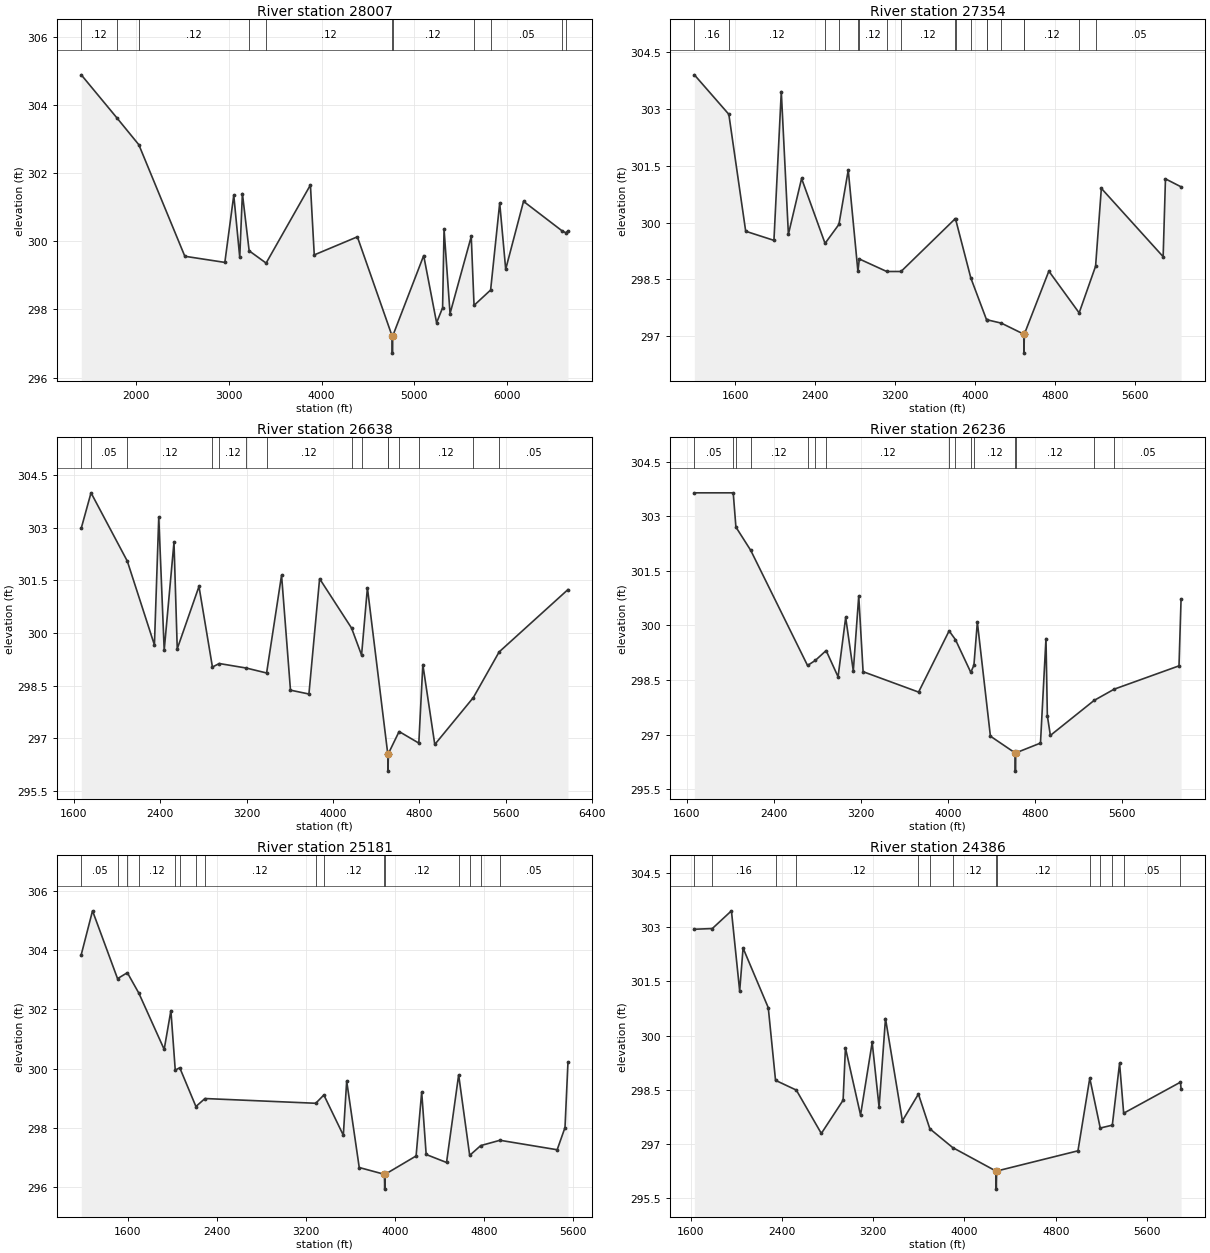
Type RM Length L Ch R = 1 ,28007   ,653,653,653
BEGIN DESCRIPTION:
Mapping XS 2e6dad86
END DESCRIPTION:
XS GIS Cut Line= 3
       3682051.5     10656237.74      3678839.68     10657088.44
      3677164.46     10658051.91
#Sta/Elev= 30
  1405.6  304.88  1792.8  303.61  2027.4  302.83    2524  299.56    2956  299.38
  3052.4  301.35  3116.9  299.53  3145.5   301.4  3218.4  299.72  3401.6  299.36
    3880  301.65  3921.4   299.6  4386.9  300.13  4762.2  297.22    4765  296.72
  4768.2  297.22    5103  299.58  5242.4  297.61  5307.1  298.05  5322.9  300.35
  5387.6  297.88  5616.5  300.14  5646.6  298.12  5825.6  298.57  5923.7  301.12
  5988.4  299.18    6181  301.17  6599.6   300.3  6637.9  300.25  6660.7   300.3
#Mann= 11 ,-1 , 0
  1405.6     .12       0  1792.8     .16       0  2027.4     .12       0
  3218.4     .05       0  3401.6     .12       0  4762.2     .07       0
  4768.2     .12       0  5646.6     .16       0  5825.6     .05       0
  6599.6     .08       0  6637.9     .05       0
Bank Sta=4762.2,4768.2
XS Rating Curve= 0 ,0
Exp/Cntr=0.3,0.1

Type RM Length L Ch R = 1 ,27354   ,716,716,716
BEGIN DESCRIPTION:
Mapping XS 1159c552
END DESCRIPTION:
XS GIS Cut Line= 3
      3681756.37     10656203.02      3678915.99      10656716.3
      3677100.59     10657528.53
#Sta/Elev= 30
  1188.6  303.89  1533.8  302.85  1702.7  299.77  1985.6  299.53  2059.2  303.45
  2130.4  299.69  2262.5  301.16  2497.6  299.45  2636.5  299.95  2729.9  301.38
    2827  298.71  2840.7  299.04  3115.2  298.71  3258.6  298.71  3801.4   300.1
    3805  300.09  3957.7  298.54    4115  297.44  4116.9  297.44  4263.3  297.35
  4487.7  297.06  4490.4  296.56  4493.7  297.06  4739.3  298.72  5042.8  297.62
  5207.5  298.85  5265.1   300.9  5884.2   299.1  5907.4  301.15  6063.8  300.94
#Mann= 18 ,-1 , 0
  1188.6     .16       0  1533.8     .12       0  2497.6     .07       0
  2636.5     .12       0    2827      .1       0  2840.7     .12       0
  3115.2      .1       0  3258.6     .12       0  3801.4     .16       0
    3805     .12       0  3957.7     .07       0    4115     .12       0
  4116.9     .07       0  4263.3     .12       0  4487.7     .07       0
  4493.7     .12       0  5042.8     .16       0  5207.5     .05       0
Bank Sta=4487.7,4493.7
XS Rating Curve= 0 ,0
Exp/Cntr=0.3,0.1

Type RM Length L Ch R = 1 ,26638   ,402,402,402
BEGIN DESCRIPTION:
UNT 0484 IN LACR 37.0
END DESCRIPTION:
XS GIS Cut Line= 3
      3681712.94      10656168.3      3677667.81     10656645.73
      3677256.21     10656791.61
#Sta/Elev= 30
  1668.7  302.99  1759.3     304  2095.6  302.05  2346.7  299.66    2387  303.31
  2437.3  299.51    2528  302.59  2558.2  299.55  2759.6  301.33  2884.2  299.03
  2947.6  299.13  3199.5     299  3386.2  298.86  3524.8  301.65  3607.4  298.37
  3778.3  298.26  3877.3  301.55  4173.7  300.14  4266.1  299.37  4320.3  301.29
  4508.6  296.56  4511.4  296.06  4514.6  296.56    4614  297.19  4796.6  296.86
  4833.9   299.1  4944.6  296.82  5302.1  298.16  5540.6  299.46  6178.6  301.24
#Mann= 15 ,-1 , 0
  1668.7     .16       0  1759.3     .05       0  2095.6     .12       0
  2884.2     .07       0  2947.6     .12       0  3199.5      .1       0
  3386.2     .12       0  4173.7     .16       0  4266.1     .12       0
  4508.6     .07       0  4514.6     .12       0    4614     .07       0
  4796.6     .12       0  5302.1     .16       0  5540.6     .05       0
Bank Sta=4508.6,4514.6
XS Rating Curve= 0 ,0
Exp/Cntr=0.3,0.1

Type RM Length L Ch R = 1 ,26236   ,1055,1055,1055
BEGIN DESCRIPTION:
Mapping XS 148ff16e
END DESCRIPTION:
XS GIS Cut Line= 3
       3681730.3     10656116.21      3678579.26     10656142.26
      3677270.66     10656331.13
#Sta/Elev= 30
  1668.6  303.64  2025.7  303.64  2050.4   302.7  2186.7  302.06  2708.8   298.9
  2780.6  299.04  2879.6  299.31  2989.3  298.59  3059.3  300.22  3129.3  298.75
  3179.3  300.81  3219.3  298.73  3729.4  298.17  4009.8  299.85  4068.1  299.61
  4209.3  298.71  4237.9  298.91  4269.4  300.09  4389.4  296.96  4616.4   296.5
  4619.1     296  4622.4   296.5  4849.7  296.77  4900.2  299.64  4912.8  297.52
  4940.6  296.98  5342.1  297.94  5527.2  298.25  6122.8  298.89  6141.9  300.73
#Mann= 15 ,-1 , 0
  1668.6     .05       0  2025.7     .12       0  2050.4     .05       0
  2186.7     .12       0  2708.8     .07       0  2780.6     .05       0
  2879.6     .12       0  4009.8     .16       0  4068.1     .12       0
  4209.3     .16       0  4237.9     .12       0  4616.4     .07       0
  4622.4     .12       0  5342.1     .16       0  5527.2     .05       0
Bank Sta=4616.4,4622.4
XS Rating Curve= 0 ,0
Exp/Cntr=0.3,0.1

Type RM Length L Ch R = 1 ,25181   ,795,795,795
BEGIN DESCRIPTION:
UNT 0484 IN LACR 36.0
END DESCRIPTION:
XS GIS Cut Line= 2
      3681730.34      10656081.5      3677383.21     10655579.62
#Sta/Elev= 30
  1180.6  303.85    1282  305.33  1506.9  303.04    1595  303.24  1698.3  302.55
  1926.2  300.65  1986.6  301.96  2025.8  299.95  2066.2  300.03  2211.6  298.72
  2292.8  298.99  3288.9  298.83  3361.9  299.11  3536.9  297.75  3567.1  299.58
  3679.9  296.66  3906.3  296.43  3909.1  295.93  3912.3  296.43  4191.2  297.05
  4241.5  299.21  4281.8   297.1  4464.9  296.83  4573.8  299.79    4673  297.07
  4772.1   297.4  4945.4  297.58  5459.6  297.26    5530  298.01  5556.6  300.21
#Mann= 16 ,-1 , 0
  1180.6     .05       0  1506.9     .12       0    1595     .05       0
  1698.3     .12       0  2025.8     .16       0  2066.2     .12       0
  2211.6     .05       0  2292.8     .12       0  3288.9     .07       0
  3361.9     .12       0  3906.3     .03       0  3912.3     .12       0
  4573.8     .07       0    4673     .05       0  4772.1     .16       0
  4945.4     .05       0
Bank Sta=3906.3,3912.3
XS Rating Curve= 0 ,0
Exp/Cntr=0.3,0.1

Type RM Length L Ch R = 1 ,24386   ,1201,1201,1201
BEGIN DESCRIPTION:
Mapping XS 60baf73c
END DESCRIPTION:
XS GIS Cut Line= 3
      3681678.24     10655881.84      3678535.86     10655256.84
      3677487.47     10655086.29
#Sta/Elev= 30
  1632.5  302.94  1789.9  302.96  1957.4  303.45  2029.6  301.23  2059.3  302.42
  2280.2  300.77  2343.9  298.76  2526.2  298.49  2745.3  297.29  2936.2  298.21
  2956.6  299.66  3089.1   297.8  3191.1  299.81  3251.5  298.02  3307.7  300.47
  3455.9  297.64  3596.3  298.38  3696.4  297.42  3896.6   296.9    4276  296.25
  4278.7  295.75    4282  296.25  4994.7  296.81  5098.3  298.82  5190.1  297.44
  5295.8  297.52  5359.5  299.23  5395.4  297.85  5893.5  298.71  5898.6  298.52
#Mann= 14 ,-1 , 0
  1632.5     .05       0  1789.9     .16       0  2343.9     .05       0
  2526.2     .12       0  3596.3     .07       0  3696.4     .05       0
  3896.6     .12       0    4276     .07       0    4282     .12       0
  5098.3     .16       0  5190.1     .12       0  5295.8     .16       0
  5395.4     .05       0  5893.5     .08       0
Bank Sta=4276,4282
XS Rating Curve= 0 ,0
Exp/Cntr=0.3,0.1

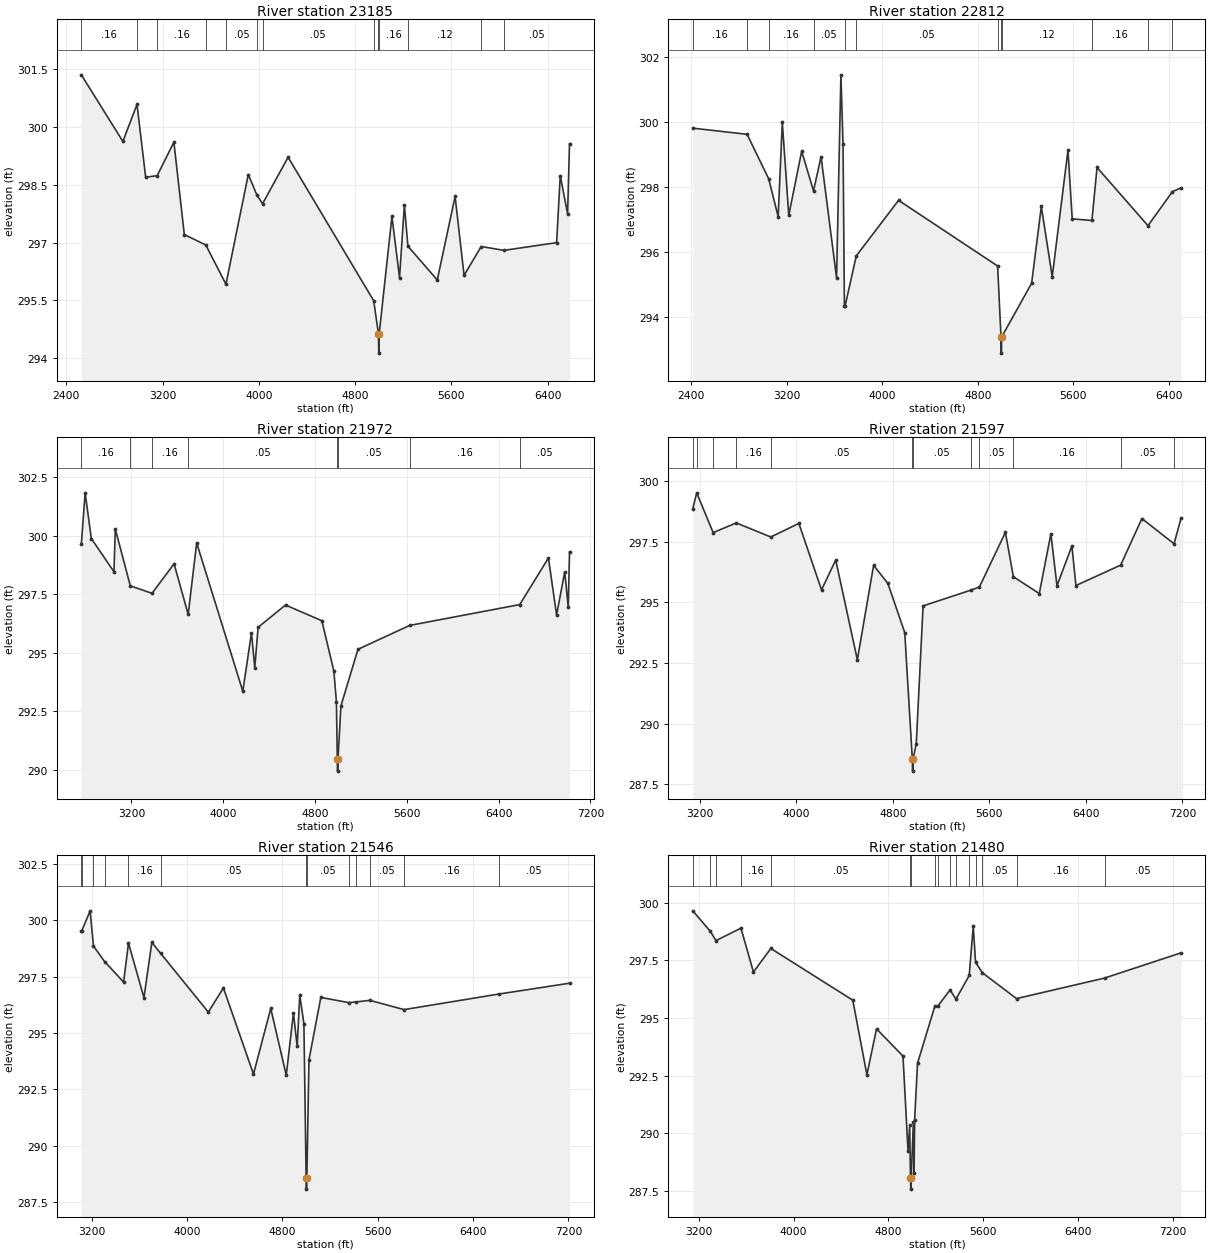
Type RM Length L Ch R = 1 ,23185   ,373,373,373
BEGIN DESCRIPTION:
UNT 0484 IN LACR 35.0
END DESCRIPTION:
XS GIS Cut Line= 3
      3681549.03     10655695.66       3679323.4      10654951.4
      3677633.65     10654690.12
#Sta/Elev= 30
    2525  301.36  2870.2  299.63  2987.8  300.59  3059.7   298.7  3155.3  298.74
  3294.1  299.61  3380.8  297.21  3559.3  296.94  3726.7  295.92  3912.4  298.77
  3983.5  298.24  4030.9  298.01  4243.1  299.22  4954.6  295.49    4994  294.63
  4996.8  294.13    5000  294.63    5106  297.68  5169.1  296.09  5209.5  297.98
  5238.7  296.91  5482.7  296.03  5630.9   298.2  5705.4  296.15  5847.9   296.9
  6036.9   296.8  6474.4     297  6504.7  298.74  6565.5  297.75  6581.6  299.57
#Mann= 13 ,-1 , 0
    2525     .16       0  2987.8     .05       0  3155.3     .16       0
  3559.3     .12       0  3726.7     .05       0  3983.5     .07       0
  4030.9     .05       0  4954.6     .16       0    4994     .07       0
    5000     .16       0  5238.7     .12       0  5847.9     .16       0
  6036.9     .05       0
Bank Sta=4994,5000
XS Rating Curve= 0 ,0
Exp/Cntr=0.3,0.1

Type RM Length L Ch R = 1 ,22812   ,840,840,840
BEGIN DESCRIPTION:
Mapping XS 021139d7
END DESCRIPTION:
XS GIS Cut Line= 3
      3681632.35     10655570.65      3679458.76     10654668.33
      3677746.49     10654367.18
#Sta/Elev= 30
  2411.7  299.81  2866.7  299.62  3047.8  298.25    3127  297.09  3161.8  299.99
  3215.9  297.13  3324.2   299.1  3423.3  297.88  3486.6  298.93  3616.5  295.21
  3653.1  301.45  3670.7  299.33  3682.4  294.35    3688  294.34  3781.8  295.88
  4136.2  297.59  4966.5  295.57  4994.8  293.39  4997.6  292.89  5000.8  293.39
  5251.7  295.04  5332.9   297.4  5424.3  295.24  5556.3  299.13  5591.6  297.02
  5756.9  296.97  5799.9   298.6    6227  296.81  6432.3  297.86  6503.7  297.97
#Mann= 12 ,-1 , 0
  2411.7     .16       0  2866.7     .05       0  3047.8     .16       0
  3423.3     .05       0    3688     .12       0  3781.8     .05       0
  4966.5     .12       0  4994.8     .07       0  5000.8     .12       0
  5756.9     .16       0    6227     .05       0  6432.3     .08       0
Bank Sta=4994.8,5000.8
XS Rating Curve= 0 ,0
Exp/Cntr=0.3,0.1

Type RM Length L Ch R = 1 ,21972   ,375,375,375
BEGIN DESCRIPTION:
UNT 0484 IN LACR 34.0
END DESCRIPTION:
XS GIS Cut Line= 4
       3681660.1      10655482.1      3679785.14      10654659.2
      3679510.03     10654065.98      3677978.57     10653809.44
#Sta/Elev= 30
  2763.6  299.63  2796.9  301.83  2850.7  299.88  3048.1  298.46  3059.5  300.29
  3190.4  297.86  3379.6  297.54  3571.9   298.8  3694.8  296.64  3768.8  299.69
  4170.8  293.36  4246.4  295.85  4275.2  294.36    4304  296.09  4543.1  297.04
  4859.8  296.37  4964.4  294.22  4986.5  292.92  4994.3  290.45    4997  289.95
  5000.3  290.45  5025.7  292.73  5174.2  295.15  5625.2  296.17  6584.1  297.06
  6834.3  299.05  6905.3  296.61  6976.3  298.46  7006.7  296.96  7017.9  299.29
#Mann= 8 ,-1 , 0
  2763.6     .16       0  3190.4     .05       0  3379.6     .16       0
  3694.8     .05       0  4994.3     .03       0  5000.3     .05       0
  5625.2     .16       0  6584.1     .05       0
Bank Sta=4994.3,5000.3
XS Rating Curve= 0 ,0
Exp/Cntr=0.3,0.1

Type RM Length L Ch R = 1 ,21597   ,51,51,51
BEGIN DESCRIPTION:
Mapping XS f499be68
END DESCRIPTION:
XS GIS Cut Line= 6
      3681436.86     10655360.12      3680041.57     10654668.41
      3680027.68      10654388.9      3679801.99     10654166.67
      3679516.76     10654012.92      3677983.93     10653701.34
#Sta/Elev= 30
  3143.8  298.87  3176.1  299.52  3312.1  297.88  3503.2  298.28  3789.8   297.7
  4022.5  298.26  4209.9  295.52  4327.5  296.75  4506.9  292.64  4641.4  296.53
  4759.4  295.79  4899.4  293.76  4962.2  288.55  4964.9  288.05  4968.2  288.55
  4994.9  289.18  5051.4  294.86  5447.9  295.51  5517.9  295.64  5733.2  297.89
  5799.5  296.06  6013.9  295.37    6110  297.83  6160.6  295.69  6284.2  297.33
  6317.6   295.7  6687.9  296.54  6864.1  298.46  7130.3  297.42    7188  298.47
#Mann= 12 ,-1 , 0
  3143.8     .12       0  3176.1     .16       0  3312.1     .05       0
  3503.2     .16       0  3789.8     .05       0  4962.2     .03       0
  4968.2     .05       0  5447.9     .07       0  5517.9     .05       0
  5799.5     .16       0  6687.9     .05       0  7130.3      .1       0
Bank Sta=4962.2,4968.2
XS Rating Curve= 0 ,0
Exp/Cntr=0.3,0.1

Type RM Length L Ch R = 1 ,21546   ,66,66,66
BEGIN DESCRIPTION:
Mapping XS 9c36ccd4
END DESCRIPTION:
XS GIS Cut Line= 6
      3681478.53     10655360.12      3680089.86     10654631.12
      3680060.67     10654355.91      3679817.61     10654137.16
      3679572.32     10653978.19       3677983.9     10653621.78
#Sta/Elev= 30
  3113.5  299.53    3117  299.53  3187.2  300.42  3215.3  298.86  3309.1  298.17
  3468.2  297.26  3509.1  298.99  3638.9  296.57  3705.1  299.02    3778  298.54
  4178.9  295.93  4305.6     297  4557.9  293.18  4702.8  296.09  4832.8  293.13
  4893.1  295.89  4924.4  294.41  4946.1  296.68  4980.9  295.42  4999.6  288.58
  5002.3  288.08  5005.6  288.58  5023.5  293.82  5122.9  296.58  5357.7  296.35
  5418.8  296.38  5533.8  296.45  5821.3  296.04  6616.1  296.73  7209.3  297.21
#Mann= 13 ,-1 , 0
  3113.5     .16       0    3117     .12       0  3215.3     .16       0
  3309.1     .05       0  3509.1     .16       0    3778     .05       0
  4999.6     .03       0  5005.6     .05       0  5357.7     .16       0
  5418.8     .07       0  5533.8     .05       0  5821.3     .16       0
  6616.1     .05       0
Bank Sta=4999.6,5005.6
XS Rating Curve= 0 ,0
Exp/Cntr=0.3,0.1

Type RM Length L Ch R = 1 ,21480   ,309,309,309
BEGIN DESCRIPTION:
Mapping XS c65df8ea
END DESCRIPTION:
XS GIS Cut Line= 6
      3681495.95     10655349.73       3680131.9     10654589.69
      3680128.38     10654402.79      3680079.77     10654289.94
      3679603.57      10653964.3      3677987.24     10653573.21
#Sta/Elev= 30
  3150.7  299.64  3297.1  298.76  3346.1  298.35  3556.4  298.89  3661.7  296.99
  3808.2  298.01  4499.3  295.77  4618.1  292.54  4699.3  294.53  4922.3  293.35
  4965.1  289.23  4978.8  290.35  4985.4  288.09  4988.1  287.59  4991.4  288.09
    5010  290.48  5015.8   288.3  5020.5   290.6    5045  293.04  5191.8  295.53
  5213.4   295.5    5319  296.21  5369.3  295.82  5480.4  296.84  5514.7  298.97
  5534.1  297.41  5591.5  296.96  5879.3  295.84  6622.4  296.73  7265.9  297.82
#Mann= 16 ,-1 , 0
  3150.7     .12       0  3297.1     .16       0  3346.1     .05       0
  3556.4     .16       0  3808.2     .05       0  4985.4     .03       0
  4991.4     .05       0  5191.8     .16       0  5213.4     .05       0
    5319     .12       0  5369.3     .16       0  5480.4     .07       0
  5534.1     .12       0  5591.5     .05       0  5879.3     .16       0
  6622.4     .05       0
Bank Sta=4985.4,4991.4
XS Rating Curve= 0 ,0
Exp/Cntr=0.3,0.1

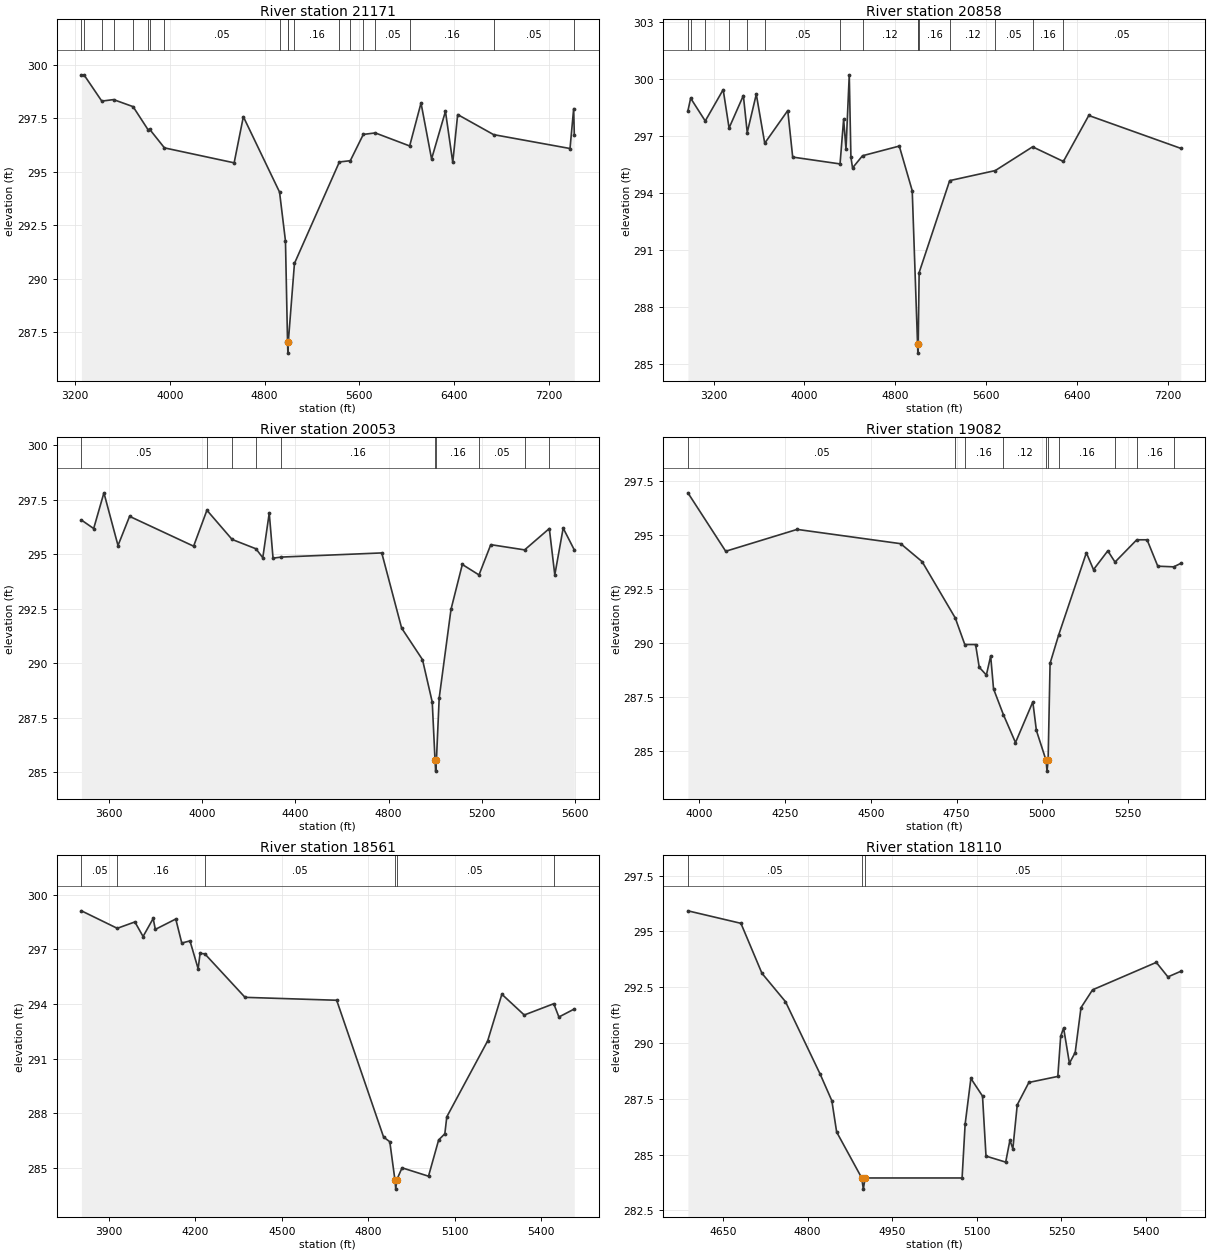
Type RM Length L Ch R = 1 ,21171   ,313,313,313
BEGIN DESCRIPTION:
UNT 0484 IN LACR 33.0
END DESCRIPTION:
XS GIS Cut Line= 3
      3681550.75      10655351.9       3680451.8     10654164.41
      3677984.57     10653539.56
#Sta/Elev= 30
  3252.2  299.54    3275  299.53  3424.1  298.31  3523.4  298.38  3688.5  298.05
  3814.9  296.97  3828.3  296.99  3953.4  296.12  4542.1  295.42  4619.8  297.58
  4925.6  294.05  4975.6  291.76  4993.2  287.01    4996  286.51  4999.2  287.01
  5051.5  290.71  5430.9  295.46  5523.3  295.52  5633.1  296.75  5734.2  296.82
  6024.6  296.21  6120.6  298.22  6209.7   295.6  6326.9  297.83  6388.8  295.44
  6430.1  297.68  6733.7  296.74  7379.1  296.09    7410  297.96  7415.3  296.72
#Mann= 19 ,-1 , 0
  3252.2     .16       0    3275     .12       0  3424.1     .16       0
  3523.4     .05       0  3688.5     .12       0  3814.9     .16       0
  3828.3     .12       0  3953.4     .05       0  4925.6     .12       0
  4993.2     .07       0  4999.2     .12       0  5051.5     .16       0
  5430.9     .12       0  5523.3     .07       0  5633.1     .12       0
  5734.2     .05       0  6024.6     .16       0  6733.7     .05       0
    7410     .08       0
Bank Sta=4993.2,4999.2
XS Rating Curve= 0 ,0
Exp/Cntr=0.3,0.1

Type RM Length L Ch R = 1 ,20858   ,805,805,805
BEGIN DESCRIPTION:
UNT 0484 IN LACR 32.0
END DESCRIPTION:
XS GIS Cut Line= 3
      3681618.45     10655327.57      3680486.53     10653897.05
      3678028.18     10653355.38
#Sta/Elev= 30
  2974.3  298.32  2998.5  298.99  3127.1  297.79    3285  299.44    3337  297.42
  3462.9  299.13  3496.9  297.18  3576.7   299.2  3651.1  296.62    3854  298.34
  3897.3  295.89  4314.5  295.53  4346.1  297.88  4366.9  296.31  4395.7  300.22
  4410.2  295.88  4424.6  295.32  4512.3  295.96  4836.3  296.47  4950.3  294.12
  4997.1  286.07  4999.9  285.57  5003.1  286.07  5011.2  289.81  5280.1  294.65
  5681.9  295.18  6010.6  296.43  6281.8  295.66  6505.4  298.08  7315.8  296.35
#Mann= 15 ,-1 , 0
  2974.3     .16       0  2998.5     .12       0  3127.1     .16       0
    3337     .05       0  3496.9     .16       0  3651.1     .05       0
  4314.5     .07       0  4512.3     .12       0  4997.1     .07       0
  5003.1     .12       0  5011.2     .16       0  5280.1     .12       0
  5681.9     .05       0  6010.6     .16       0  6281.8     .05       0
Bank Sta=4997.1,5003.1
XS Rating Curve= 0 ,0
Exp/Cntr=0.3,0.1

Type RM Length L Ch R = 1 ,20053   ,971,971,971
BEGIN DESCRIPTION:
UNT 0484 IN LACR 31.0
END DESCRIPTION:
XS GIS Cut Line= 3
       3681250.4     10654619.25       3680607.9     10653404.55
      3680188.73     10652794.06
#Sta/Elev= 30
  3481.9  296.57  3534.4  296.18  3578.4  297.82  3638.8   295.4  3688.5  296.74
  3963.2  295.37  4020.3  297.02  4128.3  295.68  4230.7  295.25    4260  294.84
  4287.7  296.89    4304  294.82  4339.4  294.87  4770.5  295.06  4855.7  291.61
  4945.2  290.16  4987.1  288.21    4999  285.54  5001.8  285.04    5005  285.54
  5016.9   288.4  5067.6  292.47  5116.1  294.53  5187.7  294.05  5238.2  295.44
  5383.4   295.2  5489.4  296.18  5512.9  294.05  5548.8   296.2  5596.6   295.2
#Mann= 10 ,-1 , 0
  3481.9     .05       0  4020.3     .07       0  4128.3     .16       0
  4230.7     .12       0  4339.4     .16       0    4999     .07       0
    5005     .16       0  5187.7     .05       0  5383.4     .16       0
  5489.4     .12       0
Bank Sta=4999,5005
XS Rating Curve= 0 ,0
Exp/Cntr=0.3,0.1

Type RM Length L Ch R = 1 ,19082   ,521,521,521
BEGIN DESCRIPTION:
UNT 0484 IN LACR 30.0
END DESCRIPTION:
XS GIS Cut Line= 2
      3681629.01     10654256.05      3681229.71     10652875.85
#Sta/Elev= 30
  3966.9  296.94  4077.1  294.24  4285.3  295.25  4587.2  294.59  4649.7  293.76
  4746.2  291.16  4774.1  289.93  4805.5  289.93  4816.2  288.88    4837  288.52
  4849.5   289.4  4857.9  287.88  4886.6  286.69  4921.9   285.4  4972.4  287.28
  4982.8  285.96    5011  284.58  5013.8  284.08    5017  284.58  5022.7  289.06
  5047.5  290.36  5128.5  294.17  5149.3  293.39    5191  294.26    5212  293.74
  5275.4  294.77  5305.5  294.77  5336.7  293.55  5383.1  293.52  5403.7  293.68
#Mann= 10 ,-1 , 0
  3966.9     .05       0  4746.2     .12       0  4774.1     .16       0
  4886.6     .12       0    5011     .07       0    5017     .12       0
  5047.5     .16       0    5212     .12       0  5275.4     .16       0
  5383.1     .12       0
Bank Sta=5011,5017
XS Rating Curve= 0 ,0
Exp/Cntr=0.3,0.1

Type RM Length L Ch R = 1 ,18561   ,451,451,451
BEGIN DESCRIPTION:
Mapping XS 452461e4
END DESCRIPTION:
XS GIS Cut Line= 2
      3682631.63     10654030.39       3681368.6     10652875.86
#Sta/Elev= 30
  3804.3  299.12  3928.7  298.16  3989.9  298.51  4018.3  297.71  4053.4   298.7
  4060.8   298.1  4131.8  298.67  4152.7  297.35  4181.1  297.47  4209.5  295.94
  4216.2  296.78  4232.6  296.76  4372.3  294.37  4690.5  294.21  4853.3   286.7
  4874.9  286.44  4892.8  284.34  4895.6  283.84  4898.8  284.34  4917.4  285.01
  5009.3  284.55  5044.5  286.54    5066  286.88  5072.8  287.81  5214.7  291.98
    5264  294.54  5341.7   293.4  5444.2  294.02    5462  293.29  5515.5  293.73
#Mann= 6 ,-1 , 0
  3804.3     .05       0  3928.7     .16       0  4232.6     .05       0
  4892.8     .03       0  4898.8     .05       0  5444.2     .12       0
Bank Sta=4892.8,4898.8
XS Rating Curve= 0 ,0
Exp/Cntr=0.3,0.1

Type RM Length L Ch R = 1 ,18110   ,425,425,425
BEGIN DESCRIPTION:
UNT 0484 IN LACR 29.0
END DESCRIPTION:
XS GIS Cut Line= 2
      3682388.08      10652956.2      3681537.39     10652756.54
#Sta/Elev= 30
  4587.8  295.92  4681.8  295.36  4719.1  293.12  4760.8  291.85  4822.5  288.59
    4843  287.41  4851.5  286.01    4896  283.95  4898.8  283.45    4902  283.95
  5073.9  283.95  5079.3  286.36  5089.5  288.41  5110.1  287.62  5116.3  284.93
  5151.2  284.66  5158.7  285.64  5163.9  285.26  5171.7  287.23  5192.3  288.23
  5243.6   288.5  5248.7   290.3  5253.9  290.67  5264.2  289.09  5274.4  289.57
  5284.7  291.58  5305.2  292.38  5418.2  293.61  5438.8  292.96  5461.6  293.21
#Mann= 3 ,-1 , 0
  4587.8     .05       0    4896    .033       0    4902     .05       0
Bank Sta=4896,4902
XS Rating Curve= 0 ,0
Exp/Cntr=0.3,0.1