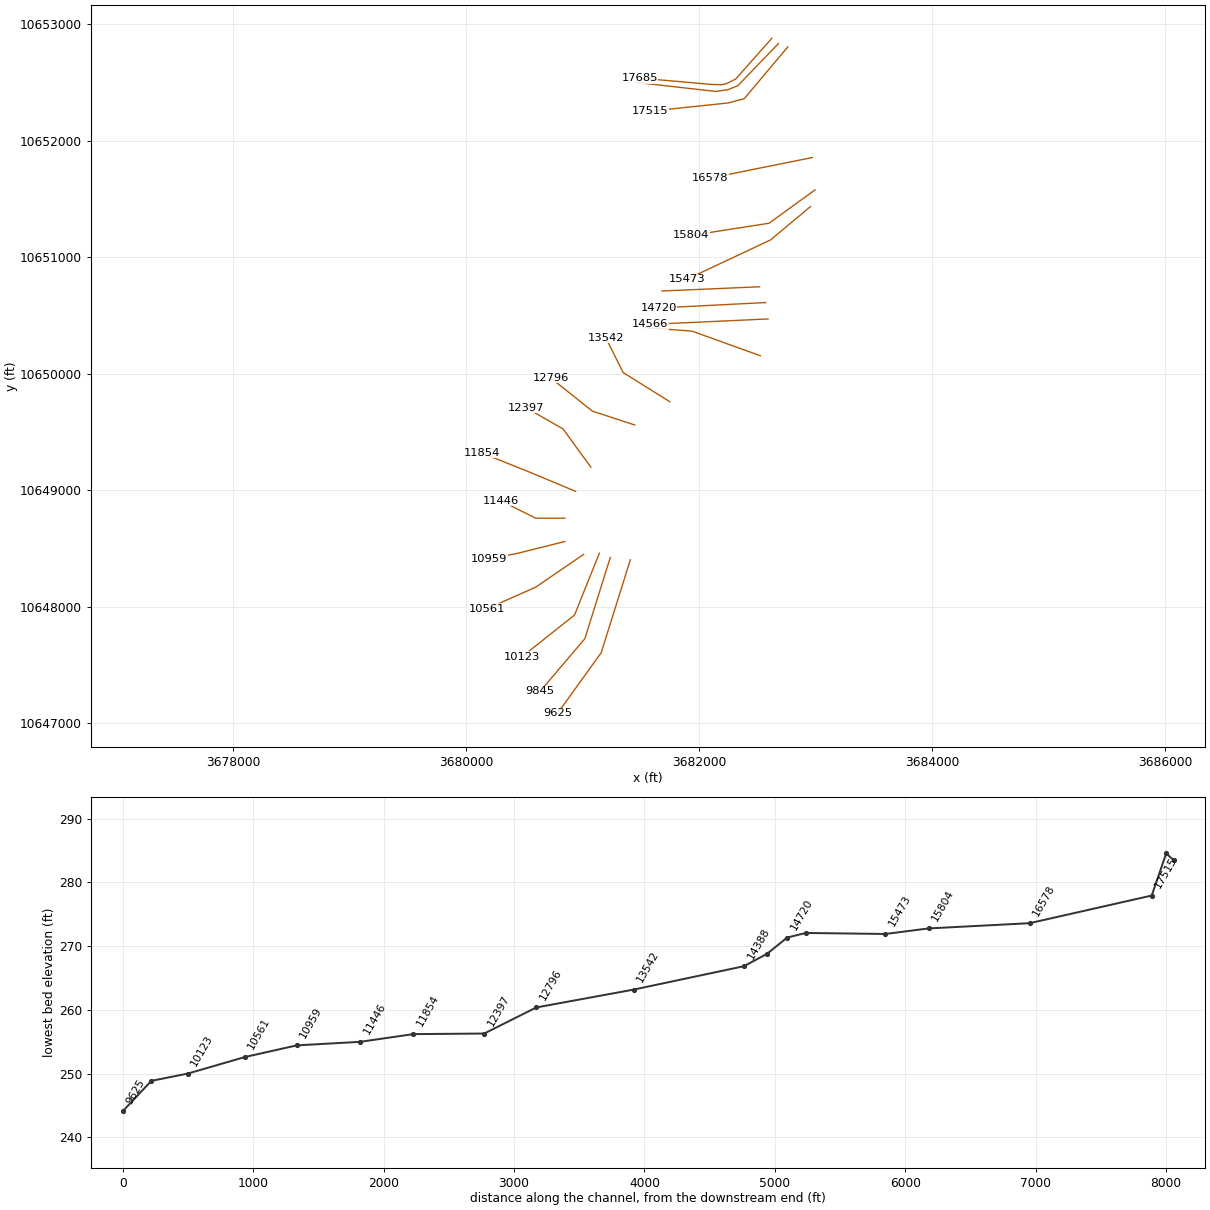
HEC-RAS study UNT 0484 IN LACR.prj: UNT 0484 IN LACR Base Level Engineering

--- UNT 0484 IN LACR.g01 (geometry) --- (continued)

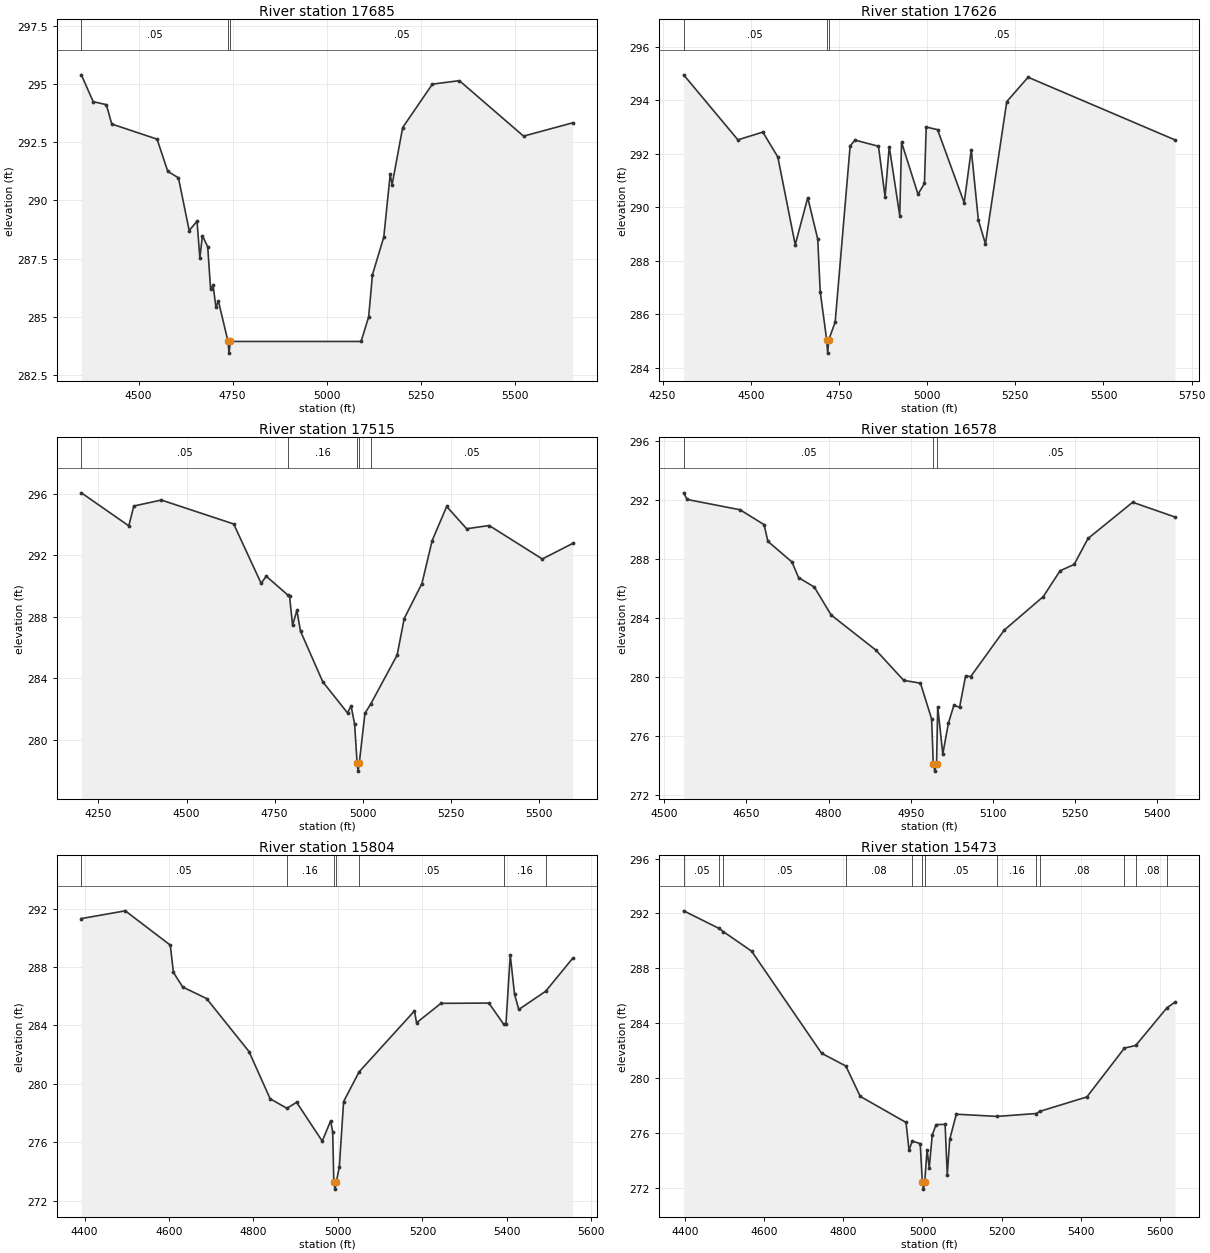
Type RM Length L Ch R = 1 ,17685   ,59,59,59
BEGIN DESCRIPTION:
Mapping XS 72f59c21
END DESCRIPTION:
XS GIS Cut Line= 6
      3682625.37     10652878.76      3682315.46     10652529.79
      3682237.34     10652490.73      3682195.67     10652480.31
      3682109.73     10652482.91      3681489.93      10652537.6
#Sta/Elev= 30
    4348  295.39  4379.4  294.24  4414.5  294.11  4428.7  293.28  4549.2  292.63
  4577.6  291.25    4606  290.97  4634.5  288.71  4655.4  289.11  4662.9  287.53
  4669.6  288.49  4683.8  288.01  4691.3  286.21    4698  286.36  4705.5  285.43
  4712.2  285.68  4737.7  283.95  4740.4  283.45  4743.7  283.95  5091.3  283.95
  5111.4  285.01  5121.5  286.82  5151.6  288.43  5168.6  291.12  5173.7  290.68
  5201.8  293.13  5280.7  294.99  5352.4  295.14    5523  292.76  5653.2  293.33
#Mann= 3 ,-1 , 0
    4348     .05       0  4737.7    .033       0  4743.7     .05       0
Bank Sta=4737.7,4743.7
XS Rating Curve= 0 ,0
Exp/Cntr=0.3,0.1

Type RM Length L Ch R = 1 ,17626   ,111,111,111
BEGIN DESCRIPTION:
Mapping XS 82ecf12a
END DESCRIPTION:
XS GIS Cut Line= 5
      3682682.66     10652834.49      3682333.69      10652472.5
      3682250.36     10652438.64      3682143.59     10652423.02
      3681456.08     10652501.14
#Sta/Elev= 30
  4309.9  294.95  4463.7  292.52  4534.4  292.81  4576.8  291.88  4626.2   288.6
  4661.7  290.36    4690  288.81    4697  286.85  4715.3  285.05  4718.1  284.55
  4721.3  285.05  4739.4  285.71  4781.9   292.3    4796  292.51  4862.2  292.28
  4880.9  290.39  4892.7  292.27  4922.5  289.69  4927.6  292.43  4974.2  290.49
  4992.5  290.89  4997.5     293  5029.7   292.9  5105.1  290.17  5125.3  292.15
  5145.4  289.52  5165.5  288.63  5225.9  293.95  5286.3  294.86  5702.5  292.52
#Mann= 3 ,-1 , 0
  4309.9     .05       0  4715.3     .03       0  4721.3     .05       0
Bank Sta=4715.3,4721.3
XS Rating Curve= 0 ,0
Exp/Cntr=0.3,0.1

Type RM Length L Ch R = 1 ,17515   ,937,937,937
BEGIN DESCRIPTION:
UNT 0484 IN LACR 28.0
END DESCRIPTION:
XS GIS Cut Line= 4
      3682763.41     10652805.86      3682388.38     10652360.52
      3682250.36     10652324.06      3681584.13     10652253.79
#Sta/Elev= 30
  4201.4  296.07  4336.1  293.92  4350.4  295.21  4428.5   295.6    4634  294.04
    4712  290.17  4726.3  290.64  4787.9  289.41  4792.7  289.32  4801.2  287.44
  4813.4  288.41  4823.7  287.06  4886.9  283.76  4957.3  281.73  4967.3   282.2
  4977.4  280.99  4984.5  278.44  4987.2  277.94  4990.5  278.44  5006.7  281.71
  5022.8   282.3  5098.1   285.5  5118.2  287.88  5168.5  290.16  5197.6  292.96
  5238.8  295.18  5295.6  293.73  5359.5  293.94  5510.3  291.76  5596.3  292.77
#Mann= 5 ,-1 , 0
  4201.4     .05       0  4787.9     .16       0  4984.5     .07       0
  4990.5     .16       0  5022.8     .05       0
Bank Sta=4984.5,4990.5
XS Rating Curve= 0 ,0
Exp/Cntr=0.3,0.1

Type RM Length L Ch R = 1 ,16578   ,774,774,774
BEGIN DESCRIPTION:
UNT 0484 IN LACR 27.0
END DESCRIPTION:
XS GIS Cut Line= 2
      3682973.61     10651855.88      3682094.04     10651678.93
#Sta/Elev= 30
  4535.4  292.49  4541.8  292.04  4638.4  291.34  4682.3  290.33  4689.2   289.2
  4733.3  287.79  4745.2  286.74  4774.1  286.09  4804.7   284.2  4886.3  281.82
  4937.3  279.76  4967.9  279.57  4988.3  277.14  4991.3   274.1  4994.1   273.6
  4997.3   274.1  4999.4  277.97  5008.7  274.76  5018.9  276.85  5029.1  278.09
  5039.3  277.92  5050.3  280.06  5059.7  280.02  5120.9  283.17  5192.3  285.45
  5222.9   287.2  5248.6  287.63  5273.9  289.39  5355.5  291.85  5432.6  290.85
#Mann= 3 ,-1 , 0
  4535.4     .05       0  4991.3     .03       0  4997.3     .05       0
Bank Sta=4991.3,4997.3
XS Rating Curve= 0 ,0
Exp/Cntr=0.3,0.1

Type RM Length L Ch R = 1 ,15804   ,331,331,331
BEGIN DESCRIPTION:
Mapping XS 94f315de
END DESCRIPTION:
XS GIS Cut Line= 3
      3682996.17      10651578.1      3682601.24     10651291.66
      3681933.77     10651187.64
#Sta/Elev= 30
  4392.3  291.32  4496.3  291.85  4602.9   289.5  4610.4  287.63  4632.3  286.63
  4688.8  285.84  4789.3  282.21  4839.5  278.97  4879.2  278.32  4902.1  278.73
  4962.8  276.07  4982.6  277.45  4987.6  276.71  4990.2  273.28  4992.9  272.78
  4996.2  273.28  5003.3  274.31  5013.4  278.78  5050.2  280.82  5181.2  284.99
  5186.2  284.18    5244  285.51  5357.5  285.53  5392.5  284.08    5398  284.12
  5408.1  288.83  5418.2  286.14  5428.3  285.09    5492  286.34  5555.7  288.59
#Mann= 7 ,-1 , 0
  4392.3     .05       0  4879.2     .16       0  4990.2     .07       0
  4996.2     .16       0  5050.2     .05       0  5392.5     .16       0
    5492     .05       0
Bank Sta=4990.2,4996.2
XS Rating Curve= 0 ,0
Exp/Cntr=0.3,0.1

Type RM Length L Ch R = 1 ,15473   ,610,610,610
BEGIN DESCRIPTION:
UNT 0484 IN LACR 26.0
END DESCRIPTION:
XS GIS Cut Line= 3
      3682957.13     10651434.88      3682614.26     10651148.43
      3681894.17     10650810.07
#Sta/Elev= 30
    4396  292.19  4485.4  290.91    4496  290.68  4567.9  289.25  4744.9  281.81
  4806.2  280.88  4842.6  278.67  4958.4  276.77    4966  274.75  4974.1  275.41
  4994.3  275.23  4999.6  272.41  5002.4  271.91  5005.6  272.41  5011.6  274.79
  5017.1  273.46  5024.7  275.85  5034.4  276.61  5057.2  276.63  5062.7  272.96
  5068.9  275.53  5085.5  277.37  5188.8  277.21  5288.1  277.42  5296.1  277.57
  5415.8  278.63  5510.9  282.19  5539.4  282.38  5618.2  285.12  5638.4  285.53
#Mann= 13 ,-1 , 0
    4396     .05       0  4485.4     .08       0    4496     .05       0
  4806.2     .08       0  4974.1     .05       0  4999.6     .03       0
  5005.6     .05       0  5188.8     .16       0  5288.1     .05       0
  5296.1     .08       0  5510.9     .16       0  5539.4     .08       0
  5618.2     .16       0
Bank Sta=4999.6,5005.6
XS Rating Curve= 0 ,0
Exp/Cntr=0.3,0.1

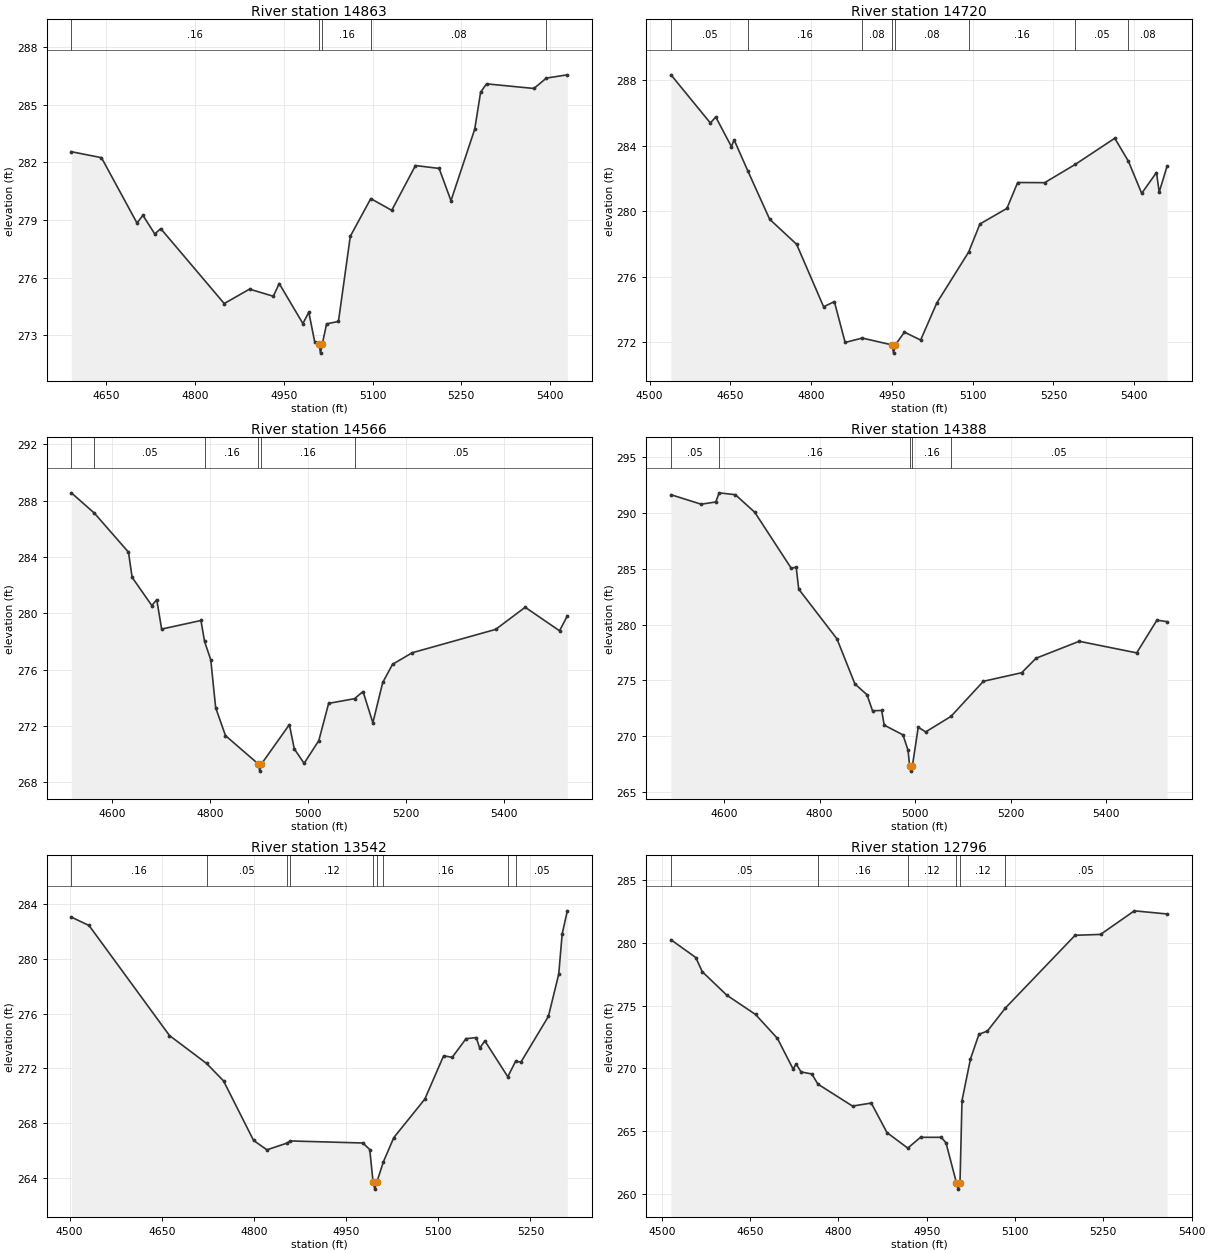
Type RM Length L Ch R = 1 ,14863   ,143,143,143
BEGIN DESCRIPTION:
Mapping XS 4116d743
END DESCRIPTION:
XS GIS Cut Line= 2
      3682520.44     10650746.51      3681683.23     10650710.11
#Sta/Elev= 30
  4591.1  282.55    4642  282.24    4702  278.84    4712  279.24  4732.1  278.27
  4742.1  278.55  4849.4  274.65  4892.2   275.4  4932.3  275.03  4942.3  275.69
  4982.3  273.61  4992.3   274.2  5002.3  272.65  5009.3  272.57  5012.1  272.07
  5015.3  272.57  5022.3  273.59  5042.4  273.72  5062.4  278.15    5097  280.11
  5132.4   279.5  5172.5  281.83  5212.5  281.68  5232.5     280  5272.6  283.72
  5282.6  285.65  5292.6  286.08  5372.7  285.84  5393.6  286.38  5429.1  286.55
#Mann= 5 ,-1 , 0
  4591.1     .16       0  5009.3     .07       0  5015.3     .16       0
    5097     .08       0  5393.6     .16       0
Bank Sta=5009.3,5015.3
XS Rating Curve= 0 ,0
Exp/Cntr=0.3,0.1

Type RM Length L Ch R = 1 ,14720   ,154,154,154
BEGIN DESCRIPTION:
UNT 0484 IN LACR 25.0
END DESCRIPTION:
XS GIS Cut Line= 2
       3682572.6     10650611.09      3681652.69     10650564.32
#Sta/Elev= 30
  4539.7  288.33  4612.8  285.39  4622.8  285.76  4651.9  283.95  4656.9  284.36
  4682.5  282.46  4722.9  279.52    4773  277.99  4823.1  274.18  4843.1  274.49
  4863.1     272  4894.8  272.27  4950.2  271.85    4953  271.35  4956.2  271.85
  4973.2  272.63  5003.3  272.15  5033.3  274.41  5092.5  277.52  5113.4  279.23
  5163.5  280.18  5183.5  281.76  5233.6  281.75  5290.2  282.86  5363.8  284.46
  5389.1  283.06  5413.8   281.1  5441.3  282.37  5446.3  281.17  5460.8  282.74
#Mann= 8 ,-1 , 0
  4539.7     .05       0  4682.5     .16       0  4894.8     .08       0
  4950.2     .07       0  4956.2     .08       0  5092.5     .16       0
  5290.2     .05       0  5389.1     .08       0
Bank Sta=4950.2,4956.2
XS Rating Curve= 0 ,0
Exp/Cntr=0.3,0.1

Type RM Length L Ch R = 1 ,14566   ,178,178,178
BEGIN DESCRIPTION:
UNT 0484 IN LACR 24.0
END DESCRIPTION:
XS GIS Cut Line= 2
      3682593.39     10650470.47      3681583.77     10650423.63
#Sta/Elev= 30
  4517.7  288.55  4564.6  287.11  4634.1  284.34  4641.6  282.55  4681.7  280.55
  4691.7  280.97  4701.7  278.88  4781.8  279.49  4789.2     278  4801.8   276.7
  4811.8   273.3  4831.8  271.32  4898.9   269.3  4901.6   268.8  4904.9   269.3
    4962   272.1    4972  270.38    4992  269.35    5022  270.97    5042  273.61
  5094.7  273.94  5112.1  274.45  5132.1  272.23  5152.2  275.09  5172.2  276.38
  5212.2   277.2  5382.4  278.86  5442.5  280.43  5512.5  278.76  5528.4  279.82
#Mann= 6 ,-1 , 0
  4517.7     .08       0  4564.6     .05       0  4789.2     .16       0
  4898.9     .07       0  4904.9     .16       0  5094.7     .05       0
Bank Sta=4898.9,4904.9
XS Rating Curve= 0 ,0
Exp/Cntr=0.3,0.1

Type RM Length L Ch R = 1 ,14388   ,846,846,846
BEGIN DESCRIPTION:
UNT 0484 IN LACR 23.0
END DESCRIPTION:
XS GIS Cut Line= 3
      3682526.42     10650154.78      3681940.46     10650365.73
      3681526.41     10650396.98
#Sta/Elev= 30
    4489  291.65    4552   290.8  4582.7     291  4589.8  291.82  4623.8  291.65
  4664.2  290.08  4740.7  285.05    4751  285.15  4756.3  283.18  4836.3  278.72
  4873.8  274.68  4899.2   273.7  4910.7  272.27  4929.9  272.29  4935.2  270.98
  4974.5   270.1  4985.1  268.72  4988.3  267.35    4991  266.85  4994.3  267.35
  5006.4  270.79    5022  270.37  5074.9  271.76  5142.7  274.91  5222.9  275.68
    5253  276.98  5343.3   278.5  5463.6  277.46    5506   280.4    5527  280.26
#Mann= 5 ,-1 , 0
    4489     .05       0  4589.8     .16       0  4988.3     .07       0
  4994.3     .16       0  5074.9     .05       0
Bank Sta=4988.3,4994.3
XS Rating Curve= 0 ,0
Exp/Cntr=0.3,0.1

Type RM Length L Ch R = 1 ,13542   ,746,746,746
BEGIN DESCRIPTION:
UNT 0484 IN LACR 22.0
END DESCRIPTION:
XS GIS Cut Line= 3
      3681749.57     10649760.21      3681349.61     10650010.19
      3681199.59     10650310.22
#Sta/Elev= 30
  4502.9  283.05  4531.7  282.44  4662.6   274.4    4723  272.36  4750.5  271.09
  4799.4  266.74  4821.2  266.05  4854.3  266.55  4858.9   266.7  4977.3  266.55
  4988.5  266.07  4993.9  263.68  4996.7  263.18  4999.9  263.68  5010.7  265.18
  5027.7  266.95    5078  269.75  5108.7  272.92  5122.7  272.81  5145.1  274.17
  5161.8  274.25  5167.4  273.48  5175.8  274.01  5213.1  271.39  5225.8  272.52
  5234.5  272.46  5279.2   275.8    5296  278.89  5301.6  281.83    5310  283.51
#Mann= 9 ,-1 , 0
  4502.9     .16       0    4723     .05       0  4854.3     .07       0
  4858.9     .12       0  4993.9     .07       0  4999.9     .12       0
  5010.7     .16       0  5213.1     .12       0  5225.8     .05       0
Bank Sta=4993.9,4999.9
XS Rating Curve= 0 ,0
Exp/Cntr=0.3,0.1

Type RM Length L Ch R = 1 ,12796   ,399,399,399
BEGIN DESCRIPTION:
UNT 0484 IN LACR 21.0
END DESCRIPTION:
XS GIS Cut Line= 3
      3681449.65     10649560.18      3681085.33      10649679.1
       3680726.2     10649965.36
#Sta/Elev= 30
  4515.6  280.25  4557.7  278.84  4568.7  277.71  4610.3  275.84  4659.2   274.3
  4696.3   272.4  4722.9  269.96  4728.2  270.35  4736.5  269.72  4754.8  269.56
  4765.1  268.75  4823.9     267  4855.8  267.24  4882.4  264.89  4917.8  263.65
  4939.4  264.51  4974.6  264.51  4982.7  264.07  5000.5  260.88  5003.2  260.38
  5006.5  260.88  5009.9  267.44  5024.3  270.76  5038.7  272.72  5053.1  272.98
  5083.7  274.82    5202  280.61  5245.3  280.68  5302.6  282.56  5358.1  282.31
#Mann= 6 ,-1 , 0
  4515.6     .05       0  4765.1     .16       0  4917.8     .12       0
  5000.5     .07       0  5006.5     .12       0  5083.7     .05       0
Bank Sta=5000.5,5006.5
XS Rating Curve= 0 ,0
Exp/Cntr=0.3,0.1

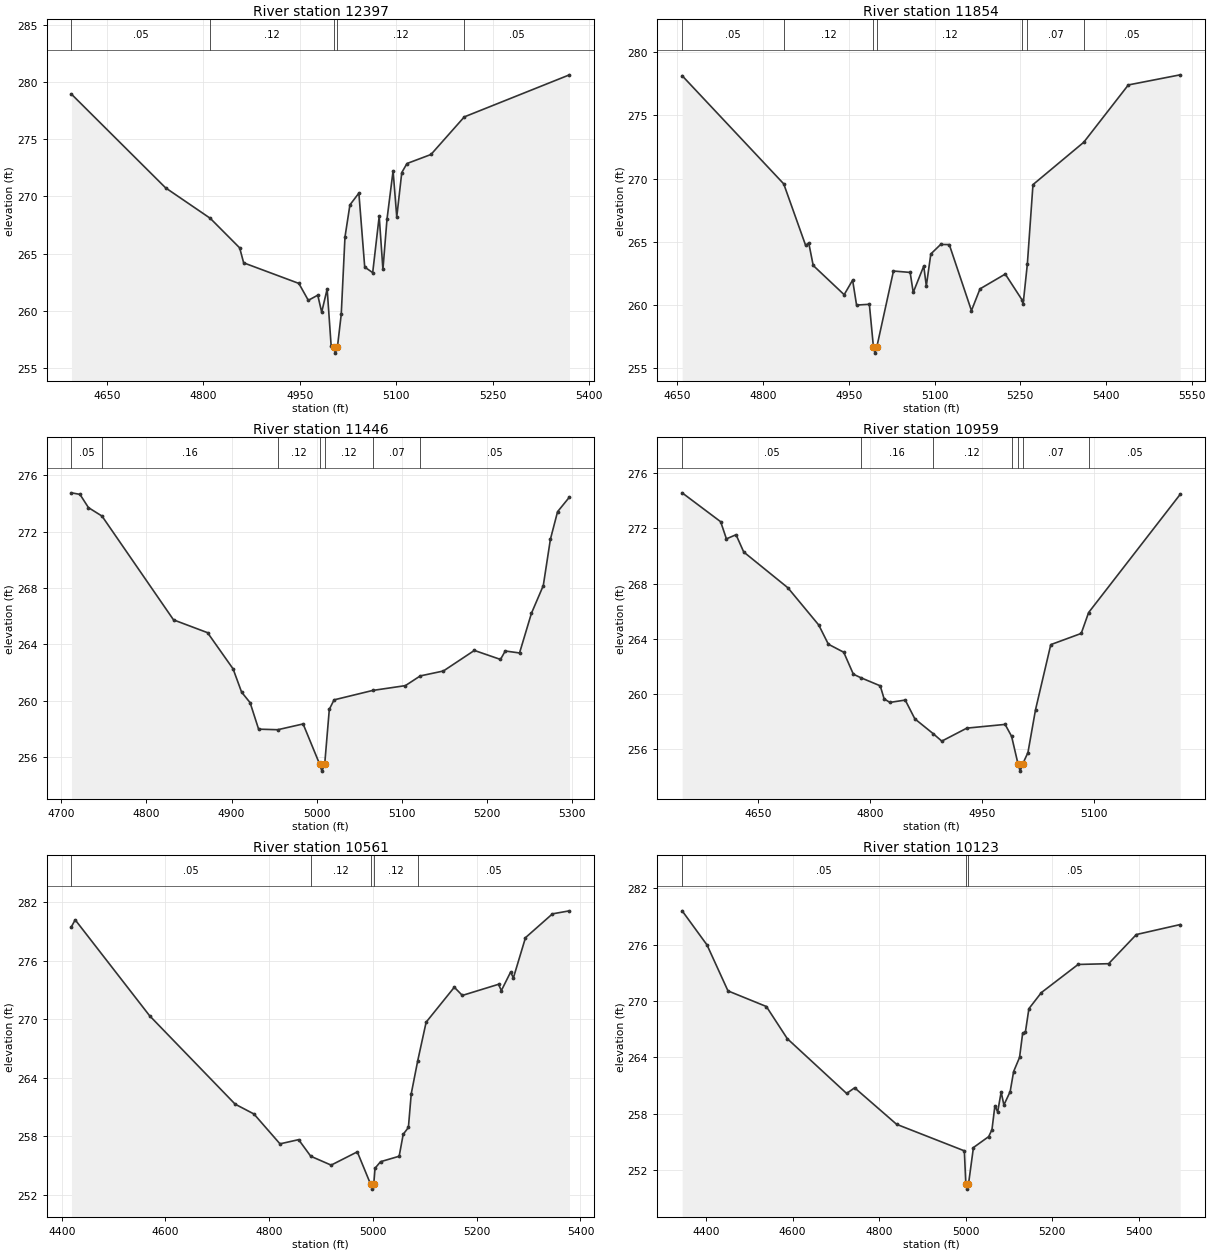
Type RM Length L Ch R = 1 ,12397   ,543,543,543
BEGIN DESCRIPTION:
UNT 0484 IN LACR 20.0
END DESCRIPTION:
XS GIS Cut Line= 3
      3681072.14     10649198.65       3680833.6      10649526.2
      3680513.48     10649709.74
#Sta/Elev= 30
  4594.8  278.95  4741.2  270.75  4810.5  268.09  4856.3   265.5  4862.5  264.19
  4948.3  262.39    4963  260.91  4977.7  261.36  4983.8  259.87  4992.3   261.9
  4998.5  256.93  5002.2  256.79  5004.9  256.29  5008.2  256.79  5014.2  259.68
    5020  266.44  5027.7  269.26  5041.6  270.29  5050.7  263.82  5063.1  263.33
  5073.2  268.26    5079  263.61  5085.3  267.99  5094.8  272.24  5100.5   268.2
  5108.3  272.09  5116.4  272.88  5153.7  273.67  5205.5  276.96    5369  280.64
#Mann= 5 ,-1 , 0
  4594.8     .05       0  4810.5     .12       0  5002.2     .07       0
  5008.2     .12       0  5205.5     .05       0
Bank Sta=5002.2,5008.2
XS Rating Curve= 0 ,0
Exp/Cntr=0.3,0.1

Type RM Length L Ch R = 1 ,11854   ,408,408,408
BEGIN DESCRIPTION:
UNT 0484 IN LACR 19.0
END DESCRIPTION:
XS GIS Cut Line= 3
      3680941.32     10648990.73      3680546.37     10649155.66
      3680134.31     10649320.48
#Sta/Elev= 30
  4658.2  278.13    4836  269.58  4874.4  264.71  4879.8  264.91  4887.6  263.13
  4941.8  260.82  4956.6  261.97  4963.5     260  4985.9  260.06    4993   256.7
  4995.7   256.2    4999   256.7  5028.1  262.69  5057.3  262.58  5062.7     261
  5081.1  263.08  5085.6  261.51  5093.5  264.04  5110.7  264.79  5125.8  264.78
  5164.6  259.56  5179.6  261.28  5223.8  262.45    5253  260.42    5255  260.05
  5262.5  263.26  5272.3  269.52  5361.2  272.87  5439.2   277.4    5530   278.2
#Mann= 7 ,-1 , 0
  4658.2     .05       0    4836     .12       0    4993     .07       0
    4999     .12       0    5253     .05       0  5262.5     .07       0
  5361.2     .05       0
Bank Sta=4993,4999
XS Rating Curve= 0 ,0
Exp/Cntr=0.3,0.1

Type RM Length L Ch R = 1 ,11446   ,487,487,487
BEGIN DESCRIPTION:
UNT 0484 IN LACR 18.0
END DESCRIPTION:
XS GIS Cut Line= 3
      3680849.57     10648760.19      3680599.61     10648760.19
      3680299.58      10648910.2
#Sta/Elev= 30
  4711.8  274.75  4721.8  274.64  4731.8   273.7  4747.7   273.1  4831.8  265.73
  4871.8  264.82  4901.8  262.25  4911.8   260.6  4921.8  259.85  4931.8  257.97
  4954.3  257.93  4984.1  258.34  5003.5  255.49  5006.2  254.99  5009.5  255.49
  5014.9  259.38  5020.5  260.05    5066  260.72  5104.3  261.06  5121.8  261.75
    5149   262.1  5185.4  263.56  5216.1  262.92  5221.7  263.52  5238.5  263.38
  5252.5   266.2  5266.4  268.16  5274.8  271.46  5283.2  273.41  5297.2  274.45
#Mann= 7 ,-1 , 0
  4711.8     .05       0  4747.7     .16       0  4954.3     .12       0
  5003.5     .07       0  5009.5     .12       0    5066     .07       0
  5121.8     .05       0
Bank Sta=5003.5,5009.5
XS Rating Curve= 0 ,0
Exp/Cntr=0.3,0.1

Type RM Length L Ch R = 1 ,10959   ,398,398,398
BEGIN DESCRIPTION:
UNT 0484 IN LACR 17.0
END DESCRIPTION:
XS GIS Cut Line= 3
      3680849.62     10648560.19      3680449.61     10648460.19
      3680199.59     10648410.18
#Sta/Elev= 30
  4548.3  274.56  4599.9  272.47  4607.6  271.23  4620.5  271.53  4630.8  270.28
    4690  267.69  4731.3     265  4744.2  263.61  4764.8  263.03  4777.7  261.44
    4788  261.18  4813.7   260.6  4818.9  259.66  4826.6   259.4  4847.2  259.57
  4860.1  258.21  4884.4  257.15  4896.2   256.6  4929.7  257.54    4981  257.81
  4989.7  256.95  4998.4  254.93  5001.2  254.43  5004.4  254.93  5011.6  255.77
  5021.8  258.88  5042.2  263.58    5083  264.39  5092.9   265.9  5215.6  274.45
#Mann= 7 ,-1 , 0
  4548.3     .05       0    4788     .16       0  4884.4     .12       0
  4989.7     .07       0  4998.4     .07       0  5004.4     .07       0
  5092.9     .05       0
Bank Sta=4998.4,5004.4
XS Rating Curve= 0 ,0
Exp/Cntr=0.3,0.1

Type RM Length L Ch R = 1 ,10561   ,438,438,438
BEGIN DESCRIPTION:
UNT 0484 IN LACR 16.0
END DESCRIPTION:
XS GIS Cut Line= 3
      3681010.05     10648449.62       3680598.6     10648168.38
      3680176.77      10647980.9
#Sta/Elev= 30
  4418.8  279.49    4426   280.2  4569.6  270.36  4734.3  261.31  4770.6   260.3
  4820.8  257.24  4856.7  257.67  4880.1  255.97  4919.4  255.06  4969.8  256.42
  4995.5   253.1  4998.3   252.6  5001.5   253.1    5004  254.74  5014.6  255.41
  5050.5  255.97  5058.3  258.22  5068.3  258.92  5073.8  262.38  5086.3  265.76
  5102.5  269.71  5156.8  273.29  5172.3  272.45    5242  273.59  5247.5  272.95
  5265.3  274.84  5270.7  274.25    5294  278.37    5346  280.81  5378.8  281.12
#Mann= 5 ,-1 , 0
  4418.8     .05       0  4880.1     .12       0  4995.5     .07       0
  5001.5     .12       0  5086.3     .05       0
Bank Sta=4995.5,5001.5
XS Rating Curve= 0 ,0
Exp/Cntr=0.3,0.1

Type RM Length L Ch R = 1 ,10123   ,278,278,278
BEGIN DESCRIPTION:
Mapping XS d5446243
END DESCRIPTION:
XS GIS Cut Line= 3
      3681145.47     10648460.03      3680931.94      10647928.8
      3680478.79     10647569.41
#Sta/Elev= 30
  4344.6  279.58  4402.1  275.95  4450.5  271.07  4539.2  269.41  4587.6  265.99
  4724.7  260.17  4743.2  260.77  4840.2  256.89  4996.7  254.07  5000.2   250.5
    5003     250  5006.2   250.5  5017.7  254.42  5052.9  255.58  5060.5  256.31
  5067.3  258.85  5073.7  258.21  5081.8  260.32  5088.1  258.94  5102.6  260.37
  5110.6   262.5  5124.3     264  5131.4  266.55  5137.8   266.7  5145.9  269.18
  5174.7  270.89  5259.6  273.88  5330.1  273.96  5394.2  277.06  5495.5  278.12
#Mann= 3 ,-1 , 0
  4344.6     .05       0  5000.2     .03       0  5006.2     .05       0
Bank Sta=5000.2,5006.2
XS Rating Curve= 0 ,0
Exp/Cntr=0.3,0.1

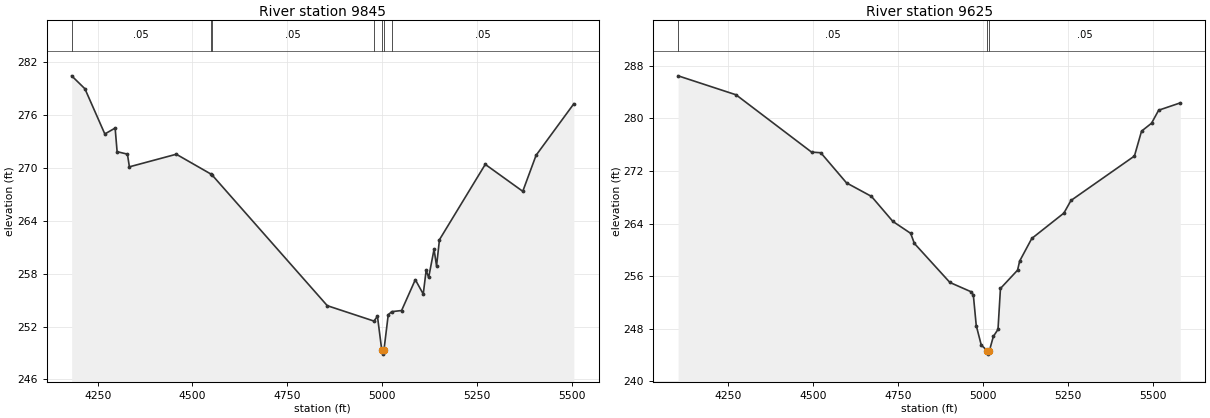
Type RM Length L Ch R = 1 ,9845    ,220,220,220
BEGIN DESCRIPTION:
UNT 0484 IN LACR 15.0
END DESCRIPTION:
XS GIS Cut Line= 3
      3681239.22     10648423.57      3681020.48     10647725.67
      3680636.19     10647273.87
#Sta/Elev= 30
  4181.3  280.46  4216.3  278.99  4268.8  273.86    4296  274.53  4301.2  271.85
  4328.4  271.57  4333.6  270.13  4457.3  271.56  4548.2  269.32  4551.4  269.22
  4855.5  254.37  4978.8  252.62  4987.8  253.18  4999.1  249.37  5001.8  248.87
  5005.1  249.37  5016.3  253.34  5025.5  253.69  5051.5  253.82  5087.7  257.32
  5108.6  255.69  5116.3  258.38  5122.9  257.57  5137.1  260.77  5143.7  258.88
  5151.4  261.86  5272.2  270.41  5371.1  267.35  5406.2  271.44  5505.8  277.29
#Mann= 7 ,-1 , 0
  4181.3     .05       0  4548.2     .08       0  4551.4     .05       0
  4978.8     .08       0  4999.1     .07       0  5005.1     .08       0
  5025.5     .05       0
Bank Sta=4999.1,5005.1
XS Rating Curve= 0 ,0
Exp/Cntr=0.3,0.1

Type RM Length L Ch R = 1 ,9625    ,433,433,433
BEGIN DESCRIPTION:
UNT 0484 IN LACR 14.0
END DESCRIPTION:
XS GIS Cut Line= 3
      3681411.09     10648402.72       3681161.1     10647605.88
      3680786.17     10647085.14
#Sta/Elev= 30
  4103.6   286.5  4273.9  283.61    4496  274.88  4523.2  274.78  4598.8  270.19
  4672.2  268.13  4735.1  264.32  4787.5   262.5  4798.3  260.97  4902.8  255.02
  4965.6  253.59  4971.8  253.09  4980.3  248.46    4995  245.49  5012.9   244.6
  5015.7   244.1  5018.9   244.6  5030.6  246.79  5044.3  247.87  5051.5   254.1
  5101.8  256.89    5108  258.28  5143.6  261.72  5238.1  265.59  5258.9  267.51
  5445.5  274.28  5466.4  278.07  5495.8  279.28  5516.7  281.26  5580.4  282.38
#Mann= 3 ,-1 , 0
  4103.6     .05       0  5012.9     .03       0  5018.9     .05       0
Bank Sta=5012.9,5018.9
XS Rating Curve= 0 ,0
Exp/Cntr=0.3,0.1