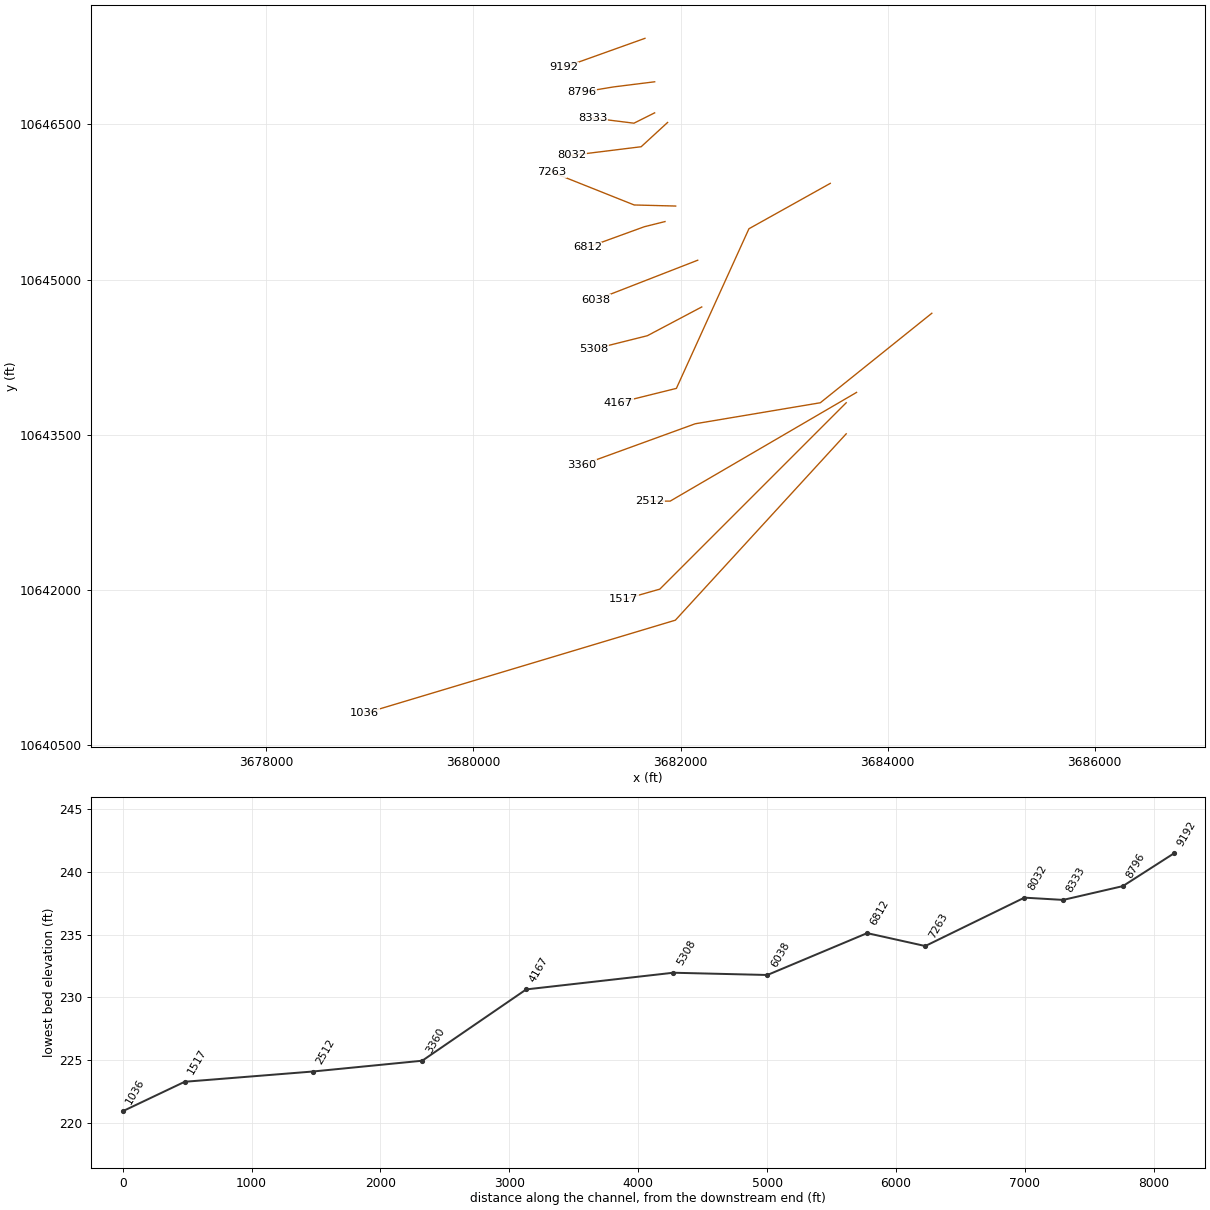
HEC-RAS study UNT 0484 IN LACR.prj: UNT 0484 IN LACR Base Level Engineering

--- UNT 0484 IN LACR.g01 (geometry) --- (continued)

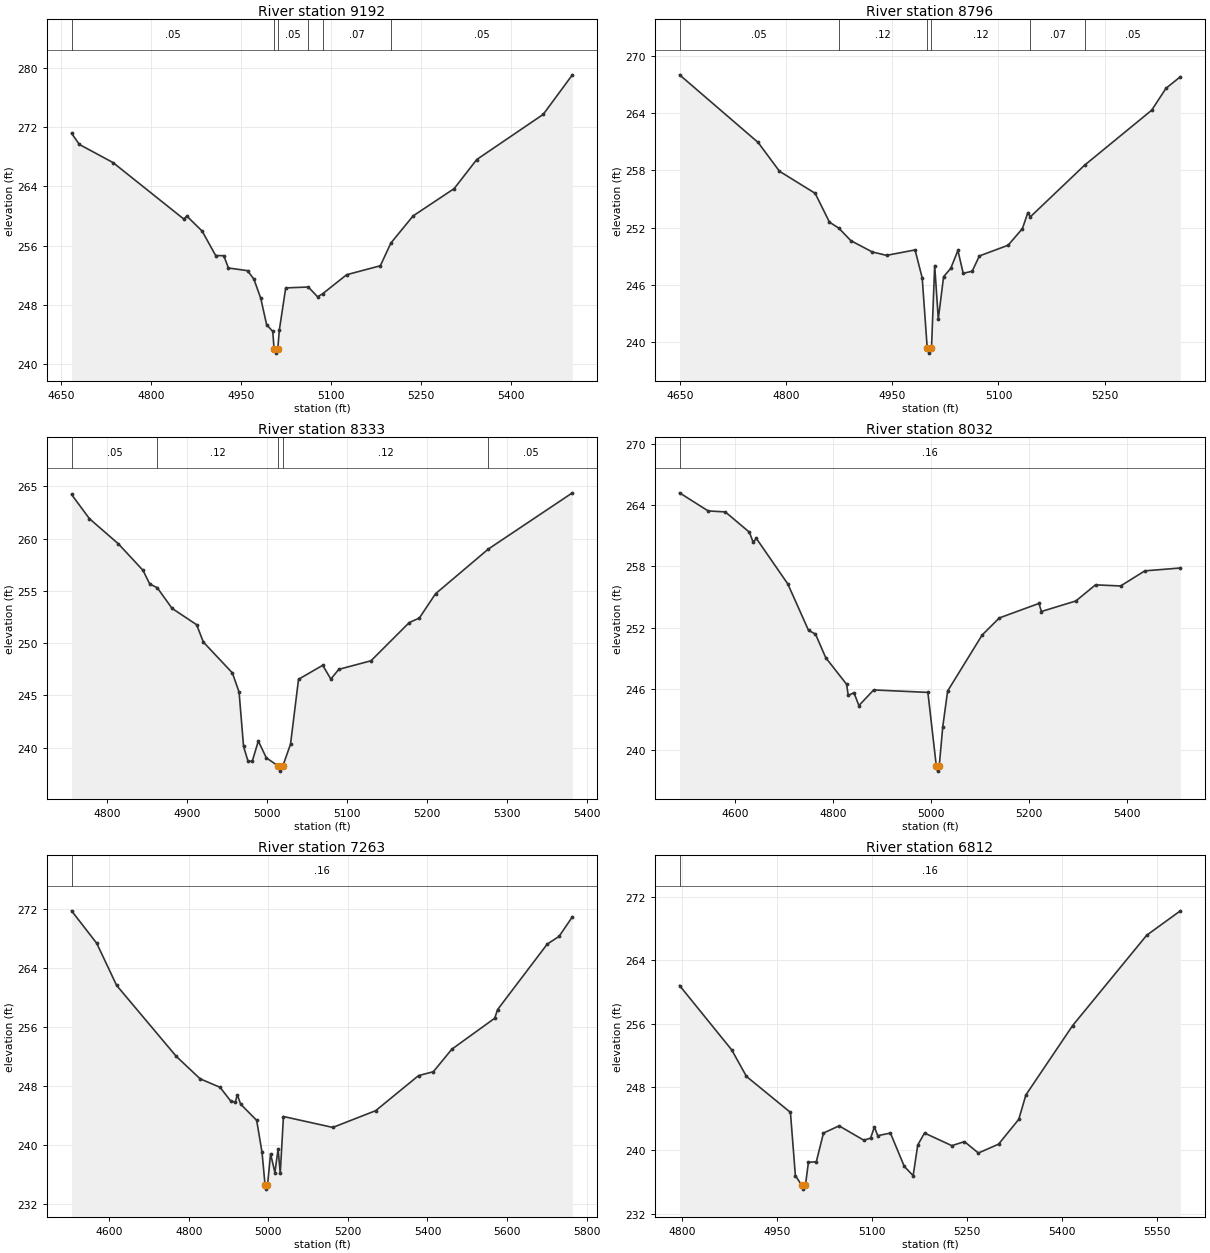
Type RM Length L Ch R = 1 ,9192    ,396,396,396
BEGIN DESCRIPTION:
UNT 0484 IN LACR 13.0
END DESCRIPTION:
XS GIS Cut Line= 2
      3681655.89     10647329.84      3680869.47      10647048.6
#Sta/Elev= 30
  4666.9  271.17  4679.8  269.66    4736  267.21  4853.9  259.59  4859.2  259.97
  4884.6  257.96  4907.2  254.65  4920.7  254.63  4928.5  252.97  4960.3  252.61
  4970.9  251.47  4982.3   248.9  4992.2  245.31  5002.4   244.4  5004.7  241.97
  5007.5  241.47  5010.7  241.97  5013.4   244.6    5024  250.28  5061.7   250.4
  5077.1  249.08  5085.6  249.49  5125.6  252.06  5181.8  253.27  5199.4  256.34
  5236.4     260  5304.9  263.69  5342.6  267.62  5453.5  273.72  5502.1  279.06
#Mann= 6 ,-1 , 0
  4666.9     .05       0  5004.7     .03       0  5010.7     .05       0
  5061.7     .12       0  5085.6     .07       0  5199.4     .05       0
Bank Sta=5004.7,5010.7
XS Rating Curve= 0 ,0
Exp/Cntr=0.3,0.1

Type RM Length L Ch R = 1 ,8796    ,463,463,463
BEGIN DESCRIPTION:
UNT 0484 IN LACR 12.0
END DESCRIPTION:
XS GIS Cut Line= 3
      3681749.64     10646910.19      3681349.61     10646860.19
      3681049.59     10646810.19
#Sta/Elev= 30
  4649.6  268.01  4760.5  260.93  4790.7  257.91  4841.1   255.6  4861.3  252.58
  4874.7  251.94  4891.5  250.64  4921.7  249.46  4941.9   249.1  4982.2  249.67
  4992.3  246.73  4999.4  239.36  5002.1  238.86  5005.4  239.36  5009.9  248.03
    5015  242.44  5022.5  246.87  5032.6  247.74  5042.7  249.61  5050.2  247.22
  5062.9  247.44    5073  249.04  5113.6  250.16  5133.8   251.9  5141.5  253.58
  5145.1  253.14  5221.7  258.55  5316.3   264.3  5336.6   266.6  5356.9  267.81
#Mann= 6 ,-1 , 0
  4649.6     .05       0  4874.7     .12       0  4999.4     .07       0
  5005.4     .12       0  5145.1     .07       0  5221.7     .05       0
Bank Sta=4999.4,5005.4
XS Rating Curve= 0 ,0
Exp/Cntr=0.3,0.1

Type RM Length L Ch R = 1 ,8333    ,301,301,301
BEGIN DESCRIPTION:
UNT 0484 IN LACR 11.0
END DESCRIPTION:
XS GIS Cut Line= 3
      3681749.59     10646610.18      3681549.61     10646510.19
       3681149.6     10646560.19
#Sta/Elev= 30
  4755.4  264.23  4777.7  261.92  4814.1   259.5  4844.8  256.97  4853.2  255.67
  4862.6  255.31  4881.2  253.33  4911.9  251.77  4920.3  250.11  4956.6  247.16
    4965  245.33  4970.6  240.12  4976.2  238.71  4981.5  238.71  4989.1  240.64
  4999.1  239.03  5013.8  238.26  5016.5  237.76  5019.8  238.26  5029.4  240.35
  5039.4  246.55  5069.7  247.89  5079.8  246.57  5089.8   247.5  5130.1  248.32
    5178  251.98  5190.6  252.41  5210.8  254.73  5276.9  259.01  5382.1  264.39
#Mann= 5 ,-1 , 0
  4755.4     .05       0  4862.6     .12       0  5013.8     .07       0
  5019.8     .12       0  5276.9     .05       0
Bank Sta=5013.8,5019.8
XS Rating Curve= 0 ,0
Exp/Cntr=0.3,0.1

Type RM Length L Ch R = 1 ,8032    ,769,769,769
BEGIN DESCRIPTION:
UNT 0484 IN LACR 10.0
END DESCRIPTION:
XS GIS Cut Line= 3
      3681874.63     10646517.33      3681619.44     10646282.97
      3680947.57     10646199.63
#Sta/Elev= 30
  4485.9  265.19  4544.2  263.42  4579.4  263.32  4628.7  261.33  4636.1  260.37
  4642.9  260.72    4707  256.28  4749.5  251.72  4763.7  251.36  4784.7  249.04
  4827.2  246.45  4830.7  245.35  4842.3  245.62  4852.4  244.36  4882.6  245.89
  4993.4  245.65  5010.6  238.44  5013.3  237.94  5016.6  238.44  5023.7  242.25
  5033.7  245.78  5104.3  251.27  5139.4  252.94  5220.4  254.36  5225.4  253.57
  5295.7   254.6    5336  256.18  5387.2  256.07  5436.8  257.55  5509.4  257.83
#Mann= 1 ,-1 , 0
  4485.9     .16       0
Bank Sta=5010.6,5016.6
XS Rating Curve= 0 ,0
Exp/Cntr=0.3,0.1

Type RM Length L Ch R = 1 ,7263    ,451,451,451
BEGIN DESCRIPTION:
UNT 0484 IN LACR 9.0
END DESCRIPTION:
XS GIS Cut Line= 3
      3681952.75     10645710.05      3681551.73     10645720.47
      3680754.88     10646038.16
#Sta/Elev= 30
  4505.4  271.75  4568.6  267.36  4618.6  261.66  4768.6  252.05  4828.6  249.01
  4878.7  247.86  4905.1  246.03  4916.8  245.82  4922.1  246.85  4930.4  245.58
  4970.7  243.39  4984.2  239.06  4991.9  234.58  4994.7  234.08  4997.9  234.58
  5005.7  238.85  5016.5  236.33  5024.6  239.51    5030  236.22    5038  243.91
  5162.1  242.43  5269.9   244.7  5377.7  249.45  5414.8  249.97  5461.3  253.02
  5569.1  257.21  5576.3  258.38  5701.2  267.25  5730.9  268.29  5764.4  270.94
#Mann= 1 ,-1 , 0
  4505.4     .16       0
Bank Sta=4991.9,4997.9
XS Rating Curve= 0 ,0
Exp/Cntr=0.3,0.1

Type RM Length L Ch R = 1 ,6812    ,774,774,774
BEGIN DESCRIPTION:
UNT 0484 IN LACR 8.0
END DESCRIPTION:
XS GIS Cut Line= 3
      3681849.62     10645560.19      3681649.61     10645510.19
      3681099.61     10645310.19
#Sta/Elev= 30
  4796.1  260.82  4878.6  252.68  4901.8  249.34  4971.3   244.8  4979.1  236.83
    4989  235.61  4991.7  235.11    4995  235.61  4999.7  238.49  5012.2  238.57
  5023.5  242.19  5048.2   243.1  5087.4  241.28    5098  241.56    5104  242.96
  5109.3  241.86  5129.3  242.19  5151.2  237.98  5165.2  236.81  5172.5  240.69
  5183.2  242.19  5226.4   240.6  5246.3  241.11  5268.3  239.67  5300.2  240.79
  5332.1  243.92  5343.4  247.01  5417.3  255.77  5534.3  267.17  5587.5  270.25
#Mann= 1 ,-1 , 0
  4796.1     .16       0
Bank Sta=4989,4995
XS Rating Curve= 0 ,0
Exp/Cntr=0.3,0.1

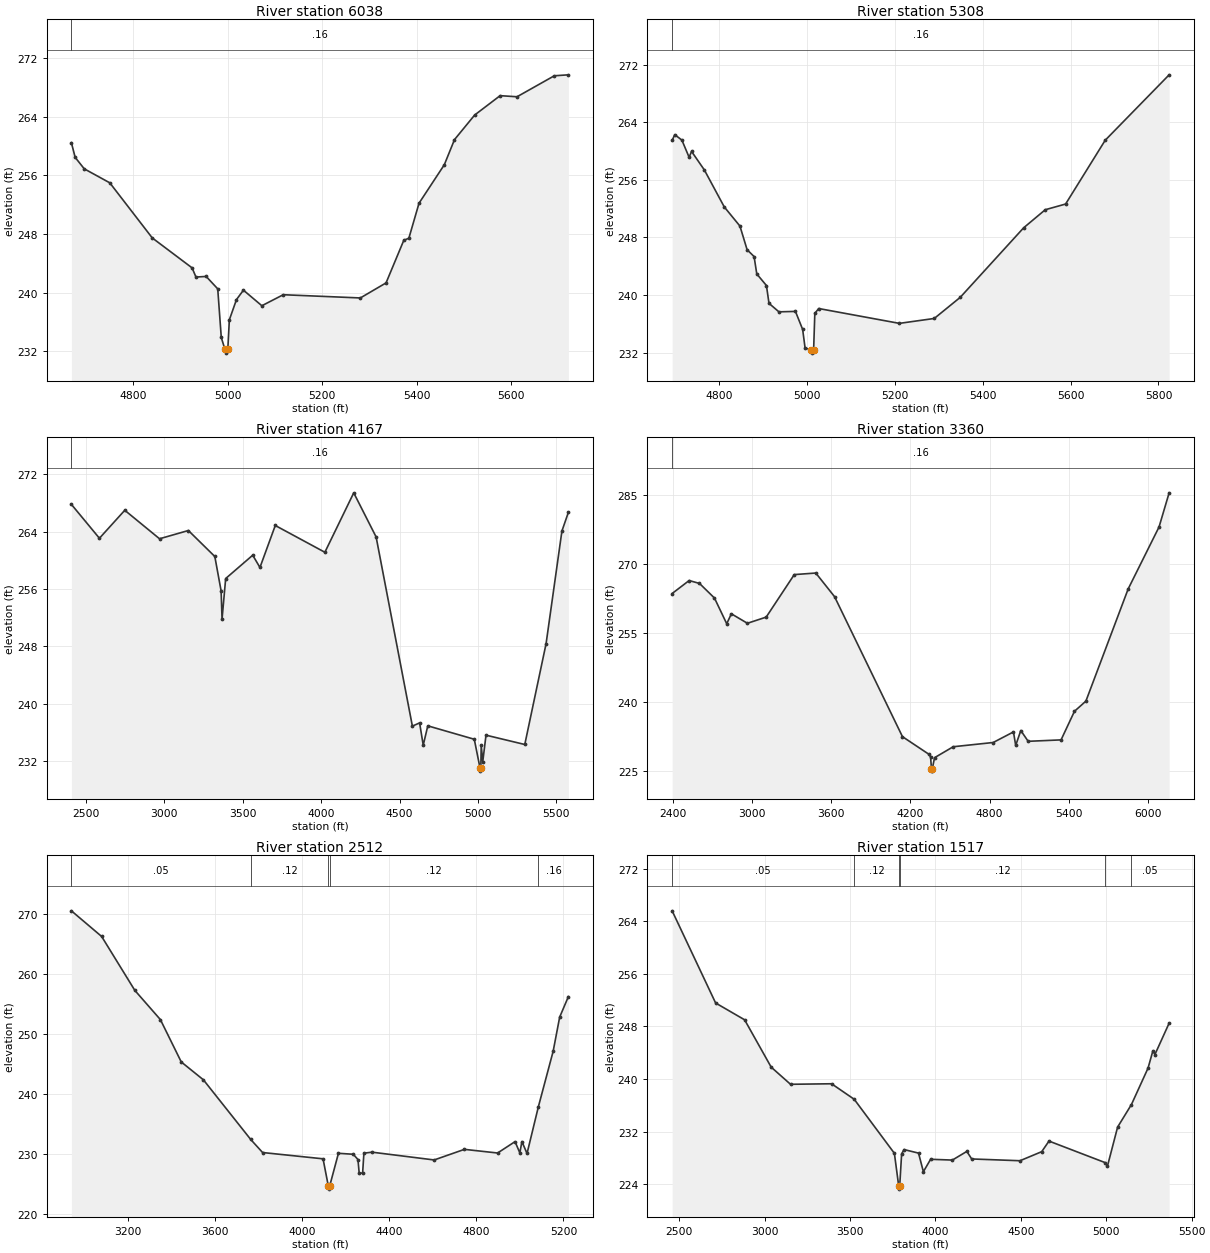
Type RM Length L Ch R = 1 ,6038    ,730,730,730
BEGIN DESCRIPTION:
UNT 0484 IN LACR 7.0
END DESCRIPTION:
XS GIS Cut Line= 2
      3682165.33     10645186.84      3681184.93     10644805.09
#Sta/Elev= 30
    4669  260.45    4677  258.45  4696.2  256.89  4750.3  254.98  4840.2  247.47
  4924.5  243.39  4932.7  242.14  4954.3  242.22  4978.8  240.53  4986.3   233.9
  4994.1  232.27  4996.8  231.77  5000.1  232.27  5003.4  236.31  5018.5  239.07
  5033.2  240.35  5072.2  238.23  5117.5  239.73  5280.7  239.29  5335.1  241.34
  5372.7  247.15  5383.4  247.43  5404.9   252.2  5458.5  257.45    5480  260.87
  5522.7  264.22  5576.6  266.86  5612.4  266.71  5691.3  269.57  5721.1   269.7
#Mann= 1 ,-1 , 0
    4669     .16       0
Bank Sta=4994.1,5000.1
XS Rating Curve= 0 ,0
Exp/Cntr=0.3,0.1

Type RM Length L Ch R = 1 ,5308    ,1141,1141,1141
BEGIN DESCRIPTION:
UNT 0484 IN LACR 6.0
END DESCRIPTION:
XS GIS Cut Line= 3
      3682204.44     10644735.47      3681679.26     10644457.69
      3681158.41     10644327.48
#Sta/Elev= 30
  4693.3  261.46  4699.2  262.27  4715.5  261.51  4731.9  259.13  4737.5  259.94
  4766.6  257.37  4811.9  252.24  4847.6  249.58  4863.9   246.3  4879.8  245.35
  4885.9  242.94  4907.9  241.33  4913.7  238.86  4936.3  237.68  4973.9  237.74
  4990.3  235.24  4995.9  232.64  5009.3  232.45    5012  231.95  5015.3  232.45
    5018  237.46  5026.8  238.14  5210.4  236.08  5289.8  236.76  5348.9  239.69
  5493.2  249.34  5542.4  251.85  5588.7  252.64  5678.8  261.49  5824.3  270.57
#Mann= 1 ,-1 , 0
  4693.3     .16       0
Bank Sta=5009.3,5015.3
XS Rating Curve= 0 ,0
Exp/Cntr=0.3,0.1

Type RM Length L Ch R = 1 ,4167    ,807,807,807
BEGIN DESCRIPTION:
UNT 0484 IN LACR 5.0
END DESCRIPTION:
XS GIS Cut Line= 4
      3683445.71     10645929.02      3682660.16     10645490.68
       3681959.5       10643949.      3681399.65      10643810.2
#Sta/Elev= 30
    2407  267.78  2585.8  263.06  2747.5  266.96  2969.2  262.99  3153.1  264.14
  3321.8  260.52    3362  255.72  3367.9  251.81    3391  257.45  3563.5   260.7
  3609.6  258.99  3707.4  264.84  4023.7  261.11  4207.8  269.39  4350.6  263.24
  4581.8  236.89  4627.9  237.34    4651  234.23  4680.1  236.93  4976.7  235.06
  5012.6  231.12  5015.3  230.62  5018.6  231.12  5020.7  234.23  5030.8  231.96
  5051.4  235.63  5298.7  234.33  5434.6  248.38  5535.6  264.07  5576.8  266.67
#Mann= 1 ,-1 , 0
    2407     .16       0
Bank Sta=5012.6,5018.6
XS Rating Curve= 0 ,0
Exp/Cntr=0.3,0.1

Type RM Length L Ch R = 1 ,3360    ,848,848,848
BEGIN DESCRIPTION:
UNT 0484 IN LACR 4.0
END DESCRIPTION:
XS GIS Cut Line= 4
      3684426.69     10644674.73      3683349.61     10643810.19
      3682141.38      10643607.2      3681049.62     10643210.19
#Sta/Elev= 30
  2393.7  263.53  2522.7  266.35  2601.1  265.72  2714.7  262.54  2807.5  256.96
  2842.7  259.12  2964.3  257.06  3106.7   258.4  3319.6  267.64  3482.8  267.98
  3625.2  262.84  4139.9  232.42  4342.7  228.55  4353.1  227.98    4360  225.43
  4362.7  224.93    4366  225.43  4383.2  227.85  4524.7  230.23  4827.7  231.15
  4981.5  233.45  4998.4  230.52  5037.1  233.75    5093  231.41  5342.4  231.72
  5444.1  237.94  5530.6  240.14  5851.1  264.52  6085.2  277.99  6161.7  285.41
#Mann= 1 ,-1 , 0
  2393.7     .16       0
Bank Sta=4360,4366
XS Rating Curve= 0 ,0
Exp/Cntr=0.3,0.1

Type RM Length L Ch R = 1 ,2512    ,995,995,995
BEGIN DESCRIPTION:
UNT 0484 IN LACR 3.0
END DESCRIPTION:
XS GIS Cut Line= 3
      3683699.65     10643910.21      3681899.61     10642860.19
      3681699.62     10642860.19
#Sta/Elev= 30
  2938.7  270.53  3077.7  266.25  3230.2  257.25  3347.7  252.37  3443.6   245.3
  3545.3  242.32  3762.8  232.36  3817.4  230.18  4095.2  229.13  4119.5  224.57
  4122.3  224.07  4125.5  224.57  4165.9  230.05  4234.1  229.89  4255.6  229.01
  4261.4  226.68  4277.1  226.78  4282.9  230.07  4320.1  230.24  4605.8  228.94
  4744.8  230.71  4897.3   230.1  4977.5     232  4999.5  230.12    5009  232.01
  5032.6  230.02  5084.9  237.85  5152.6  247.08  5182.6  252.79  5222.6  256.21
#Mann= 5 ,-1 , 0
  2938.7     .05       0  3762.8     .12       0  4119.5     .07       0
  4125.5     .12       0  5084.9     .16       0
Bank Sta=4119.5,4125.5
XS Rating Curve= 0 ,0
Exp/Cntr=0.3,0.1

Type RM Length L Ch R = 1 ,1517    ,481,481,481
BEGIN DESCRIPTION:
UNT 0484 IN LACR 2.0
END DESCRIPTION:
XS GIS Cut Line= 3
       3683599.6     10643810.18      3681799.61     10642010.19
      3681449.59     10641910.18
#Sta/Elev= 30
  2458.5  265.59    2713  251.57  2882.8  249.01  3038.3  241.81  3151.5   239.2
  3391.9  239.28  3524.4  236.92  3759.6   228.7  3784.8  223.75  3787.6  223.25
  3790.8  223.75    3802  228.61  3816.1  229.27    3901  228.73  3929.3   225.9
  3971.7  227.79    4099  227.67  4183.8  228.99  4212.1  227.84    4495  227.57
  4622.2  228.95  4664.7  230.56  4993.8  227.28  5006.7  226.72  5066.5  232.69
  5147.4  236.12  5244.6  241.66  5273.2  244.31  5284.9  243.73  5368.1   248.5
#Mann= 6 ,-1 , 0
  2458.5     .05       0  3524.4     .12       0  3784.8     .07       0
  3790.8     .12       0  4993.8     .16       0  5147.4     .05       0
Bank Sta=3784.8,3790.8
XS Rating Curve= 0 ,0
Exp/Cntr=0.3,0.1

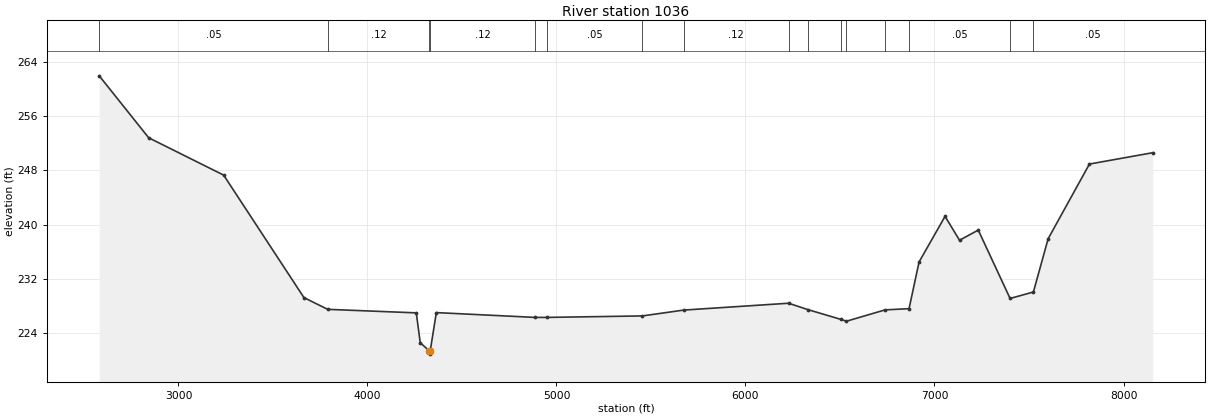
Type RM Length L Ch R = 1 ,1036    ,0,0,0
BEGIN DESCRIPTION:
UNT 0484 IN LACR 1.0
END DESCRIPTION:
XS GIS Cut Line= 3
      3683599.62      10643510.2      3681949.61     10641710.19
      3678949.64      10640810.2
#Sta/Elev= 30
  2580.8  261.91  2842.6  252.78  3239.1  247.28  3663.9  229.23  3789.6   227.5
  4258.3  226.98  4279.3  222.58  4326.2   221.4    4329   220.9  4332.2   221.4
  4364.4  227.02    4887  226.31  4948.1  226.31  5454.7  226.53    5673  227.39
  6228.1   228.4  6330.2  227.46  6505.9  226.01  6534.4  225.75  6738.6  227.42
  6865.4   227.6  6918.4  234.48  7055.9   241.2  7132.5  237.68  7231.6  239.18
    7400   229.1  7523.4  230.06  7601.4  237.91  7819.8  248.91  8154.7  250.58
#Mann= 16 ,-1 , 0
  2580.8     .05       0  3789.6     .12       0  4326.2    .033       0
  4332.2     .12       0    4887     .07       0  4948.1     .05       0
  5454.7     .07       0    5673     .12       0  6228.1     .05       0
  6330.2     .12       0  6505.9     .07       0  6534.4     .12       0
  6738.6     .07       0  6865.4     .05       0    7400     .12       0
  7523.4     .05       0
Bank Sta=4326.2,4332.2
XS Rating Curve= 0 ,0
Exp/Cntr=0.3,0.1

Chan Stop Cuts=-1
Use User Specified Reach Order=0
Composite Channel Slope=5