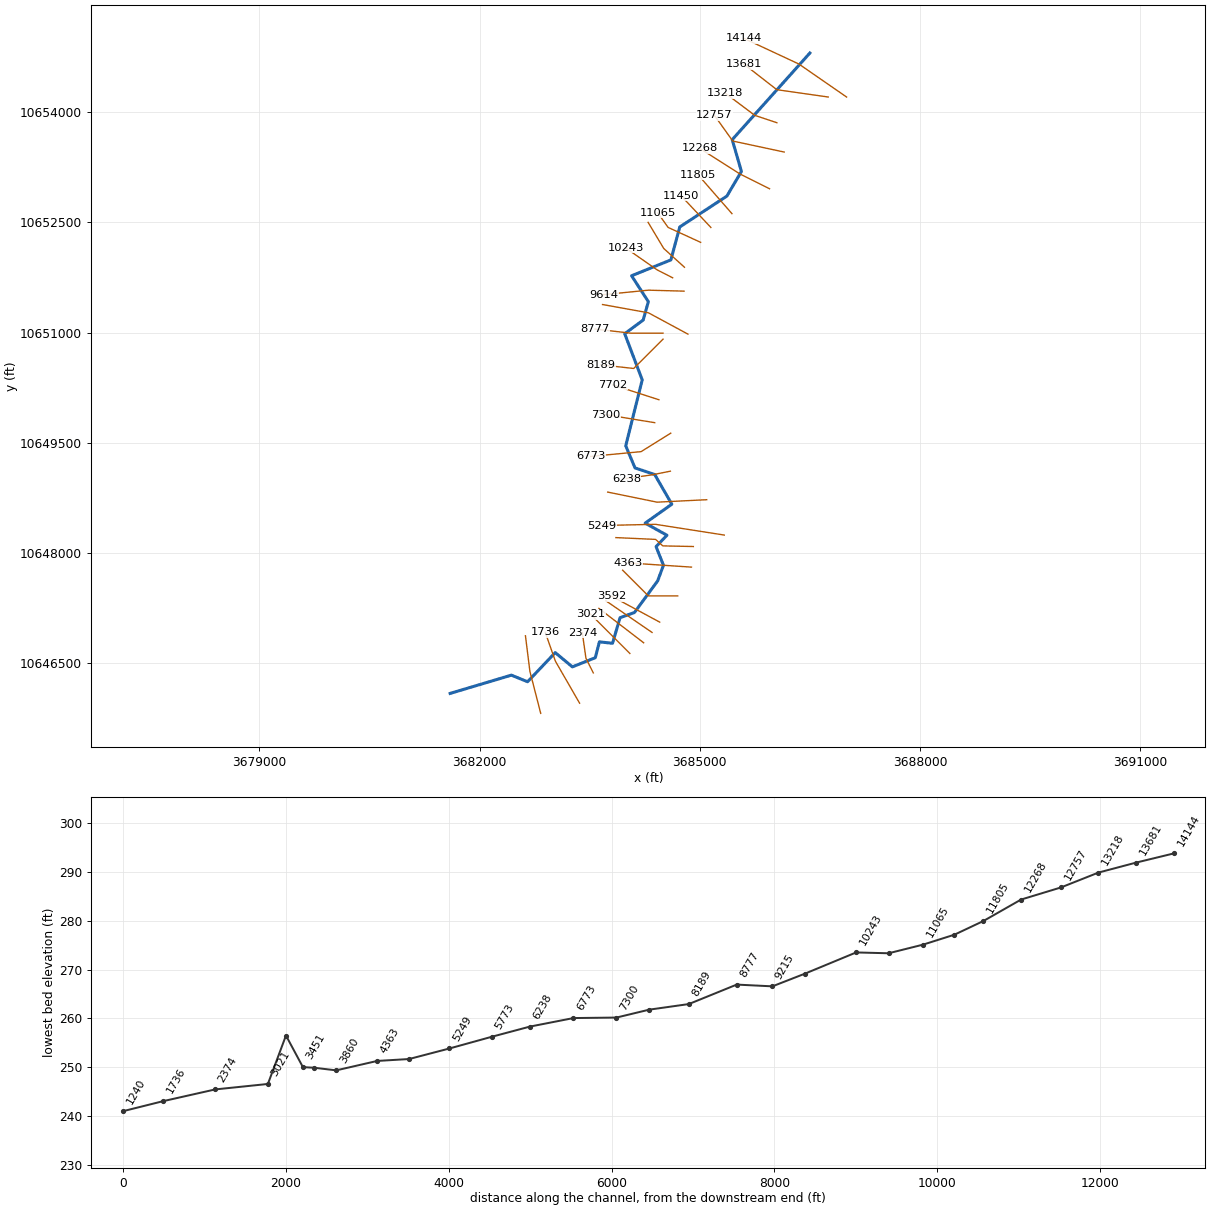
--- UNT 0485 IN LACR.prj (project) ---

Proj Title=UNT 0485 IN LACR Base Level Engineering
Current Plan=p01
Default Exp/Contr=0.3,0.1
English Units
Geom File=g01
Flow File=f01
Plan File=p01
Y Axis Title=Elevation
X Axis Title(PF)=Main Channel Distance
X Axis Title(XS)=Station
BEGIN DESCRIPTION:
UNT 0485 IN LACR
END DESCRIPTION:
DSS Export Rating Curves= 0
DSS Export Rating Curve Sorted= 0
DSS Export Volume Flow Curves= 0
DXF OffsetX= 0
DXF OffsetY= 0
DXF ScaleX= 1
DXF ScaleY= 10

--- UNT 0485 IN LACR.p01 (plan) ---

Plan Title=Multiple Run
Short Identifier=Multiple
Geom File=g01
Flow File=f01
Subcritical Flow
K Sum by GR= 0
Std Step Tol= 0.01
Critical Tol= 0.01
Num of Std Step Trials= 20
Max Error Tol= 0.3
Flow Tol Ratio= 0.001
Split Flow NTrial= 30
Split Flow Tol= 0.02
Split Flow Ratio= 0.02
Log Output Level= 0
Friction Slope Method= 1
Unsteady Friction Slope Method= 2
Unsteady Bridges Friction Slope Method= 1
Parabolic Critical Depth
Global Vel Dist=  1 , 1 , 1
Global Log Level= 0
CheckData=True
Encroach Param= -1, 0, 0, 0
BEGIN DESCRIPTION:
Multiple Run
END DESCRIPTION:

--- UNT 0485 IN LACR.f01 (steady flow) ---

Flow Title=Multiple
Program Version=4.10
Number of Profiles= 7
Profile Names=10-year,25-year,50-year,1pct_min,100-year,1pct_plu,500-year
River Rch & RM=UNT 0485 IN LACR,Reach-1         ,14144
     689     941    1150    1031    1395    1887    2063
River Rch & RM=UNT 0485 IN LACR,Reach-1         ,9215
     911    1257    1547    1396    1887    2553    2824
River Rch & RM=UNT 0485 IN LACR,Reach-1         ,53
    1335    1852    2286    2064    2792    3775    4185
Boundary for River Rch & Prof#=UNT 0485 IN LACR,Reach-1         , 1
Up Type= 0
Dn Type= 3
Dn Slope=0.003
Boundary for River Rch & Prof#=UNT 0485 IN LACR,Reach-1         , 2
Up Type= 0
Dn Type= 3
Dn Slope=0.003
Boundary for River Rch & Prof#=UNT 0485 IN LACR,Reach-1         , 3
Up Type= 0
Dn Type= 3
Dn Slope=0.003
Boundary for River Rch & Prof#=UNT 0485 IN LACR,Reach-1         , 4
Up Type= 0
Dn Type= 3
Dn Slope=0.003
Boundary for River Rch & Prof#=UNT 0485 IN LACR,Reach-1         , 5
Up Type= 0
Dn Type= 3
Dn Slope=0.003
Boundary for River Rch & Prof#=UNT 0485 IN LACR,Reach-1         , 6
Up Type= 0
Dn Type= 3
Dn Slope=0.003
Boundary for River Rch & Prof#=UNT 0485 IN LACR,Reach-1         , 7
Up Type= 0
Dn Type= 3
Dn Slope=0.003
DSS Import GetInterval= 0
DSS Import GetPeak= 0
DSS Import FillOption= 0

--- UNT 0485 IN LACR.g01 (geometry) ---

Geom Title=Existing Conditions
Program Version=4.10

River Reach=UNT 0485 IN LACR,Reach-1
Reach XY= 30
      3686499.61     10654810.19      3685441.75       10653629.
      3685567.25       10653196.      3685369.25       10652860.
       3684727.5       10652439.      3684606.25       10651990.
      3684071.25       10651774.       3684299.5       10651421.
      3684229.25       10651170.       3683977.5       10650984.
        3684216.       10650355.      3683991.25       10649456.
      3684117.75       10649155.      3684386.75       10649064.
      3684619.25       10648660.        3684256.       10648402.
        3684553.       10648237.       3684404.5       10648082.
      3684505.25       10647828.      3684426.25       10647615.
       3684110.5       10647184.        3683914.       10647113.
       3683811.5       10646764.        3683633.       10646784.
      3683576.75       10646568.      3683264.75       10646443.
      3683031.25       10646637.       3682654.5       10646240.
        3682434.       10646330.       3681599.5       10646081.

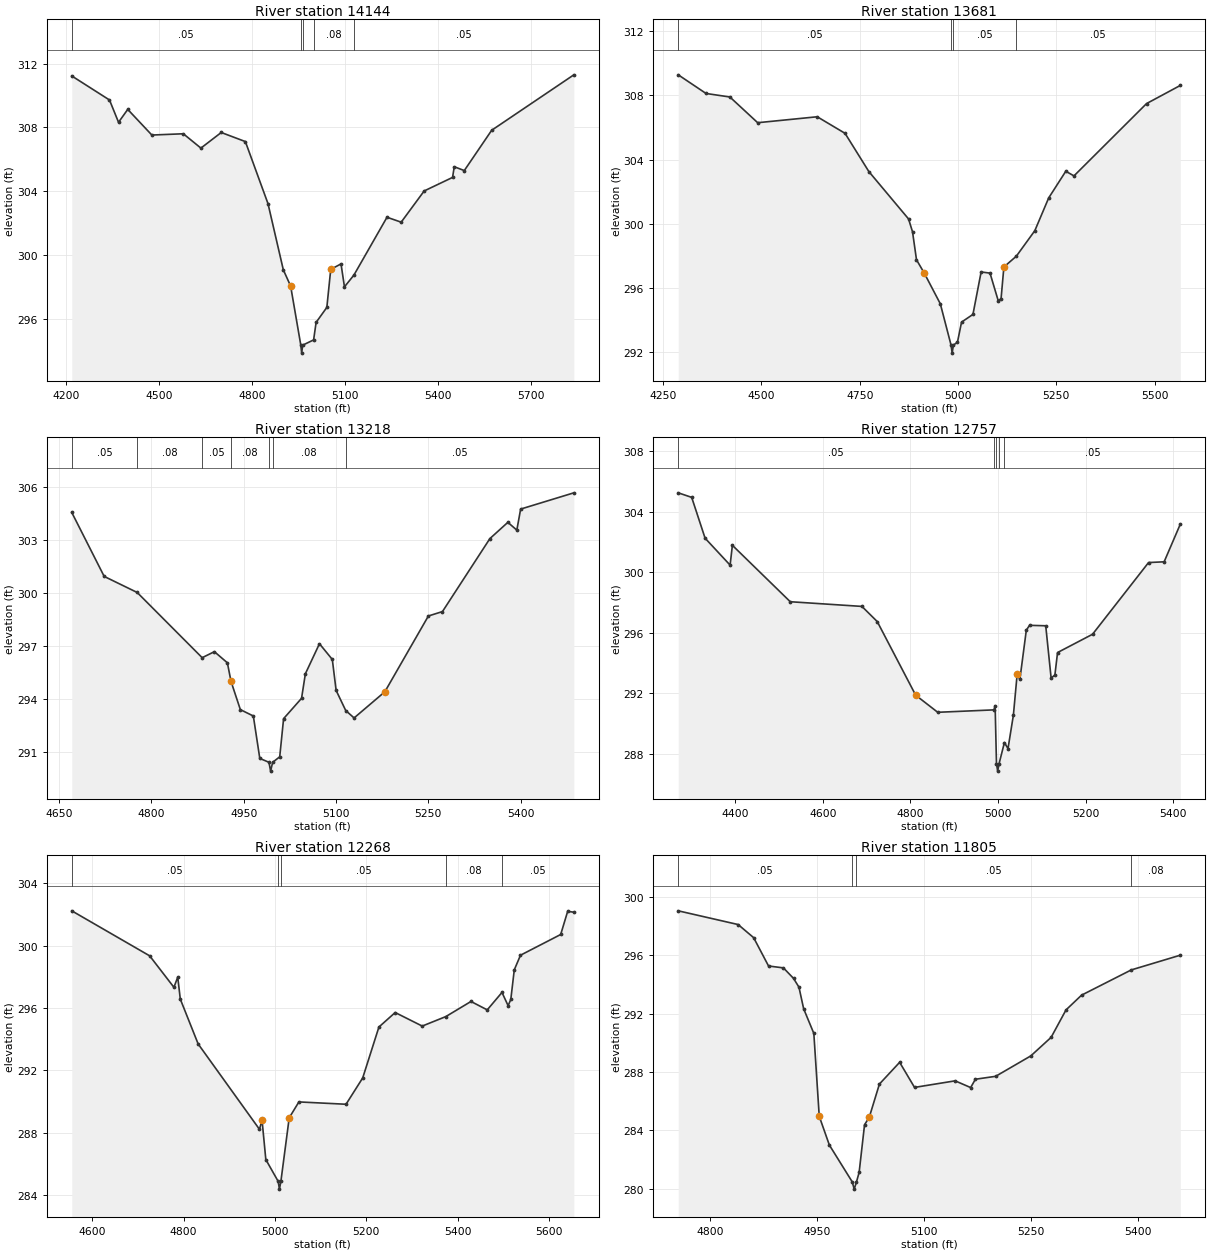
Type RM Length L Ch R = 1 ,14144   ,463,463,463
BEGIN DESCRIPTION:
UNT 0485 IN LACR 30.0
END DESCRIPTION:
XS GIS Cut Line= 3
      3686999.61     10654210.19      3686349.61     10654660.19
      3685599.63     10655010.18
#Sta/Elev= 30
  4219.2  311.23  4340.8  309.72  4369.9  308.32  4399.6  309.13  4477.3  307.52
  4578.7   307.6  4635.4   306.7    4701  307.68  4778.7  307.11  4851.7  303.21
    4901  299.06  4924.6  298.04  4957.4  294.33  4960.2  293.83  4963.4  294.33
  4998.7  294.66  5006.7  295.76  5041.3   296.7  5053.9  299.09    5087  299.43
  5098.1  297.99  5128.6  298.73  5235.2  302.36  5280.9  302.05    5355  304.01
  5446.5  304.86    5452  305.53  5484.3  305.29  5572.6  307.82  5837.4   311.3
#Mann= 5 ,-1 , 0
  4219.2     .05       0  4957.4     .07       0  4963.4     .05       0
  4998.7     .08       0  5128.6     .05       0
Bank Sta=4924.6,5053.9
XS Rating Curve= 0 ,0
Exp/Cntr=0.3,0.1

Type RM Length L Ch R = 1 ,13681   ,463,463,463
BEGIN DESCRIPTION:
UNT 0485 IN LACR 29.0
END DESCRIPTION:
XS GIS Cut Line= 3
      3686749.65     10654210.18      3686049.61     10654310.19
      3685599.63     10654660.17
#Sta/Elev= 30
  4288.2  309.27  4358.9  308.11  4419.6  307.89  4490.3  306.29  4641.8  306.66
  4712.5  305.63  4773.1  303.25  4874.1   300.3  4884.2   299.5  4894.3  297.76
  4914.5  296.91  4954.9  295.02  4982.2  292.45    4985  291.95  4988.2  292.45
  4998.5  292.63  5008.9  293.88  5037.9  294.36  5058.7     297  5081.3  296.93
  5102.1  295.22  5109.4  295.33  5116.6  297.31  5148.2  297.98  5195.3  299.57
  5230.6  301.61  5274.1  303.27  5294.9  302.98  5479.5  307.48  5565.4  308.61
#Mann= 4 ,-1 , 0
  4288.2     .05       0  4982.2     .07       0  4988.2     .05       0
  5148.2     .05       0
Bank Sta=4914.5,5116.6
XS Rating Curve= 0 ,0
Exp/Cntr=0.3,0.1

Type RM Length L Ch R = 1 ,13218   ,461,461,461
BEGIN DESCRIPTION:
UNT 0485 IN LACR 28.0
END DESCRIPTION:
XS GIS Cut Line= 3
      3686049.64     10653860.18      3685749.61     10653960.19
      3685349.58     10654260.21
#Sta/Elev= 30
  4670.4  304.54  4723.1  300.92  4776.8  300.01  4882.4  296.32  4902.3  296.66
  4923.4  296.03  4929.3  294.98  4944.5  293.38  4965.6  293.02  4976.1  290.62
    4991   290.4  4993.7   289.9    4997   290.4  5008.5  290.71  5014.8  292.87
    5044  294.02  5050.2  295.41  5073.1  297.11    5094  296.22  5100.2  294.47
  5115.8  293.33  5129.4  292.91  5179.4  294.39  5250.2  298.68  5273.1  298.93
  5350.2  303.06  5379.4  303.98    5394  303.54  5400.2  304.73  5486.7  305.65
#Mann= 7 ,-1 , 0
  4670.4     .05       0  4776.8     .08       0  4882.4     .05       0
  4929.3     .08       0    4991     .07       0    4997     .08       0
  5115.8     .05       0
Bank Sta=4929.3,5179.4
XS Rating Curve= 0 ,0
Exp/Cntr=0.3,0.1

Type RM Length L Ch R = 1 ,12757   ,489,489,489
BEGIN DESCRIPTION:
UNT 0485 IN LACR 27.0
END DESCRIPTION:
XS GIS Cut Line= 3
       3686149.6     10653460.19      3685449.61     10653610.19
      3685199.61     10653960.19
#Sta/Elev= 30
  4269.9  305.25  4300.6  304.95  4331.2  302.25  4388.3  300.47  4393.5  301.78
  4525.6  298.05  4689.2  297.74  4724.1  296.74  4811.9  291.87  4862.2  290.74
  4990.5   290.9  4993.2  291.18  4996.3  287.35    4999  286.85  5002.3  287.35
  5014.4  288.74  5022.6  288.34  5034.9  290.55  5043.5  293.26  5049.7  292.92
  5064.4  296.17  5071.8  296.49  5108.7  296.46    5121  293.01  5129.6   293.2
  5135.7  294.69  5215.6   295.9  5343.4  300.64    5379  300.69  5415.9  303.18
#Mann= 5 ,-1 , 0
  4269.9     .05       0  4990.5     .08       0  4996.3     .07       0
  5002.3     .08       0  5014.4     .05       0
Bank Sta=4811.9,5043.5
XS Rating Curve= 0 ,0
Exp/Cntr=0.3,0.1

Type RM Length L Ch R = 1 ,12268   ,463,463,463
BEGIN DESCRIPTION:
UNT 0485 IN LACR 26.0
END DESCRIPTION:
XS GIS Cut Line= 3
       3685949.6     10652960.19      3685549.61     10653160.19
      3684999.63     10653510.18
#Sta/Elev= 30
  4555.1  302.24  4725.6  299.35  4778.7  297.33  4787.1  297.98  4792.7  296.57
  4831.8  293.69    4966  288.21  4971.6  288.81  4979.9  286.27  5006.9  284.87
  5009.7  284.37  5012.9  284.87  5031.1  288.95  5052.3  289.97  5155.5  289.82
    5192  291.51  5227.5  294.78  5263.1  295.71  5322.3  294.84    5374  295.45
    5429  296.42  5464.6  295.88  5496.9     297  5510.3  296.15  5516.2  296.55
  5523.8  298.45  5537.4  299.39  5625.4  300.72  5640.7  302.21  5654.2  302.15
#Mann= 5 ,-1 , 0
  4555.1     .05       0  5006.9     .03       0  5012.9     .05       0
    5374     .08       0  5496.9     .05       0
Bank Sta=4971.6,5031.1
XS Rating Curve= 0 ,0
Exp/Cntr=0.3,0.1

Type RM Length L Ch R = 1 ,11805   ,355,355,355
BEGIN DESCRIPTION:
UNT 0485 IN LACR 25.0
END DESCRIPTION:
XS GIS Cut Line= 2
      3685438.52     10652620.31      3684975.01     10653151.52
#Sta/Elev= 30
  4754.7  299.04  4838.8   298.1  4860.6   297.2  4881.5  295.26  4902.4  295.13
  4916.6  294.41  4924.2  293.81  4930.8  292.33  4945.1  290.64  4952.7  284.96
  4966.9  282.99    4999  280.47  5001.8  279.97    5005  280.47  5008.7  281.11
  5016.3  284.38  5022.9  284.89  5037.2  287.17  5065.6  288.66  5086.5  286.94
  5143.5  287.39  5165.3  286.93    5172   287.5  5200.4   287.7  5249.8   289.1
  5278.3  290.37  5299.2  292.25    5321  293.26  5390.8  294.99  5459.7     296
#Mann= 4 ,-1 , 0
  4754.7     .05       0    4999     .03       0    5005     .05       0
  5390.8     .08       0
Bank Sta=4952.7,5022.9
XS Rating Curve= 0 ,0
Exp/Cntr=0.3,0.1

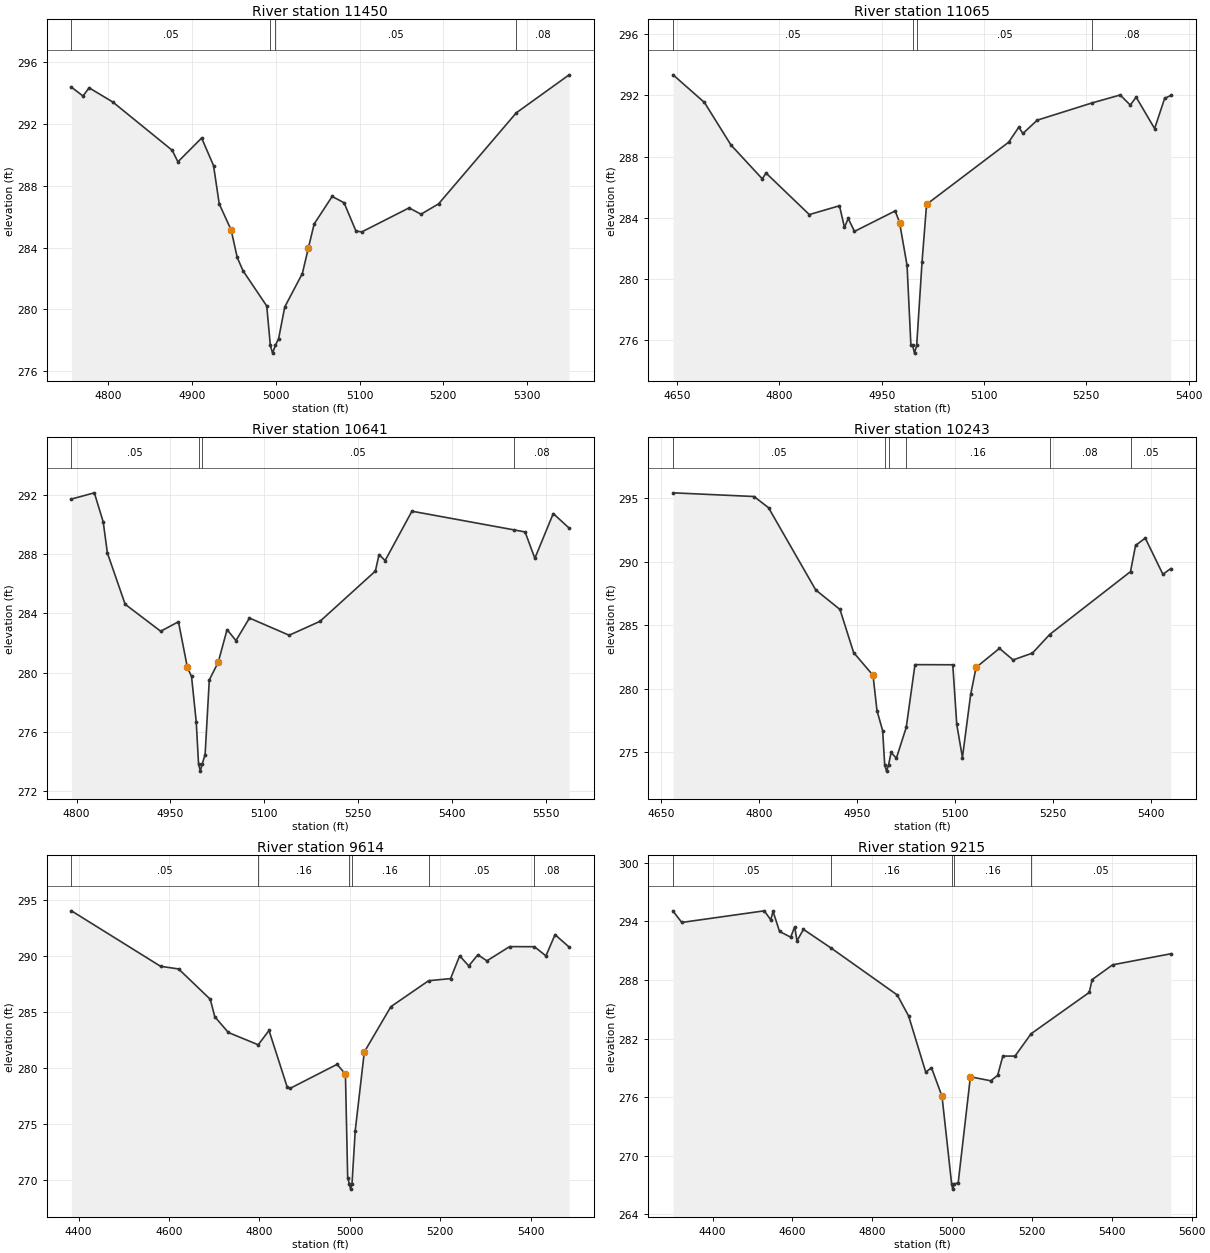
Type RM Length L Ch R = 1 ,11450   ,385,385,385
BEGIN DESCRIPTION:
UNT 0485 IN LACR 24.0
END DESCRIPTION:
XS GIS Cut Line= 2
      3685151.31     10652432.21      3684744.47     10652865.02
#Sta/Elev= 30
  4756.1  294.38  4769.9  293.81  4777.2  294.34  4805.5  293.42  4876.3   290.3
  4883.2  289.55  4911.5  291.09  4925.7  289.31  4932.5  286.83  4946.7  285.14
    4954  283.36  4960.9   282.5  4989.2  280.22  4993.5  277.67  4996.2  277.17
  4999.5  277.67  5003.4  278.11  5010.7  280.16  5031.7  282.32    5039     284
  5045.8  285.53  5067.3  287.31  5081.5   286.9  5095.6  285.08  5102.5  285.01
  5159.1  286.57  5173.3  286.16  5194.3  286.83    5287  292.72  5350.1  295.18
#Mann= 4 ,-1 , 0
  4756.1     .05       0  4993.5     .03       0  4999.5     .05       0
    5287     .08       0
Bank Sta=4946.7,5039
XS Rating Curve= 0 ,0
Exp/Cntr=0.3,0.1

Type RM Length L Ch R = 1 ,11065   ,424,424,424
BEGIN DESCRIPTION:
UNT 0485 IN LACR 23.0
END DESCRIPTION:
XS GIS Cut Line= 3
      3685011.42     10652229.68      3684568.74     10652432.79
      3684428.14     10652630.68
#Sta/Elev= 30
    4644  293.35    4690  291.54  4728.8  288.76  4774.8  286.54  4780.3  286.92
  4843.8   284.2    4888  284.78  4895.3  283.36  4900.8  283.95    4910   283.1
  4969.7  284.44  4976.1  283.68  4987.1  280.87  4992.7  275.67  4995.2  275.63
    4998  275.13  5001.2  275.63  5009.1  281.12  5015.7  284.87  5136.1  288.94
  5150.9  289.92    5157  289.51  5177.9  290.38  5258.3  291.51  5299.6  292.03
  5314.4  291.37    5323  291.89  5350.1  289.83  5364.8  291.81  5373.8     292
#Mann= 4 ,-1 , 0
    4644     .05       0  4995.2     .03       0  5001.2     .05       0
  5258.3     .08       0
Bank Sta=4976.1,5015.7
XS Rating Curve= 0 ,0
Exp/Cntr=0.3,0.1

Type RM Length L Ch R = 1 ,10641   ,398,398,398
BEGIN DESCRIPTION:
UNT 0485 IN LACR 22.0
END DESCRIPTION:
XS GIS Cut Line= 3
      3684791.13     10651890.06      3684509.04     10652146.11
      3684296.35     10652502.03
#Sta/Elev= 30
  4791.8  291.72  4828.4  292.14  4842.6  290.18  4849.3  288.08  4877.7  284.62
  4934.5   282.8  4962.9  283.44  4977.1  280.37  4983.8  279.75  4991.3  276.69
    4995  273.86  4997.8  273.36    5001  273.86  5005.5  274.48  5012.2  279.52
  5026.4   280.7  5040.6  282.91  5054.8  282.17  5076.4  283.69  5139.9  282.53
  5189.2  283.47  5277.7  286.86  5283.5  287.97  5293.3  287.57  5336.1   290.9
  5499.2  289.64    5517   289.5  5532.6  287.72    5562  290.74  5587.4  289.76
#Mann= 4 ,-1 , 0
  4791.8     .05       0    4995     .03       0    5001     .05       0
  5499.2     .08       0
Bank Sta=4977.1,5026.4
XS Rating Curve= 0 ,0
Exp/Cntr=0.3,0.1

Type RM Length L Ch R = 1 ,10243   ,629,629,629
BEGIN DESCRIPTION:
UNT 0485 IN LACR 21.0
END DESCRIPTION:
XS GIS Cut Line= 3
      3684630.44     10651746.48      3684417.79     10651854.97
      3683988.09     10652154.46
#Sta/Elev= 30
  4668.3  295.43  4792.3  295.14  4814.5  294.26  4886.8  287.79    4924  286.25
  4944.9  282.86  4974.6  281.07  4980.7  278.29  4989.4  276.71  4992.5  274.03
  4995.3  273.53  4998.5  274.03  5002.3     275  5010.4  274.55  5025.5  276.97
  5038.9  281.91  5096.8   281.9  5102.9  277.21  5111.6   274.6  5124.2  279.56
  5132.5  281.69  5168.3  283.19  5189.2  282.28  5218.9  282.82  5245.2  284.28
  5369.1  289.23  5376.8  291.29  5391.7  291.87  5418.7  289.02  5430.8  289.47
#Mann= 6 ,-1 , 0
  4668.3     .05       0  4992.5     .03       0  4998.5     .05       0
  5025.5     .16       0  5245.2     .08       0  5369.1     .05       0
Bank Sta=4974.6,5132.5
XS Rating Curve= 0 ,0
Exp/Cntr=0.3,0.1

Type RM Length L Ch R = 1 ,9614    ,399,399,399
BEGIN DESCRIPTION:
UNT 0485 IN LACR 20.0
END DESCRIPTION:
XS GIS Cut Line= 3
      3684786.69     10651564.17      3684300.45     10651577.42
      3683688.61     10651516.43
#Sta/Elev= 30
    4384  294.07  4581.2  289.11  4621.2  288.87  4691.2  286.16  4701.2   284.6
  4731.2  283.19  4797.3  282.09  4821.2  283.37  4861.3  278.33  4868.3   278.2
  4971.8  280.34  4990.3  279.47  4995.3  270.18  4998.9  269.68  5001.7  269.18
  5004.9  269.68    5012  274.41  5032.1  281.45  5090.9   285.5  5174.4  287.82
    5223  288.01  5243.1  290.05  5263.2  289.14  5283.3  290.14  5303.4   289.6
  5353.6  290.87  5408.6  290.86    5434  290.04  5454.1  291.94  5485.3  290.83
#Mann= 6 ,-1 , 0
    4384     .05       0  4797.3     .16       0  4998.9     .07       0
  5004.9     .16       0  5174.4     .05       0  5408.6     .08       0
Bank Sta=4990.3,5032.1
XS Rating Curve= 0 ,0
Exp/Cntr=0.3,0.1

Type RM Length L Ch R = 1 ,9215    ,438,438,438
BEGIN DESCRIPTION:
UNT 0485 IN LACR 19.0
END DESCRIPTION:
XS GIS Cut Line= 3
      3684838.78     10650978.24       3684300.6     10651269.03
      3683675.62     10651381.88
#Sta/Elev= 30
  4300.9  295.05  4322.7   293.9  4529.4  295.09  4545.6  294.16  4551.3  295.04
  4567.5  292.98  4595.5  292.39  4605.6  293.45  4611.3  292.01  4627.5  293.19
    4697  291.27  4862.5  286.47    4891  284.31  4933.9  278.56  4948.2  279.02
  4974.6  276.09  4998.8  267.08  5001.5  266.58  5004.8  267.08  5015.2  267.25
  5045.7  278.09  5096.5  277.68  5113.9  278.23    5127  280.21  5157.5  280.21
  5197.8   282.5  5343.4  286.73  5350.6  288.04    5402  289.56  5547.7  290.69
#Mann= 5 ,-1 , 0
  4300.9     .05       0    4697     .16       0  4998.8     .07       0
  5004.8     .16       0  5197.8     .05       0
Bank Sta=4974.6,5045.7
XS Rating Curve= 0 ,0
Exp/Cntr=0.3,0.1

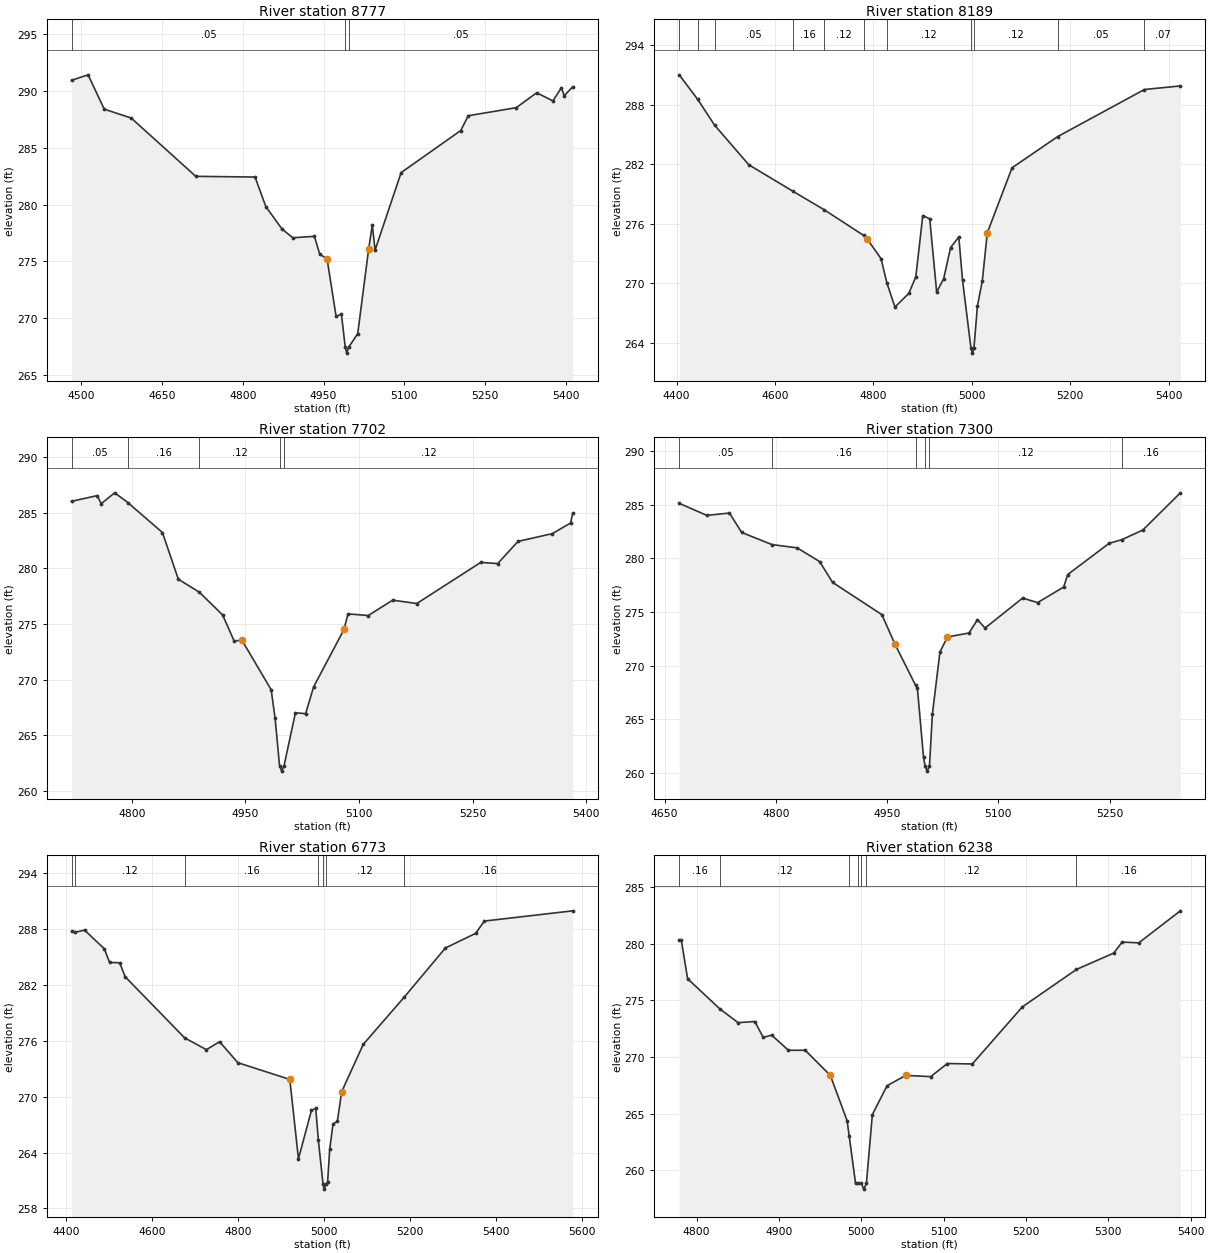
Type RM Length L Ch R = 1 ,8777    ,588,588,588
BEGIN DESCRIPTION:
UNT 0485 IN LACR 18.0
END DESCRIPTION:
XS GIS Cut Line= 3
      3684500.24     10650991.25      3684061.89     10650991.25
      3683573.06     10651047.49
#Sta/Elev= 30
  4482.1  290.94  4512.7  291.42  4542.7   288.4  4592.7  287.62  4712.7  282.49
  4822.7  282.43  4842.7  279.83  4872.7  277.86  4892.7  277.09  4932.8  277.21
  4942.9  275.63  4956.4  275.24  4973.1  270.19  4983.1  270.35  4990.2  267.44
    4993  266.94  4996.2  267.44  5013.3  268.65  5033.5  276.06  5040.4   278.2
  5045.5     276  5093.9  282.82  5204.6  286.52  5218.5  287.82  5307.6  288.53
  5345.5  289.84  5375.7  289.13  5391.6  290.29  5396.6  289.58  5412.5  290.37
#Mann= 3 ,-1 , 0
  4482.1     .05       0  4990.2     .03       0  4996.2     .05       0
Bank Sta=4956.4,5033.5
XS Rating Curve= 0 ,0
Exp/Cntr=0.3,0.1

Type RM Length L Ch R = 1 ,8189    ,487,487,487
BEGIN DESCRIPTION:
UNT 0485 IN LACR 17.0
END DESCRIPTION:
XS GIS Cut Line= 3
       3684499.6     10650910.18      3684099.61     10650510.19
      3683649.64     10650560.18
#Sta/Elev= 30
  4405.2  291.02  4442.8  288.54  4477.1  285.94  4546.6  281.95  4635.5   279.3
  4699.5  277.42  4779.8  274.83    4787  274.48  4815.3  272.48  4827.2  270.03
  4843.6   267.6  4871.9  268.98    4886  270.66  4900.2  276.83  4914.3  276.49
  4928.4  269.11  4942.6  270.45  4956.7   273.6  4973.4  274.67  4980.9  270.32
  4998.1  263.45  5000.8  262.95  5004.1  263.45  5011.1  267.66  5021.2  270.26
  5031.2  275.07  5081.5  281.64  5174.2  284.79  5350.6  289.54  5423.6   289.9
#Mann= 11 ,-1 , 0
  4405.2     .05       0  4442.8     .16       0  4477.1     .05       0
  4635.5     .16       0  4699.5     .12       0  4779.8     .05       0
  4827.2     .12       0  4998.1     .07       0  5004.1     .12       0
  5174.2     .05       0  5350.6     .07       0
Bank Sta=4787,5031.2
XS Rating Curve= 0 ,0
Exp/Cntr=0.3,0.1

Type RM Length L Ch R = 1 ,7702    ,402,402,402
BEGIN DESCRIPTION:
UNT 0485 IN LACR 16.0
END DESCRIPTION:
XS GIS Cut Line= 2
      3684443.73     10650083.84      3683814.03      10650286.8
#Sta/Elev= 30
  4720.5  286.01  4754.3  286.52  4759.6   285.8  4777.4  286.77  4794.7   285.9
  4840.4  283.21  4861.4  279.02    4889  277.86  4919.8  275.82    4935  273.49
  4945.5  273.53    4984   269.1  4989.2  266.53    4995   262.3  4997.8   261.8
    5001   262.3    5016  267.03  5029.5  266.96    5040  269.36  5080.1  274.51
  5085.4  275.91  5112.2  275.76  5144.3  277.14  5176.3  276.84  5260.7  280.53
    5283  280.42  5309.8  282.41  5355.2  283.11  5379.2  284.06  5382.1  284.96
#Mann= 5 ,-1 , 0
  4720.5     .05       0  4794.7     .16       0    4889     .12       0
    4995     .07       0    5001     .12       0
Bank Sta=4945.5,5080.1
XS Rating Curve= 0 ,0
Exp/Cntr=0.3,0.1

Type RM Length L Ch R = 1 ,7300    ,527,527,527
BEGIN DESCRIPTION:
UNT 0485 IN LACR 15.0
END DESCRIPTION:
XS GIS Cut Line= 2
      3684386.44     10649771.34      3683719.75     10649880.71
#Sta/Elev= 30
  4669.8  285.11  4707.1  283.99  4737.5  284.21    4754   282.4  4794.9  281.27
  4828.7  280.97  4859.1  279.69  4876.6  277.75    4943  274.75  4960.5  272.02
  4988.4  268.18  4990.9  267.89  4999.2  261.45  5001.2  260.68    5004  260.18
  5007.2  260.68  5011.1  265.48  5021.3  271.27  5031.4  272.67  5060.5  273.04
  5071.9  274.28  5082.1   273.5  5132.7  276.29    5153  275.87  5188.1  277.32
  5193.5  278.48  5249.4  281.39  5266.6  281.73  5294.9  282.63  5345.4  286.09
#Mann= 6 ,-1 , 0
  4669.8     .05       0  4794.9     .16       0  4988.4     .12       0
  5001.2     .07       0  5007.2     .12       0  5266.6     .16       0
Bank Sta=4960.5,5031.4
XS Rating Curve= 0 ,0
Exp/Cntr=0.3,0.1

Type RM Length L Ch R = 1 ,6773    ,535,535,535
BEGIN DESCRIPTION:
UNT 0485 IN LACR 14.0
END DESCRIPTION:
XS GIS Cut Line= 3
      3684604.46     10649628.43      3684200.78     10649376.67
      3683515.02     10649311.57
#Sta/Elev= 30
  4412.9  287.75  4420.5  287.66    4443   287.9    4489  285.89  4501.1  284.43
  4524.7  284.39  4537.4  282.89  4675.5  276.33  4726.2  275.06  4756.8  275.91
  4799.3  273.66    4920  271.86  4940.1  263.34  4970.2  268.53  4980.2  268.77
  4986.4  265.31  4997.3  260.58  5000.1  260.08  5003.3  260.58  5007.8  260.83
  5012.8  264.41  5020.4  267.09  5030.5  267.36  5040.5  270.54  5090.7  275.63
  5185.9   280.7  5281.6  285.98  5351.9  287.55    5372  288.87  5577.5  289.97
#Mann= 7 ,-1 , 0
  4412.9     .05       0  4420.5     .12       0  4675.5     .16       0
  4986.4     .12       0  4997.3     .07       0  5003.3     .12       0
  5185.9     .16       0
Bank Sta=4920,5040.5
XS Rating Curve= 0 ,0
Exp/Cntr=0.3,0.1

Type RM Length L Ch R = 1 ,6238    ,465,465,465
BEGIN DESCRIPTION:
UNT 0485 IN LACR 13.0
END DESCRIPTION:
XS GIS Cut Line= 3
      3684599.59     10649110.18      3684349.61     10649060.19
      3683999.59     10649010.19
#Sta/Elev= 30
    4779  280.36  4781.5  280.36  4789.2  276.92  4828.1  274.27  4850.4  273.04
  4870.8  273.14    4881  271.73  4891.2  271.94  4911.6   270.6    4932   270.6
  4962.5  268.38  4982.9  264.37  4985.4  263.02  4993.1  258.85    4996  258.84
  5000.3  258.83  5003.1  258.33  5006.3  258.83  5013.5  264.91  5031.4  267.47
  5054.1  268.38  5084.4  268.27  5104.6  269.43  5134.9  269.39  5195.6  274.43
  5261.3  277.74  5306.7  279.19  5316.8  280.16    5337  280.09  5387.5  282.92
#Mann= 7 ,-1 , 0
    4779     .16       0  4828.1     .12       0  4985.4     .16       0
    4996     .12       0  5000.3     .07       0  5006.3     .12       0
  5261.3     .16       0
Bank Sta=4962.5,5054.1
XS Rating Curve= 0 ,0
Exp/Cntr=0.3,0.1

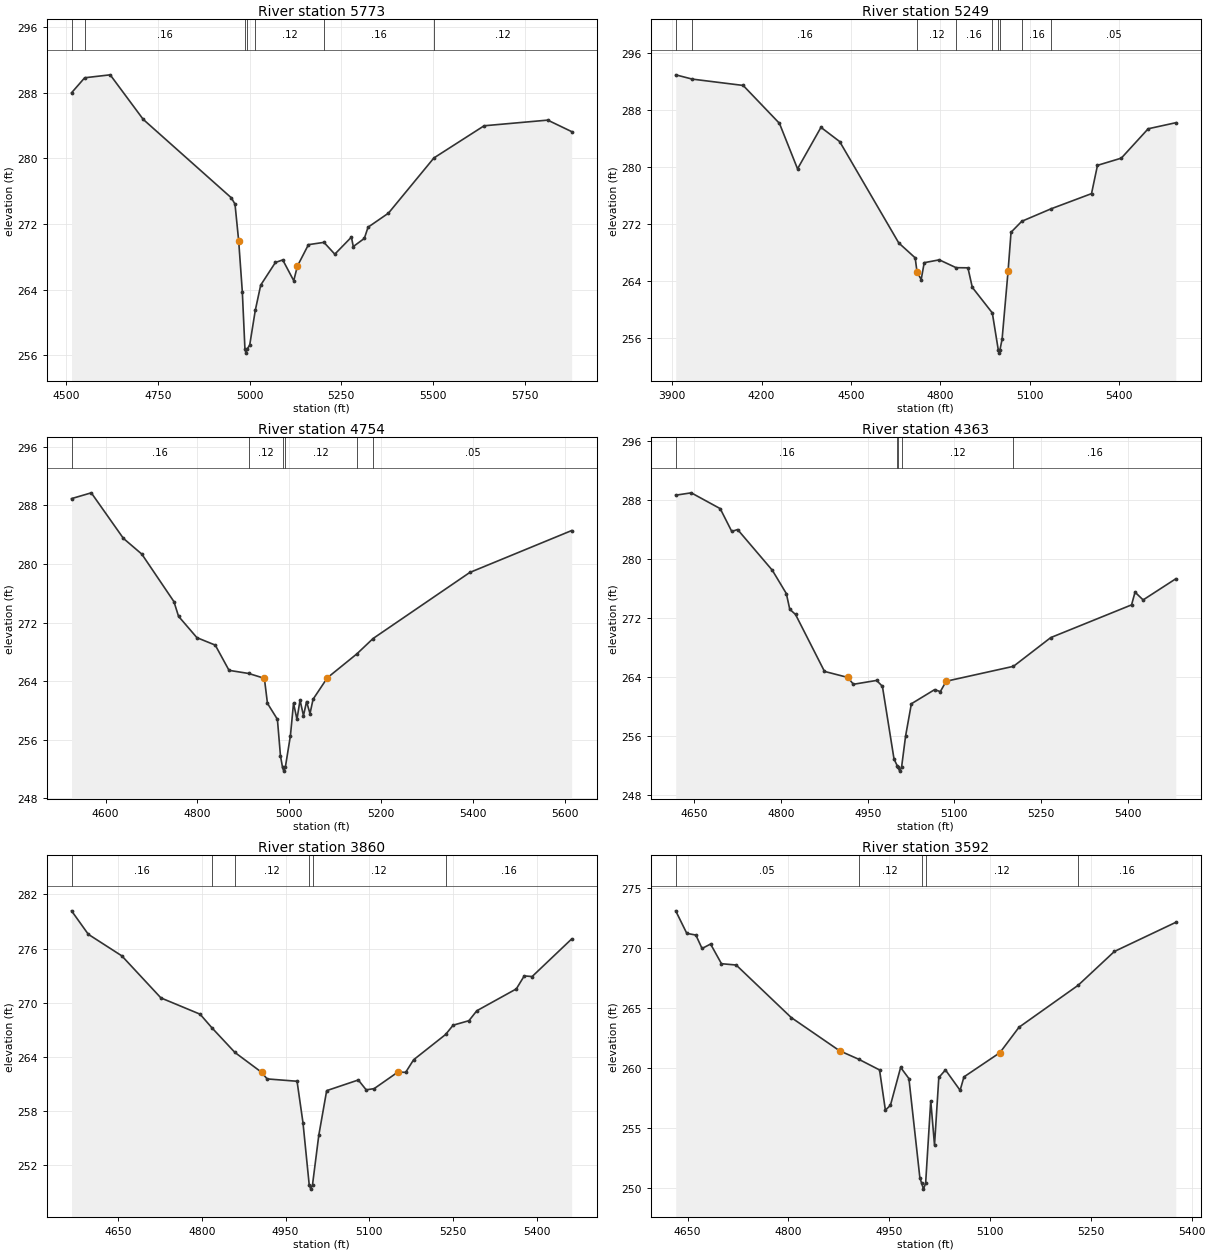
Type RM Length L Ch R = 1 ,5773    ,524,524,524
BEGIN DESCRIPTION:
UNT 0485 IN LACR 12.0
END DESCRIPTION:
XS GIS Cut Line= 3
       3685094.9     10648721.29       3684417.7       10648688.
       3683745.7     10648825.32
#Sta/Elev= 30
  4514.2  287.99    4550  289.82  4619.6  290.18  4709.7  284.75    4950  275.19
    4960  274.42    4970  269.95    4980  263.72  4987.1  256.76  4989.8  256.26
  4993.1  256.76  5000.1  257.24  5015.3  261.47  5030.1  264.55  5070.2  267.31
  5090.2  267.62  5120.2  265.09  5130.2  266.87  5160.3  269.48  5202.6  269.76
  5232.2  268.32  5277.5   270.4  5282.6  269.25  5312.7  270.24  5322.9  271.61
  5378.5  273.32  5502.5  280.05  5639.4  283.97  5812.9  284.66  5878.1  283.26
#Mann= 7 ,-1 , 0
  4514.2     .05       0    4550     .16       0  4987.1     .07       0
  4993.1     .16       0  5015.3     .12       0  5202.6     .16       0
  5502.5     .12       0
Bank Sta=4970,5130.2
XS Rating Curve= 0 ,0
Exp/Cntr=0.3,0.1

Type RM Length L Ch R = 1 ,5249    ,495,495,495
BEGIN DESCRIPTION:
UNT 0485 IN LACR 11.0
END DESCRIPTION:
XS GIS Cut Line= 3
      3685333.63     10648239.51      3684396.87     10648385.92
      3683666.88     10648369.73
#Sta/Elev= 30
  3911.7  292.89  3967.2  292.29  4138.1   291.4  4259.9  286.08  4320.6   279.7
  4399.2  285.52  4461.9  283.53  4660.3   269.3  4715.4  267.21  4721.7   265.2
  4735.6  264.17  4745.7  266.53  4796.3  266.93  4852.7  265.83  4892.4  265.81
  4907.1  263.07  4974.3  259.48  4994.1  254.34  4996.9  253.84  5000.1  254.34
  5007.1   255.8  5027.1  265.33  5037.1   270.8  5073.2  272.34  5172.1   274.1
  5307.2  276.22  5327.2  280.19  5407.2   281.2  5497.3  285.32    5590  286.17
#Mann= 9 ,-1 , 0
  3911.7     .05       0  3967.2     .16       0  4721.7     .12       0
  4852.7     .16       0  4974.3     .12       0  4994.1     .07       0
  5000.1     .12       0  5073.2     .16       0  5172.1     .05       0
Bank Sta=4721.7,5027.1
XS Rating Curve= 0 ,0
Exp/Cntr=0.3,0.1

Type RM Length L Ch R = 1 ,4754    ,391,391,391
BEGIN DESCRIPTION:
UNT 0485 IN LACR 10.0
END DESCRIPTION:
XS GIS Cut Line= 4
      3684912.63     10648083.27      3684495.92     10648091.95
      3684398.17     10648180.48       3683857.9      10648204.8
#Sta/Elev= 30
  4525.9  288.94  4568.9  289.73  4638.9   283.5    4679  281.35    4749  274.85
    4759  272.85    4799  269.93    4839  268.91    4869  265.46  4911.9  265.03
    4946  264.37  4952.7  260.95  4974.4  258.76  4981.1  253.75  4985.6  252.18
  4988.3  251.68  4991.6  252.18  5002.8  256.55  5009.5  260.97    5017  258.76
  5023.7  261.39  5031.2  259.26  5037.9  261.19  5045.4  259.54  5052.1  261.51
  5083.2  264.44  5147.5  267.71  5182.8  269.81  5393.5  278.84  5615.4  284.57
#Mann= 6 ,-1 , 0
  4525.9     .16       0  4911.9     .12       0  4985.6     .07       0
  4991.6     .12       0  5147.5     .16       0  5182.8     .05       0
Bank Sta=4946,5083.2
XS Rating Curve= 0 ,0
Exp/Cntr=0.3,0.1

Type RM Length L Ch R = 1 ,4363    ,503,503,503
BEGIN DESCRIPTION:
UNT 0485 IN LACR 9.0
END DESCRIPTION:
XS GIS Cut Line= 2
      3684886.45     10647802.59      3684023.24     10647859.79
#Sta/Elev= 30
  4617.9  288.65  4644.8  288.97  4694.9  286.83  4714.9  283.74    4725     284
  4785.1  278.48  4809.3  275.33  4815.2  273.21  4825.2   272.5  4875.3  264.79
  4915.4  263.98  4925.4  263.05  4965.5  263.57  4975.5  262.77  4995.6  252.92
  5001.4  251.98  5002.6  251.79  5005.3  251.29  5008.6  251.79  5015.6  256.05
  5025.6  260.41  5065.7  262.32  5075.7  262.06  5085.8  263.46  5202.2  265.48
  5266.7  269.37  5406.5   273.8  5412.5  275.52  5426.5  274.47    5483  277.33
#Mann= 5 ,-1 , 0
  4617.9     .16       0  5001.4     .12       0  5002.6     .07       0
  5008.6     .12       0  5202.2     .16       0
Bank Sta=4915.4,5085.8
XS Rating Curve= 0 ,0
Exp/Cntr=0.3,0.1

Type RM Length L Ch R = 1 ,3860    ,268,268,268
BEGIN DESCRIPTION:
UNT 0485 IN LACR 8.0
END DESCRIPTION:
XS GIS Cut Line= 3
      3684699.65     10647410.19      3684299.61     10647410.19
      3683949.62     10647760.18
#Sta/Elev= 30
    4567  280.19    4597  277.59    4657   275.2    4727  270.54    4797  268.74
  4818.1  267.24  4859.4   264.5    4907  262.31    4917  261.57  4970.6  261.31
  4981.2  256.72  4992.3  249.86  4995.1  249.36  4998.3  249.86  5009.5  255.33
  5023.6  260.27  5080.2  261.45  5094.3  260.36  5108.5  260.49  5150.9  262.32
    5165   262.3  5179.2  263.69  5236.4  266.49  5249.9  267.52  5278.2  268.02
  5292.3  269.12    5363  271.54  5377.2  272.98  5391.3  272.91    5462  277.07
#Mann= 6 ,-1 , 0
    4567     .16       0  4818.1     .05       0  4859.4     .12       0
  4992.3     .07       0  4998.3     .12       0  5236.4     .16       0
Bank Sta=4907,5150.9
XS Rating Curve= 0 ,0
Exp/Cntr=0.3,0.1

Type RM Length L Ch R = 1 ,3592    ,141,141,141
BEGIN DESCRIPTION:
Mapping XS ea10de10
END DESCRIPTION:
XS GIS Cut Line= 2
      3684454.14     10647052.59      3683799.32     10647405.99
#Sta/Elev= 30
  4632.3   273.1  4648.8  271.22  4662.3  271.08  4671.5  269.96  4684.2  270.33
  4700.4  268.69  4722.3  268.58  4804.2   264.2  4876.1  261.43  4904.7  260.72
  4935.6  259.83  4944.3  256.48  4951.8  256.88    4967  260.04  4979.3  259.11
  4995.6  250.84  4998.2  250.39    5001  249.89  5004.2  250.39  5011.8  257.26
  5017.4  253.56  5023.8   259.2  5033.7  259.83  5055.5  258.13  5061.2  259.25
  5114.7  261.27  5143.1  263.39  5231.1  266.89    5285  269.71  5376.4  272.14
#Mann= 5 ,-1 , 0
  4632.3     .05       0  4904.7     .12       0  4998.2     .07       0
  5004.2     .12       0  5231.1     .16       0
Bank Sta=4876.1,5114.7
XS Rating Curve= 0 ,0
Exp/Cntr=0.3,0.1

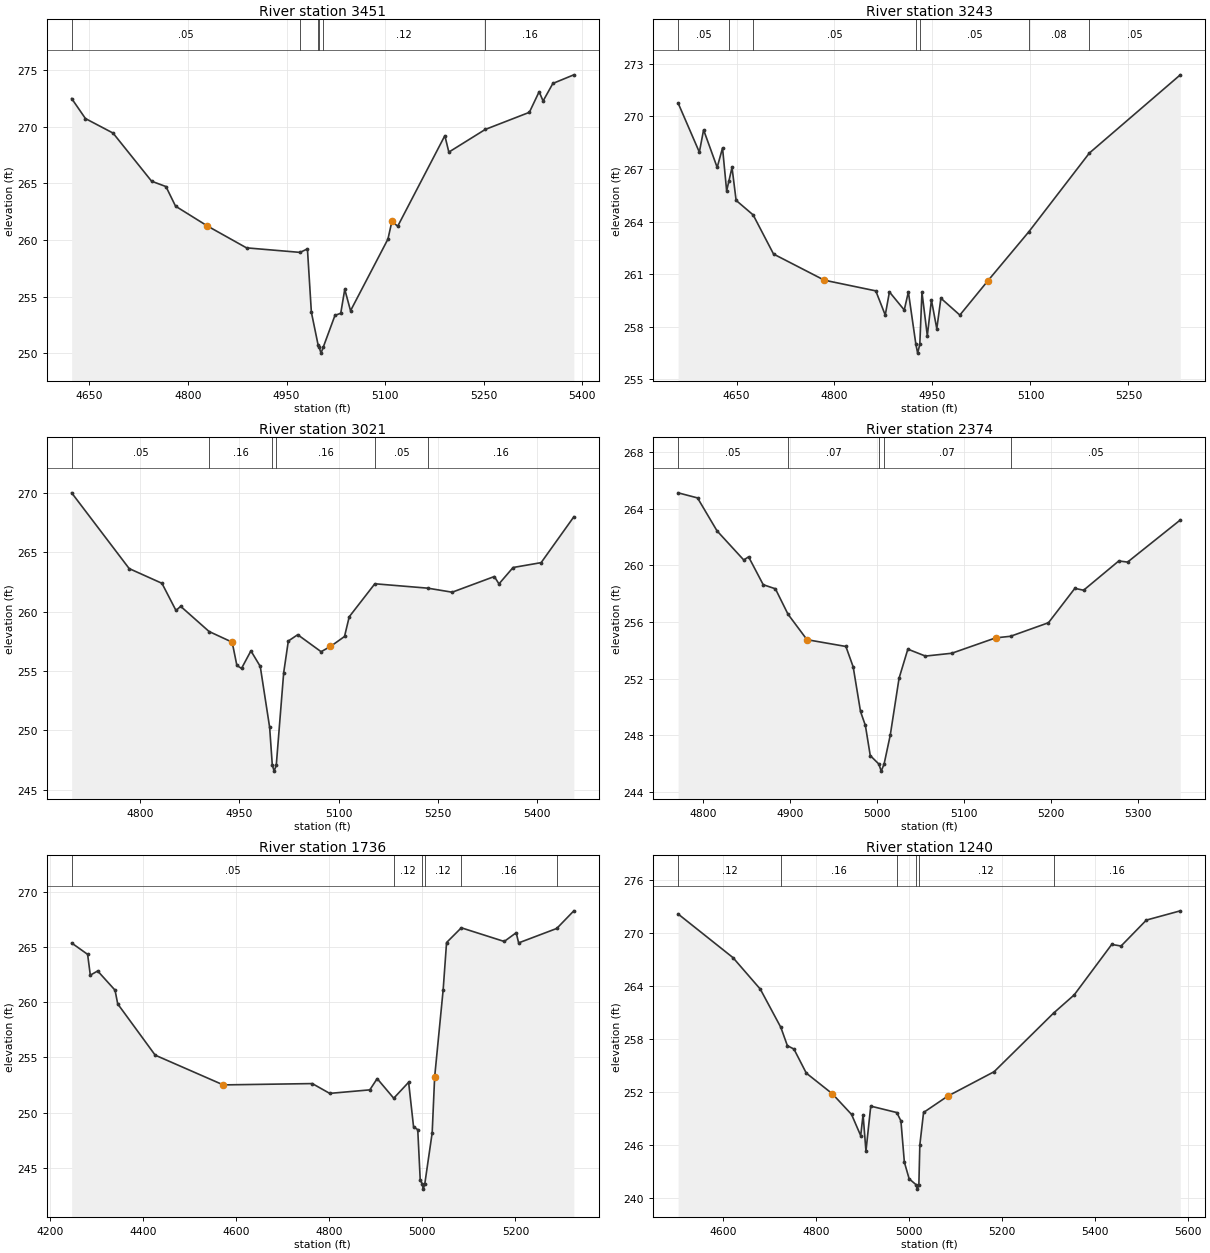
Type RM Length L Ch R = 1 ,3451    ,208,208,208
BEGIN DESCRIPTION:
UNT 0485 IN LACR 7.0
END DESCRIPTION:
XS GIS Cut Line= 2
      3684350.01     10646911.95      3683719.82     10647344.23
#Sta/Elev= 30
  4622.9  272.49  4643.9  270.72  4685.9  269.44  4744.6  265.19  4766.4  264.72
    4781  262.99  4829.5  261.24    4889  259.31  4970.5  258.91  4981.7  259.22
  4987.7  253.63  4997.8  250.78  4999.6  250.52  5002.4  250.02  5005.6  250.52
  5023.6  253.35  5032.4  253.54  5038.5  255.65  5047.3  253.76  5104.2  260.08
  5110.2  261.64  5119.1  261.22  5190.8  269.21  5196.9  267.76  5252.3  269.76
  5319.4  271.27  5334.3  273.09  5340.3  272.27  5355.2  273.82  5387.1  274.58
#Mann= 6 ,-1 , 0
  4622.9     .05       0  4970.5     .16       0  4997.8     .12       0
  4999.6     .07       0  5005.6     .12       0  5252.3     .16       0
Bank Sta=4829.5,5110.2
XS Rating Curve= 0 ,0
Exp/Cntr=0.3,0.1

Type RM Length L Ch R = 1 ,3243    ,222,222,222
BEGIN DESCRIPTION:
UNT 0485 IN LACR 6.0
END DESCRIPTION:
XS GIS Cut Line= 2
      3684235.38     10646771.36      3683626.01      10647240.1
#Sta/Elev= 30
  4560.6  270.76  4593.1  267.96  4599.6  269.23  4620.4  267.09  4628.6   268.2
  4634.9  265.75  4638.2  266.29  4643.1  267.09  4649.4  265.21  4675.5  264.38
  4706.7  262.15  4784.4  260.66  4863.2  260.05  4877.7  258.67  4884.1  259.99
  4906.8  258.96  4913.1  259.99  4924.6     257  4927.3   256.5  4930.6     257
  4933.9  259.97  4942.1  257.49  4948.4  259.53  4956.6  257.89  4962.9  259.63
  4991.9  258.67  5034.7  260.62  5097.5  263.42  5190.2  267.91  5329.4  272.37
#Mann= 7 ,-1 , 0
  4560.6     .05       0  4638.2     .08       0  4675.5     .05       0
  4924.6     .04       0  4930.6     .05       0  5097.5     .08       0
  5190.2     .05       0
Bank Sta=4784.4,5034.7
XS Rating Curve= 0 ,0
Exp/Cntr=0.3,0.1

Type RM Length L Ch R = 1 ,3021    ,647,647,647
BEGIN DESCRIPTION:
Mapping XS 6078b48b
END DESCRIPTION:
XS GIS Cut Line= 2
      3684047.89     10646625.52      3683511.47     10647161.94
#Sta/Elev= 30
  4696.7  270.01  4783.6  263.63  4833.1  262.39  4854.3   260.1  4861.4  260.45
  4904.3  258.33  4939.2  257.43  4946.3  255.47  4953.3  255.22  4967.5   256.7
  4981.6  255.39  4995.8  250.25  4999.8  247.07  5002.6  246.57  5005.8  247.07
    5017  254.86    5024  257.53  5038.2  258.06  5073.5  256.63  5087.7  257.07
  5108.9  257.91    5116  259.57  5154.7  262.35  5234.7  261.98  5271.5  261.64
  5335.2  262.96  5342.2  262.34  5363.5  263.72  5405.9  264.13  5455.3  267.99
#Mann= 6 ,-1 , 0
  4696.7     .05       0  4904.3     .16       0  4999.8     .07       0
  5005.8     .16       0  5154.7     .05       0  5234.7     .16       0
Bank Sta=4939.2,5087.7
XS Rating Curve= 0 ,0
Exp/Cntr=0.3,0.1

Type RM Length L Ch R = 1 ,2374    ,638,638,638
BEGIN DESCRIPTION:
UNT 0485 IN LACR 5.0
END DESCRIPTION:
XS GIS Cut Line= 3
      3683549.59     10646360.22      3683449.61     10646560.19
      3683399.61     10646910.17
#Sta/Elev= 30
  4771.1  265.14  4793.4  264.78  4815.8  262.45  4846.5  260.39  4852.1  260.61
  4868.9  258.64  4882.9  258.35  4897.4  256.55  4919.2  254.75  4963.9  254.27
  4972.3  252.82  4980.7  249.67  4986.3  248.68  4991.9  246.55  5001.8  245.95
  5004.5  245.45  5007.8  245.95  5014.9     248    5025  252.02  5035.1  254.08
  5055.3  253.59  5085.6  253.79  5136.1  254.88  5153.1  254.99  5196.7  255.95
    5227  258.38  5237.1  258.25  5277.5  260.32  5287.6  260.24  5348.2  263.22
#Mann= 5 ,-1 , 0
  4771.1     .05       0  4897.4     .07       0  5001.8     .07       0
  5007.8     .07       0  5153.1     .05       0
Bank Sta=4919.2,5136.1
XS Rating Curve= 0 ,0
Exp/Cntr=0.3,0.1

Type RM Length L Ch R = 1 ,1736    ,496,496,496
BEGIN DESCRIPTION:
UNT 0485 IN LACR 4.0
END DESCRIPTION:
XS GIS Cut Line= 3
      3683363.11     10645947.84      3683033.24     10646520.77
      3682894.58     10646915.09
#Sta/Elev= 30
  4246.4  265.39  4280.7  264.36  4286.5  262.47  4302.3  262.85  4339.6  261.11
  4345.4  259.86  4425.9  255.21  4572.2  252.51  4763.5  252.63  4800.9  251.74
  4887.1  252.06  4902.9  253.08  4938.5   251.3  4970.5  252.75  4981.1   248.7
  4990.1  248.45  4995.4  243.91  4999.3  243.55    5002  243.05  5005.3  243.55
  5021.1  248.16  5026.4  253.22  5044.7  261.14    5052  265.43  5083.7  266.77
  5175.9  265.53  5201.6  266.32  5206.9   265.4  5288.8  266.71  5325.5  268.31
#Mann= 6 ,-1 , 0
  4246.4     .05       0  4938.5     .12       0  4999.3     .07       0
  5005.3     .12       0  5083.7     .16       0  5288.8     .05       0
Bank Sta=4572.2,5026.4
XS Rating Curve= 0 ,0
Exp/Cntr=0.3,0.1

Type RM Length L Ch R = 1 ,1240    ,323,323,323
BEGIN DESCRIPTION:
UNT 0485 IN LACR 3.0
END DESCRIPTION:
XS GIS Cut Line= 3
      3682833.59     10645808.96      3682686.02     10646381.88
      3682625.43     10646866.59
#Sta/Elev= 30
  4503.6  272.17  4621.7  267.22  4680.4  263.65  4724.6  259.31  4738.6  257.24
  4752.7  256.86  4779.3  254.13  4835.3  251.79  4876.6  249.45  4896.3  247.04
  4901.4  249.42  4907.6  245.29  4917.9  250.39    4974  249.66  4982.8  248.71
  4990.2  244.04  5000.5  242.15  5015.4  241.48  5018.1  240.98  5021.4  241.48
  5023.5     246  5031.5  249.67  5083.1  251.51  5183.2  254.29    5311  260.93
  5355.5     263  5436.2  268.72  5456.3  268.54  5510.7  271.48  5583.7  272.53
#Mann= 6 ,-1 , 0
  4503.6     .12       0  4724.6     .16       0    4974     .12       0
  5015.4     .07       0  5021.4     .12       0    5311     .16       0
Bank Sta=4835.3,5083.1
XS Rating Curve= 0 ,0
Exp/Cntr=0.3,0.1