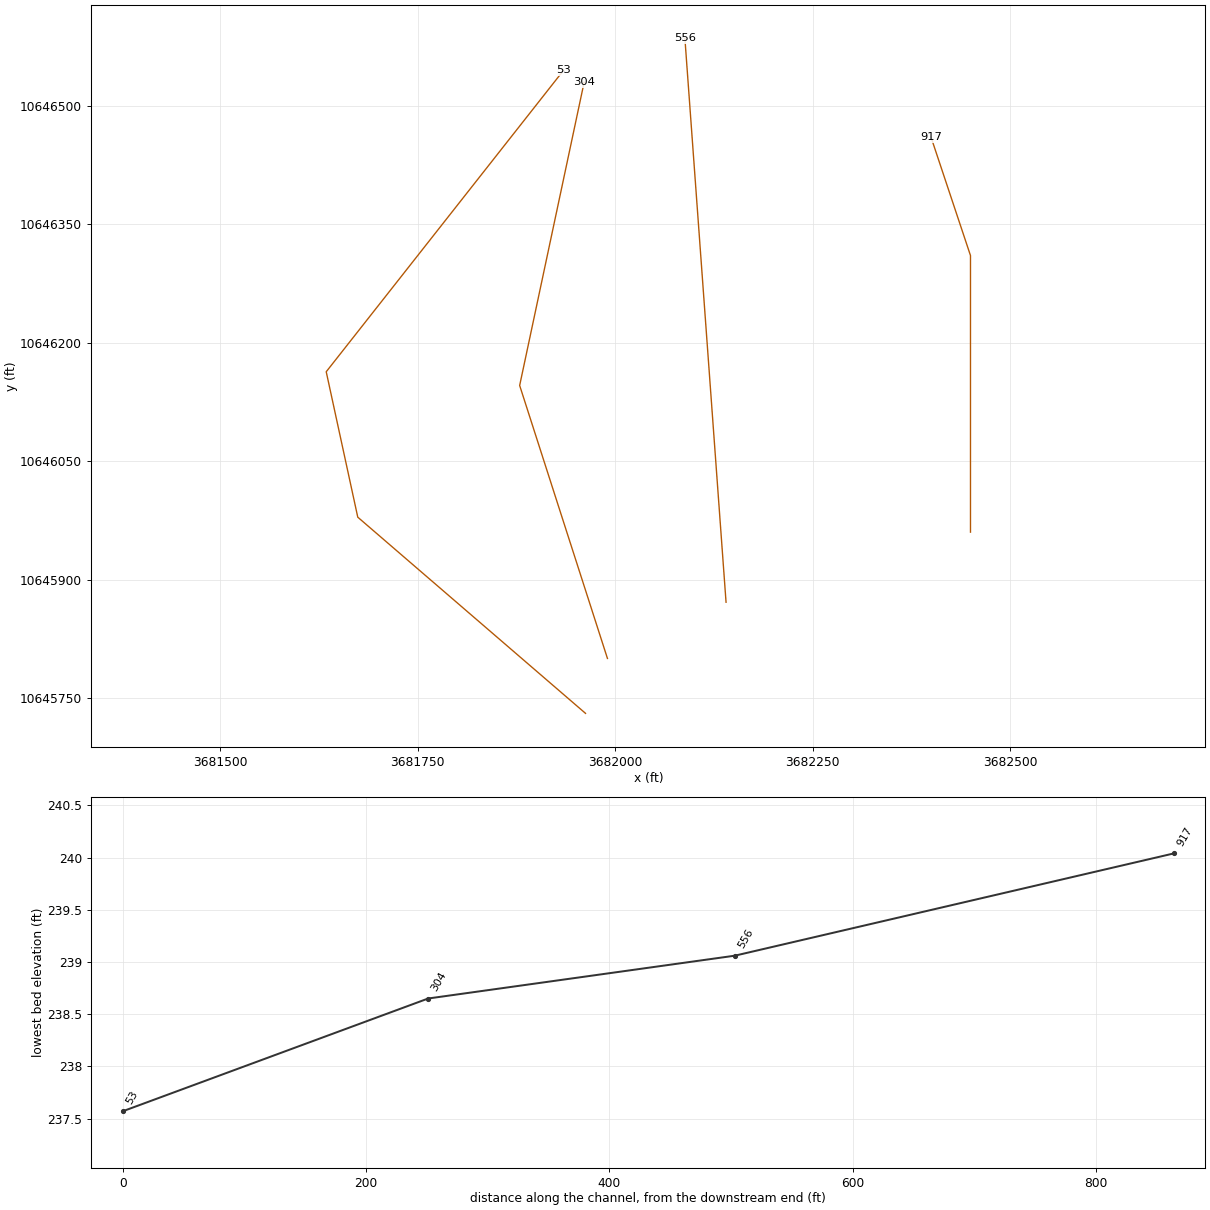
HEC-RAS study UNT 0485 IN LACR.prj: UNT 0485 IN LACR Base Level Engineering

--- UNT 0485 IN LACR.g01 (geometry) --- (continued)

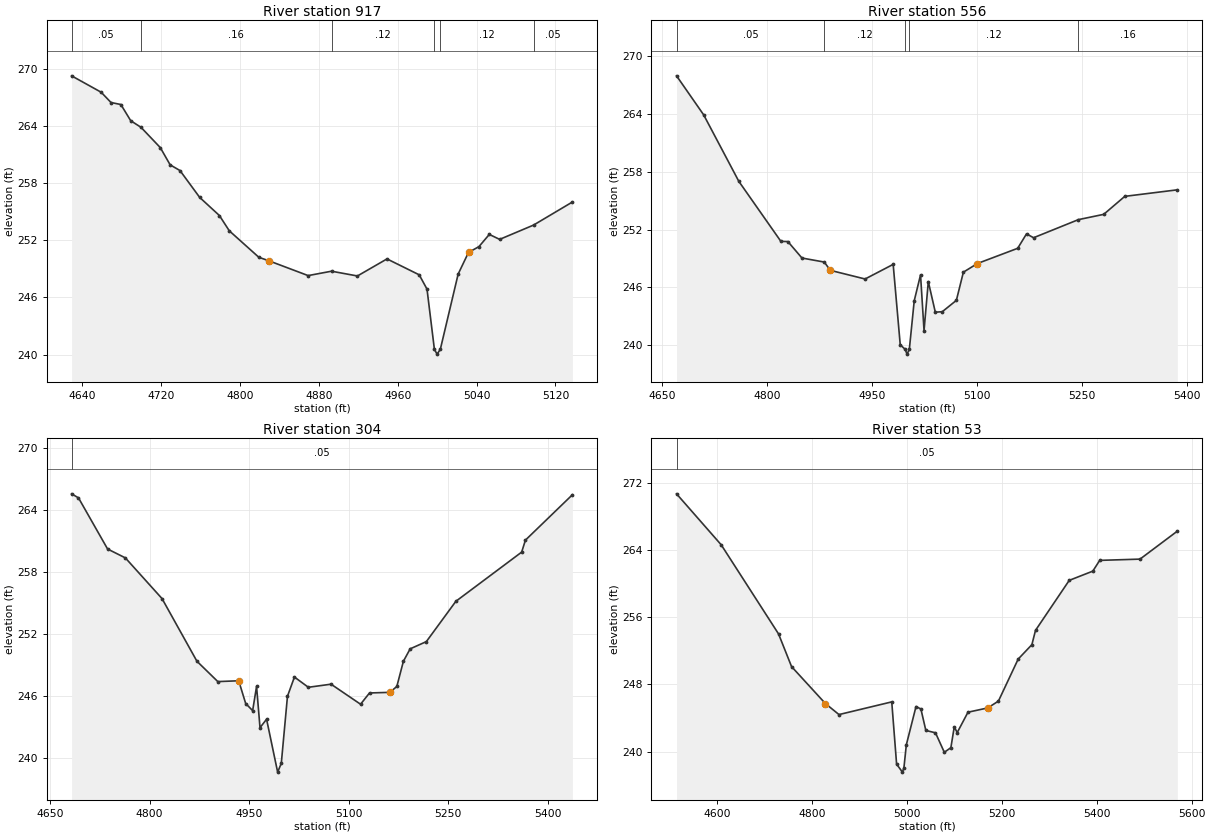
Type RM Length L Ch R = 1 ,917     ,361,361,361
BEGIN DESCRIPTION:
UNT 0485 IN LACR 2.0
END DESCRIPTION:
XS GIS Cut Line= 3
      3682449.61     10645960.17      3682449.61     10646310.19
      3682399.62     10646460.16
#Sta/Elev= 30
  4629.1  269.24  4659.1  267.52  4669.1  266.44  4679.1  266.23  4689.1  264.53
  4699.5  263.84  4719.1  261.71  4729.1   259.9  4739.1   259.3  4759.1  256.48
  4779.1  254.58  4789.1  252.98  4819.1   250.2  4829.1  249.84  4869.1  248.28
  4892.8  248.74  4919.1  248.24  4949.1  250.03  4981.8  248.36  4989.7  246.86
  4997.2  240.54  4999.9  240.04  5003.2  240.54  5021.3  248.44  5031.8  250.71
  5042.4  251.32  5052.9   252.6  5063.4  252.08  5097.8  253.58  5137.2     256
#Mann= 6 ,-1 , 0
  4629.1     .05       0  4699.5     .16       0  4892.8     .12       0
  4997.2     .07       0  5003.2     .12       0  5097.8     .05       0
Bank Sta=4829.1,5031.8
XS Rating Curve= 0 ,0
Exp/Cntr=0.3,0.1

Type RM Length L Ch R = 1 ,556     ,252,252,252
BEGIN DESCRIPTION:
Mapping XS 6faaee0a
END DESCRIPTION:
XS GIS Cut Line= 2
      3682140.27     10645871.47      3682088.18     10646585.08
#Sta/Elev= 30
  4670.6  267.99  4709.4  263.93  4759.6  257.02  4819.7  250.78  4829.7  250.76
  4849.8  249.05  4881.7  248.63  4890.3  247.77    4940  246.87  4980.1  248.39
  4990.2  240.03  4997.2  239.56  4999.9  239.06  5003.2  239.56  5010.2  244.61
  5019.2   247.3  5024.2  241.51  5030.3   246.6  5040.3  243.42  5050.3  243.47
  5070.4  244.65  5080.4  247.58  5100.5  248.48    5158  250.06  5170.6  251.56
  5180.7  251.16  5244.7  253.04  5280.9  253.59    5311  255.46  5386.1  256.14
#Mann= 5 ,-1 , 0
  4670.6     .05       0  4881.7     .12       0  4997.2     .07       0
  5003.2     .12       0  5244.7     .16       0
Bank Sta=4890.3,5100.5
XS Rating Curve= 0 ,0
Exp/Cntr=0.3,0.1

Type RM Length L Ch R = 1 ,304     ,251,251,251
BEGIN DESCRIPTION:
Mapping XS 5b9eeaea
END DESCRIPTION:
XS GIS Cut Line= 3
      3681990.18     10645800.31      3681879.08     10646145.77
      3681960.66      10646529.4
#Sta/Elev= 30
  4682.3  265.58  4692.7  265.19  4736.6  260.24  4763.4  259.38  4818.7  255.44
  4871.3  249.38  4902.8  247.41  4934.3  247.49  4944.8  245.29  4955.3   244.6
  4961.2  246.94  4966.4  242.95  4976.3  243.77    4993  238.65  4998.5   239.5
  5007.8  245.99  5018.3  247.85  5039.3  246.86  5073.5  247.16    5118  245.22
  5131.5  246.31  5162.2  246.37  5172.7  246.94  5182.6  249.38  5192.8  250.58
  5217.2  251.28  5261.7  255.18  5360.9  259.94  5366.6   261.1  5437.4  265.49
#Mann= 1 ,-1 , 0
  4682.3     .05       0
Bank Sta=4934.3,5162.2
XS Rating Curve= 0 ,0
Exp/Cntr=0.3,0.1

Type RM Length L Ch R = 1 ,53      ,0,0,0
BEGIN DESCRIPTION:
UNT 0485 IN LACR 1.0
END DESCRIPTION:
XS GIS Cut Line= 4
      3681962.45     10645730.81      3681674.21      10645979.1
      3681634.28     10646163.13      3681934.84     10646544.87
#Sta/Elev= 30
  4515.3  270.69  4609.4  264.62  4730.1  254.02  4757.5  250.13  4828.8  245.73
  4857.4  244.42  4968.5  245.93  4978.7  238.53  4990.9  237.57  4994.1  238.07
  4999.2  240.82  5019.6  245.38  5029.9  245.08  5040.3  242.53  5060.6  242.25
  5079.2  239.93    5093  240.48  5100.1  242.95  5106.4  242.28    5129   244.7
  5170.6  245.21  5193.1  246.02  5234.7  251.02  5263.6  252.74  5271.2  254.44
  5342.2  260.39  5391.9  261.49  5406.4  262.77  5491.3  262.92  5569.9  266.25
#Mann= 1 ,-1 , 0
  4515.3     .05       0
Bank Sta=4828.8,5170.6
XS Rating Curve= 0 ,0
Exp/Cntr=0.3,0.1

Chan Stop Cuts=-1
Use User Specified Reach Order=0
Composite Channel Slope=5