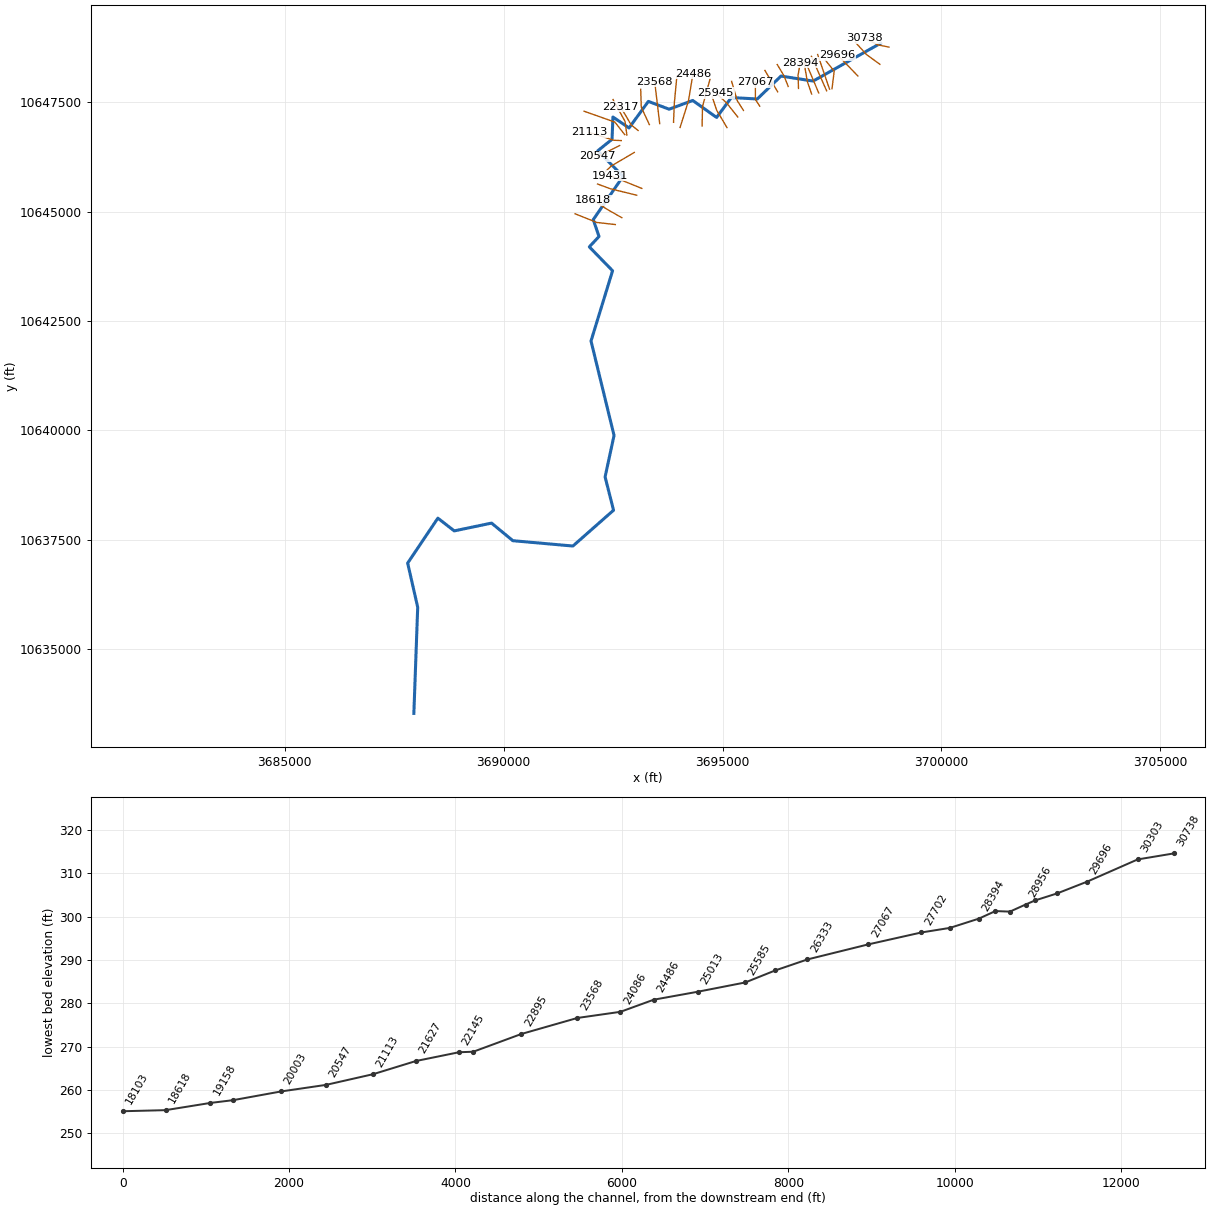
--- UNT 0487 IN LACR.prj (project) ---

Proj Title=UNT 0487 IN LACR Base Level Engineering
Current Plan=p01
Default Exp/Contr=0.3,0.1
English Units
Geom File=g01
Flow File=f01
Plan File=p01
Y Axis Title=Elevation
X Axis Title(PF)=Main Channel Distance
X Axis Title(XS)=Station
BEGIN DESCRIPTION:
UNT 0487 IN LACR
END DESCRIPTION:
DSS Export Rating Curves= 0
DSS Export Rating Curve Sorted= 0
DSS Export Volume Flow Curves= 0
DXF OffsetX= 0
DXF OffsetY= 0
DXF ScaleX= 1
DXF ScaleY= 10

--- UNT 0487 IN LACR.p01 (plan) ---

Plan Title=Multiple Run
Short Identifier=Multiple
Geom File=g01
Flow File=f01
Subcritical Flow
K Sum by GR= 0
Std Step Tol= 0.01
Critical Tol= 0.01
Num of Std Step Trials= 20
Max Error Tol= 0.3
Flow Tol Ratio= 0.001
Split Flow NTrial= 30
Split Flow Tol= 0.02
Split Flow Ratio= 0.02
Log Output Level= 0
Friction Slope Method= 1
Unsteady Friction Slope Method= 2
Unsteady Bridges Friction Slope Method= 1
Parabolic Critical Depth
Global Vel Dist=  1 , 1 , 1
Global Log Level= 0
CheckData=True
Encroach Param= -1, 0, 0, 0
BEGIN DESCRIPTION:
Multiple Run
END DESCRIPTION:

--- UNT 0487 IN LACR.f01 (steady flow) ---

Flow Title=Multiple
Number of Profiles=7
Profile Names=10-year,25-year,50-year,1pct_min,100-year,1pct_plu,500-year
River Rch & RM= UNT 0487 IN LACR,Reach-1,30738
     778    1061    1296    1161    1570    2123    2315
River Rch & RM= UNT 0487 IN LACR,Reach-1,14583
     946    1301    1597    1437    1943    2628    2891
River Rch & RM= UNT 0487 IN LACR,Reach-1,11693
    1371    1918    2383    2166    2930    3962    4452
Boundary for River Rch & Prof#=UNT 0487 IN LACR,Reach-1,1
Up Type=0
Dn Type=3
Dn Slope=0.005
Boundary for River Rch & Prof#=UNT 0487 IN LACR,Reach-1,2
Up Type=0
Dn Type=3
Dn Slope=0.005
Boundary for River Rch & Prof#=UNT 0487 IN LACR,Reach-1,3
Up Type=0
Dn Type=3
Dn Slope=0.005
Boundary for River Rch & Prof#=UNT 0487 IN LACR,Reach-1,4
Up Type=0
Dn Type=3
Dn Slope=0.005
Boundary for River Rch & Prof#=UNT 0487 IN LACR,Reach-1,5
Up Type=0
Dn Type=3
Dn Slope=0.005
Boundary for River Rch & Prof#=UNT 0487 IN LACR,Reach-1,6
Up Type=0
Dn Type=3
Dn Slope=0.005
Boundary for River Rch & Prof#=UNT 0487 IN LACR,Reach-1,7
Up Type=0
Dn Type=3
Dn Slope=0.005

--- UNT 0487 IN LACR.g01 (geometry) ---

Geom Title=Existing Conditions

River Reach=UNT 0487 IN LACR,Reach-1
Reach XY= 30
      3698612.00     10648849.00      3697068.25     10647983.00
      3696335.00     10648098.00      3695793.25     10647574.00
      3695200.75     10647607.00      3694864.00     10647152.00
      3694318.50     10647540.00      3693780.50     10647340.00
      3693305.00     10647519.00      3692864.00     10646912.00
      3692496.00     10647162.00      3692476.00     10646652.00
      3692150.00     10646390.00      3692727.50     10645806.00
      3692047.00     10644817.00      3692178.00     10644431.00
      3691956.75     10644194.00      3692488.00     10643648.00
      3691995.75     10642042.00      3692521.75     10639883.00
      3692317.25     10638937.00      3692510.00     10638174.00
      3691582.00     10637356.00      3690210.75     10637478.00
      3689723.75     10637880.00      3688871.75     10637702.00
      3688497.75     10637993.00      3687808.00     10636966.00
      3688037.25     10635957.00      3687949.50     10633531.00

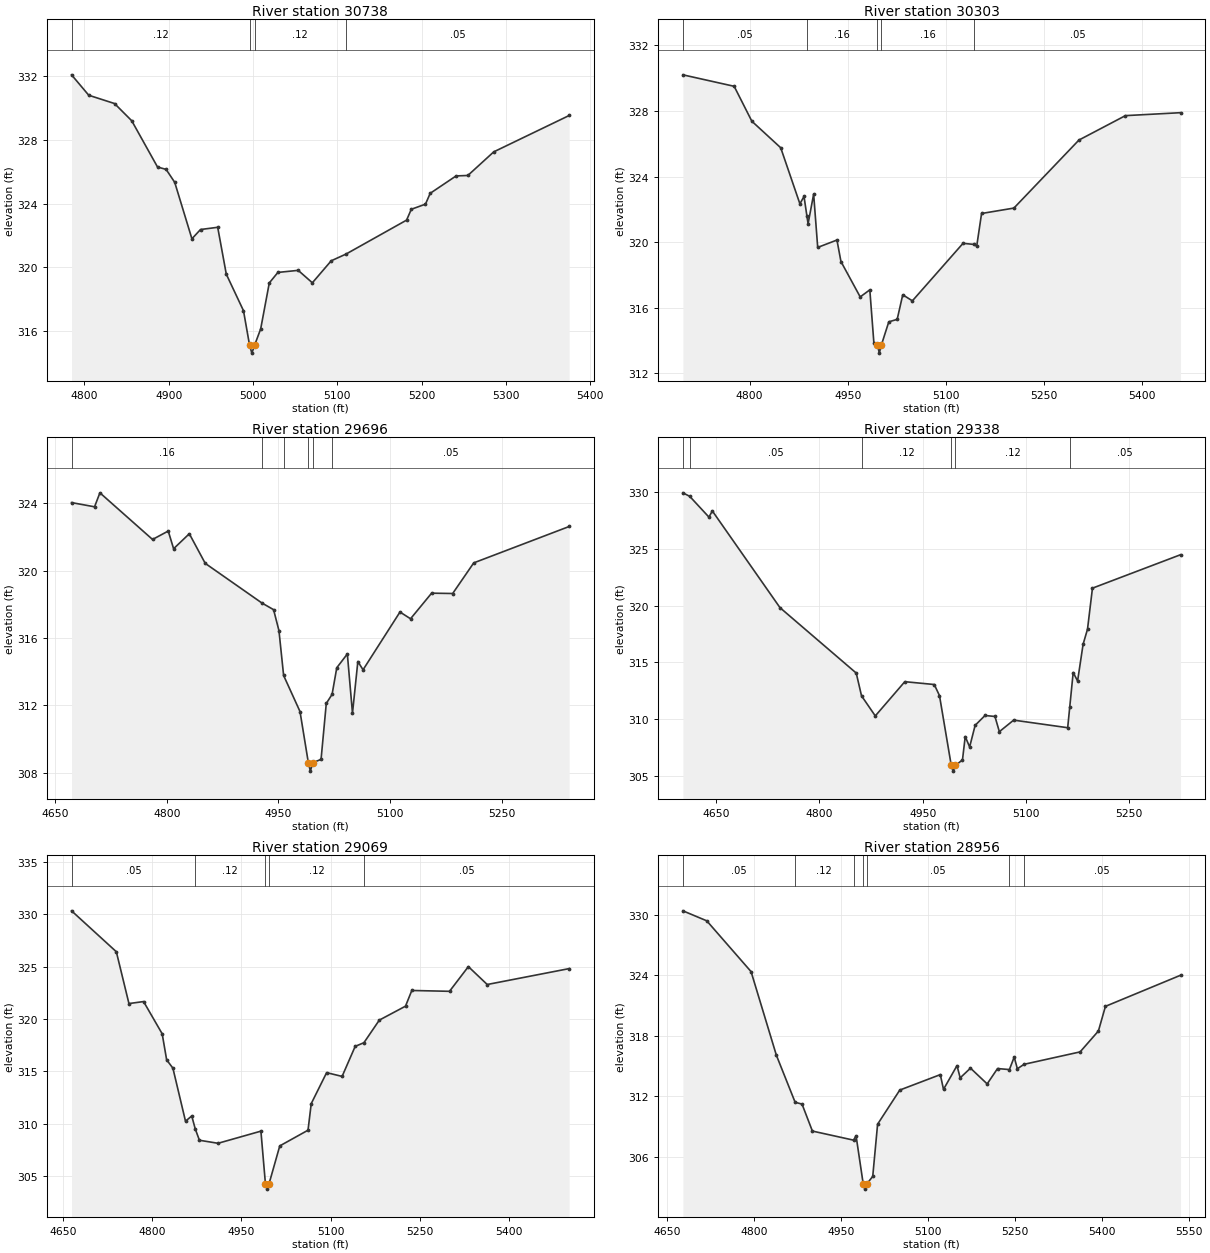
Type RM Length L Ch R = 1,30738,435,435,435
BEGIN DESCRIPTION:
UNT 0487 IN LACR 47.0
END DESCRIPTION:
XS GIS Cut Line= 3
      3698799.61     10648760.19      3698549.61     10648810.19
      3698249.57     10648960.21
#Sta/Elev= 30
  4784.8  332.07  4805.2  330.79  4835.8  330.27  4856.2  329.19  4886.8  326.29
  4897.0  326.14  4907.2  325.33  4927.6  321.79  4937.8  322.37  4958.2  322.51
  4968.4  319.57  4988.8  317.28  4996.0  315.12  4998.7  314.62  5002.0  315.12
  5009.2  316.14  5019.4  319.02  5029.6  319.68  5053.7  319.81  5070.5  319.03
  5092.9  320.41  5110.4  320.83  5182.3  322.96  5187.9  323.64  5204.7  323.96
  5210.3  324.64  5241.0  325.73  5255.0  325.76  5285.7  327.24  5375.2  329.52
#Mann=4,-1,0
  4784.8    0.12       0  4996.0    0.07       0  5002.0    0.12       0
  5110.4    0.05       0
Bank Sta=4996,5002
Exp/Cntr=0.3,0.1

Type RM Length L Ch R = 1,30303,607,607,607
BEGIN DESCRIPTION:
UNT 0487 IN LACR 46.0
END DESCRIPTION:
XS GIS Cut Line= 3
      3698594.33     10648366.60      3698292.22     10648585.37
      3698031.83     10648871.80
#Sta/Elev= 30
  4698.1  330.21  4776.4  329.51  4803.4  327.38  4847.5  325.76  4876.8  322.34
  4883.1  322.79  4887.5  321.60  4889.3  321.12  4897.8  322.93  4904.0  319.68
  4933.4  320.13  4939.5  318.82  4968.9  316.66  4983.6  317.09  4989.8  313.86
  4995.3  313.73  4998.1  313.23  5001.3  313.73  5012.6  315.14  5025.4  315.29
  5033.9  316.79  5048.6  316.42  5126.0  319.93  5143.1  319.86  5146.9  319.76
  5154.3  321.75  5203.7  322.08  5303.0  326.23  5374.0  327.72  5458.2  327.90
#Mann=5,-1,0
  4698.1    0.05       0  4887.5    0.16       0  4995.3    0.07       0
  5001.3    0.16       0  5143.1    0.05       0
Bank Sta=4995.3,5001.3
Exp/Cntr=0.3,0.1

Type RM Length L Ch R = 1,29696,358,358,358
BEGIN DESCRIPTION:
UNT 0487 IN LACR 45.0
END DESCRIPTION:
XS GIS Cut Line= 2
      3698091.67     10648098.41      3697628.18     10648580.14
#Sta/Elev= 30
  4672.0  324.05  4702.9  323.80  4710.1  324.63  4780.8  321.86  4801.9  322.36
  4809.1  321.31  4830.2  322.20  4851.6  320.44  4927.6  318.09  4943.4  317.69
  4950.6  316.45  4956.9  313.78  4978.9  311.64  4990.1  308.60  4992.8  308.10
  4996.1  308.60  5007.2  308.80  5014.2  312.12  5022.0  312.66  5028.3  314.24
  5042.5  315.06  5049.4  311.54  5056.6  314.61  5063.6  314.12  5113.2  317.55
  5127.4  317.15  5155.7  318.67  5184.0  318.65  5212.3  320.47  5340.5  322.63
#Mann=6,-1,0
  4672.0    0.16       0  4927.6    0.12       0  4956.9    0.16       0
  4990.1    0.07       0  4996.1    0.16       0  5022.0    0.05       0
Bank Sta=4990.1,4996.1
Exp/Cntr=0.3,0.1

Type RM Length L Ch R = 1,29338,269,269,269
BEGIN DESCRIPTION:
UNT 0487 IN LACR 44.0
END DESCRIPTION:
XS GIS Cut Line= 3
      3697499.61     10647810.21      3697549.61     10648210.19
      3697349.64     10648460.15
#Sta/Elev= 30
  4601.6  329.95  4611.5  329.64  4639.4  327.81  4644.4  328.35  4742.7  319.82
  4853.5  314.05  4861.2  312.04  4881.2  310.27  4924.1  313.29  4966.9  313.04
  4974.5  312.06  4991.6  305.90  4994.4  305.40  4997.6  305.90  5007.9  306.39
  5011.9  308.45  5018.3  307.53  5026.3  309.44  5040.7  310.31  5055.1  310.22
  5061.5  308.88  5082.3  309.90  5160.8  309.23  5163.8  311.06  5168.8  314.10
  5175.2  313.35  5183.2  316.59  5189.6  317.92  5196.8  321.54  5324.8  324.49
#Mann=6,-1,0
  4601.6    0.08       0  4611.5    0.05       0  4861.2    0.12       0
  4991.6    0.07       0  4997.6    0.12       0  5163.8    0.05       0
Bank Sta=4991.6,4997.6
Exp/Cntr=0.3,0.1

Type RM Length L Ch R = 1,29069,113,113,113
BEGIN DESCRIPTION:
Mapping XS 98f8b741
END DESCRIPTION:
XS GIS Cut Line= 2
      3697443.26     10647798.92      3697172.43     10648590.58
#Sta/Elev= 30
  4664.3  330.34  4739.6  326.43  4760.8  321.48  4785.4  321.67  4816.7  318.59
  4824.2  316.10  4834.7  315.31  4855.9  310.24  4866.4  310.74  4872.3  309.50
  4879.3  308.42  4910.6  308.13  4982.7  309.29  4990.3  304.25  4993.0  303.75
  4996.3  304.25  5014.4  307.88  5061.9  309.38  5067.3  311.92  5093.2  314.88
  5119.2  314.52  5141.2  317.39  5155.9  317.74  5181.8  319.90  5225.8  321.23
  5236.4  322.73  5299.8  322.65  5331.5  325.01  5363.2  323.30  5501.0  324.82
#Mann=5,-1,0
  4664.3    0.05       0  4872.3    0.12       0  4990.3    0.07       0
  4996.3    0.12       0  5155.9    0.05       0
Bank Sta=4990.3,4996.3
Exp/Cntr=0.3,0.1

Type RM Length L Ch R = 1,28956,189,189,189
BEGIN DESCRIPTION:
Mapping XS 9174121d
END DESCRIPTION:
XS GIS Cut Line= 2
      3697375.55     10647762.46      3697029.22     10648548.88
#Sta/Elev= 30
  4676.7  330.37  4717.9  329.38  4794.4  324.35  4838.1  316.07  4870.5  311.41
  4882.4  311.23  4900.3  308.56  4971.4  307.66  4975.7  308.10  4988.1  303.31
  4990.8  302.81  4994.1  303.31  5004.5  304.07  5012.9  309.24  5051.2  312.62
  5121.2  314.15  5126.7  312.69  5150.0  315.04  5155.5  313.83  5173.3  314.79
  5202.1  313.23  5220.0  314.75  5240.5  314.65  5248.8  315.89  5254.2  314.73
  5265.8  315.17  5362.6  316.40  5394.2  318.47  5406.3  320.91  5536.0  323.99
#Mann=7,-1,0
  4676.7    0.05       0  4870.5    0.12       0  4971.4    0.05       0
  4988.1    0.04       0  4994.1    0.05       0  5240.5    0.08       0
  5265.8    0.05       0
Bank Sta=4988.1,4994.1
Exp/Cntr=0.3,0.1

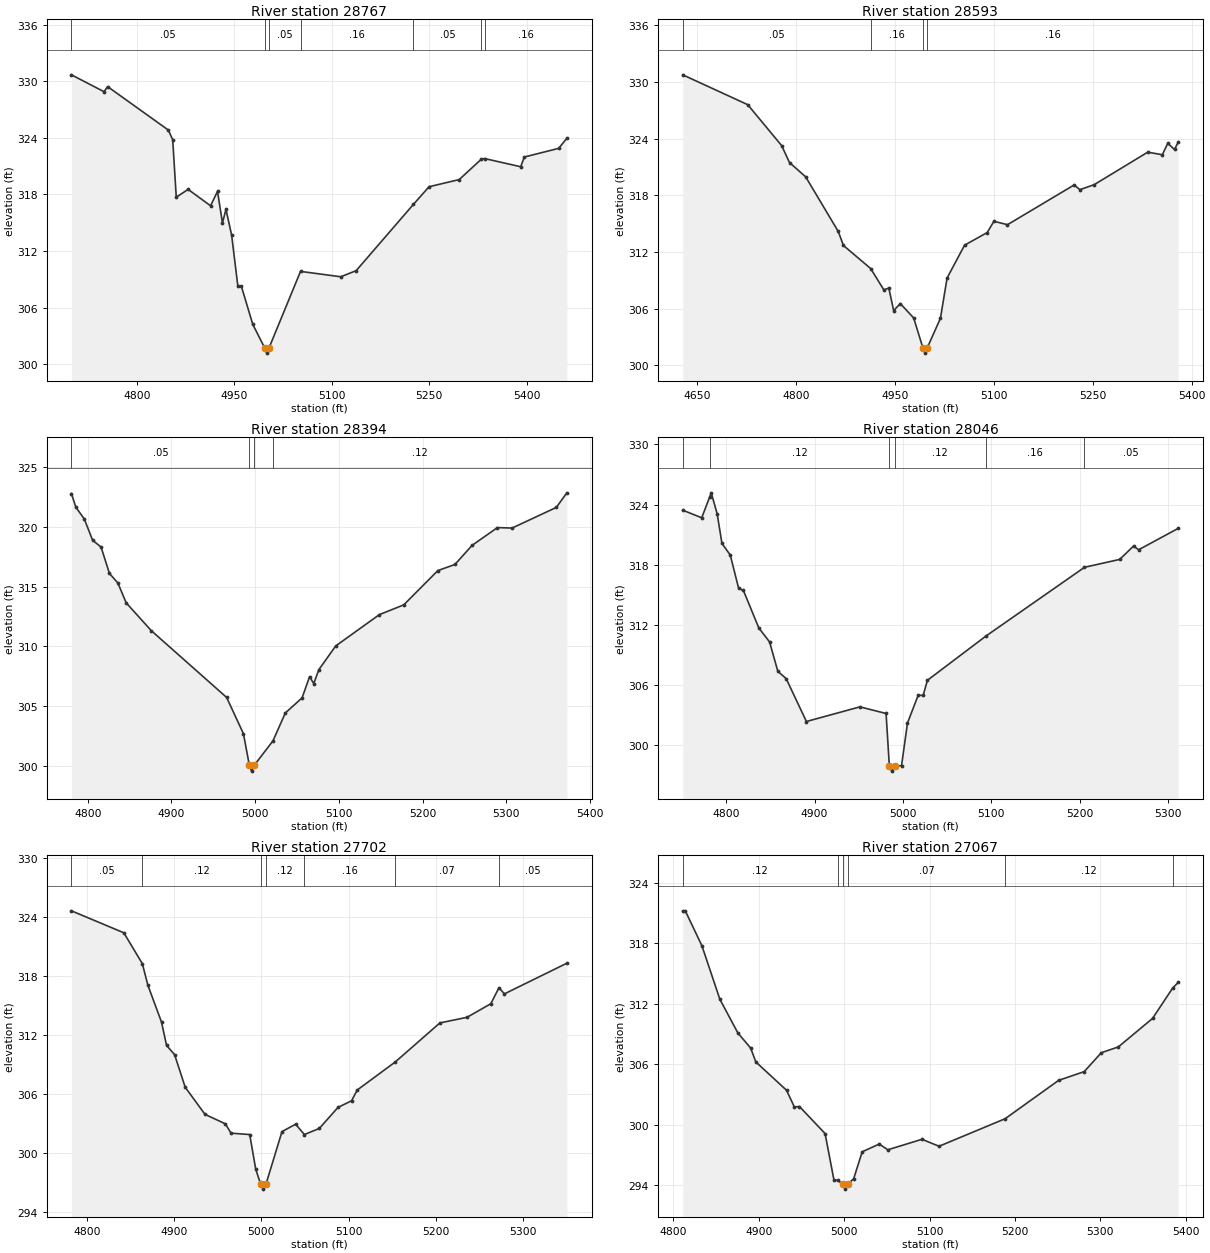
Type RM Length L Ch R = 1,28767,174,174,174
BEGIN DESCRIPTION:
UNT 0487 IN LACR 43.0
END DESCRIPTION:
XS GIS Cut Line= 2
      3697195.87     10647712.97      3696899.20     10648415.60
#Sta/Elev= 30
  4699.2  330.69  4749.4  328.90  4754.9  329.44  4848.2  324.84  4855.1  323.82
  4860.6  317.71  4878.8  318.54  4913.4  316.80  4924.1  318.33  4931.7  314.98
  4937.1  316.42  4945.8  313.70  4955.4  308.28  4960.8  308.26  4978.4  304.22
  4997.1  301.67  4999.9  301.17  5003.1  301.67  5051.9  309.84  5113.9  309.27
  5137.6  309.92  5225.6  316.94  5249.8  318.82  5296.2  319.58  5330.3  321.74
  5335.3  321.81  5390.9  320.94  5396.4  321.97  5449.3  322.89  5461.9  323.96
#Mann=7,-1,0
  4699.2    0.05       0  4997.1    0.03       0  5003.1    0.05       0
  5051.9    0.16       0  5225.6    0.05       0  5330.3    0.08       0
  5335.3    0.16       0
Bank Sta=4997.1,5003.1
Exp/Cntr=0.3,0.1

Type RM Length L Ch R = 1,28593,199,199,199
BEGIN DESCRIPTION:
Mapping XS e9d79257
END DESCRIPTION:
XS GIS Cut Line= 3
      3697034.42     10647686.91      3696935.45     10647975.99
      3696860.01     10648415.61
#Sta/Elev= 30
  4627.9  330.77  4726.5  327.61  4777.9  323.28  4789.9  321.48  4814.4  319.97
  4863.9  314.18  4871.7  312.70  4913.0  310.26  4933.0  308.00  4940.6  308.19
  4947.9  305.80  4958.0  306.55  4978.3  305.02  4992.5  301.80  4995.3  301.30
  4998.5  301.80  5018.9  304.99  5029.0  309.26  5055.5  312.73  5089.9  314.07
  5100.0  315.26  5120.6  314.90  5221.8  319.11  5230.5  318.61  5252.2  319.14
  5333.4  322.58  5355.5  322.31  5363.8  323.51  5374.0  322.87  5379.5  323.63
#Mann=4,-1,0
  4627.9    0.05       0  4913.0    0.16       0  4992.5    0.07       0
  4998.5    0.16       0
Bank Sta=4992.5,4998.5
Exp/Cntr=0.3,0.1

Type RM Length L Ch R = 1,28394,348,348,348
BEGIN DESCRIPTION:
UNT 0487 IN LACR 42.0
END DESCRIPTION:
XS GIS Cut Line= 3
      3696734.44     10647814.85      3696724.02     10648120.44
      3696776.11     10648401.70
#Sta/Elev= 30
  4780.5  322.79  4785.8  321.64  4795.8  320.67  4805.8  318.88  4815.9  318.31
  4825.9  316.10  4835.9  315.31  4845.9  313.64  4875.9  311.31  4965.9  305.72
  4986.0  302.68  4993.0  300.05  4995.7  299.55  4999.0  300.05  5021.3  302.09
  5036.0  304.42  5056.0  305.68  5065.0  307.46  5070.0  306.88  5076.0  308.04
  5096.2  310.03  5148.3  312.65  5177.5  313.47  5218.2  316.34  5238.6  316.85
  5259.1  318.45  5289.4  319.94  5306.9  319.90  5359.8  321.63  5372.3  322.85
#Mann=4,-1,0
  4780.5    0.05       0  4993.0    0.03       0  4999.0    0.05       0
  5021.3    0.12       0
Bank Sta=4993,4999
Exp/Cntr=0.3,0.1

Type RM Length L Ch R = 1,28046,344,344,344
BEGIN DESCRIPTION:
UNT 0487 IN LACR 41.0
END DESCRIPTION:
XS GIS Cut Line= 3
      3696499.60     10647860.20      3696399.61     10648110.19
      3696249.60     10648360.20
#Sta/Elev= 30
  4750.7  323.44  4772.2  322.68  4781.3  324.78  4783.0  325.17  4789.7  323.07
  4795.1  320.12  4804.5  318.97  4814.0  315.64  4819.3  315.45  4836.8  311.70
  4849.0  310.30  4858.4  307.36  4867.8  306.64  4890.7  302.36  4951.3  303.82
  4980.9  303.16  4984.6  297.91  4987.4  297.41  4990.6  297.91  4998.4  297.95
  5005.1  302.20  5017.2  304.97  5022.9  304.97  5027.7  306.47  5093.9  310.88
  5205.5  317.74  5245.4  318.53  5261.0  319.86  5266.8  319.49  5311.5  321.62
#Mann=6,-1,0
  4750.7    0.05       0  4781.3    0.12       0  4984.6    0.07       0
  4990.6    0.12       0  5093.9    0.16       0  5205.5    0.05       0
Bank Sta=4984.6,4990.6
Exp/Cntr=0.3,0.1

Type RM Length L Ch R = 1,27702,635,635,635
BEGIN DESCRIPTION:
UNT 0487 IN LACR 40.0
END DESCRIPTION:
XS GIS Cut Line= 2
      3696258.72     10647738.53      3695967.92     10648226.68
#Sta/Elev= 30
  4782.1  324.60  4842.2  322.37  4863.4  319.24  4869.8  317.04  4885.4  313.31
  4891.2  310.94  4900.4  310.00  4912.6  306.69  4935.3  303.94  4958.6  302.98
  4965.2  302.03  4986.6  301.89  4993.5  298.36  4999.2  296.85  5002.0  296.35
  5005.2  296.85  5023.6  302.19  5039.2  302.94  5049.3  301.89  5066.4  302.51
  5087.9  304.65  5103.4  305.32  5109.9  306.41  5153.7  309.27  5204.7  313.22
  5235.8  313.79  5263.1  315.17  5272.5  316.80  5278.7  316.17  5350.3  319.28
#Mann=7,-1,0
  4782.1    0.05       0  4863.4    0.12       0  4999.2    0.07       0
  5005.2    0.12       0  5049.3    0.16       0  5153.7    0.07       0
  5272.5    0.05       0
Bank Sta=4999.2,5005.2
Exp/Cntr=0.3,0.1

Type RM Length L Ch R = 1,27067,734,734,734
BEGIN DESCRIPTION:
UNT 0487 IN LACR 39.0
END DESCRIPTION:
XS GIS Cut Line= 3
      3695849.58     10647410.23      3695749.61     10647560.19
      3695749.61     10647960.16
#Sta/Elev= 30
  4810.9  321.20  4813.9  321.20  4833.4  317.73  4854.4  312.43  4875.5  309.09
  4890.5  307.59  4896.5  306.22  4932.5  303.41  4941.6  301.76  4947.6  301.80
  4977.6  299.12  4988.1  294.48  4992.4  294.48  4998.1  294.11  5000.9  293.61
  5004.1  294.11  5011.1  294.64  5021.1  297.31  5041.1  298.08  5051.1  297.51
  5091.1  298.55  5111.1  297.86  5188.5  300.59  5251.1  304.39  5281.1  305.26
  5301.1  307.13  5321.1  307.71  5361.1  310.53  5384.6  313.53  5391.1  314.10
#Mann=6,-1,0
  4810.9    0.12       0  4992.4    0.07       0  4998.1    0.07       0
  5004.1    0.07       0  5188.5    0.12       0  5384.6    0.16       0
Bank Sta=4998.1,5004.1
Exp/Cntr=0.3,0.1

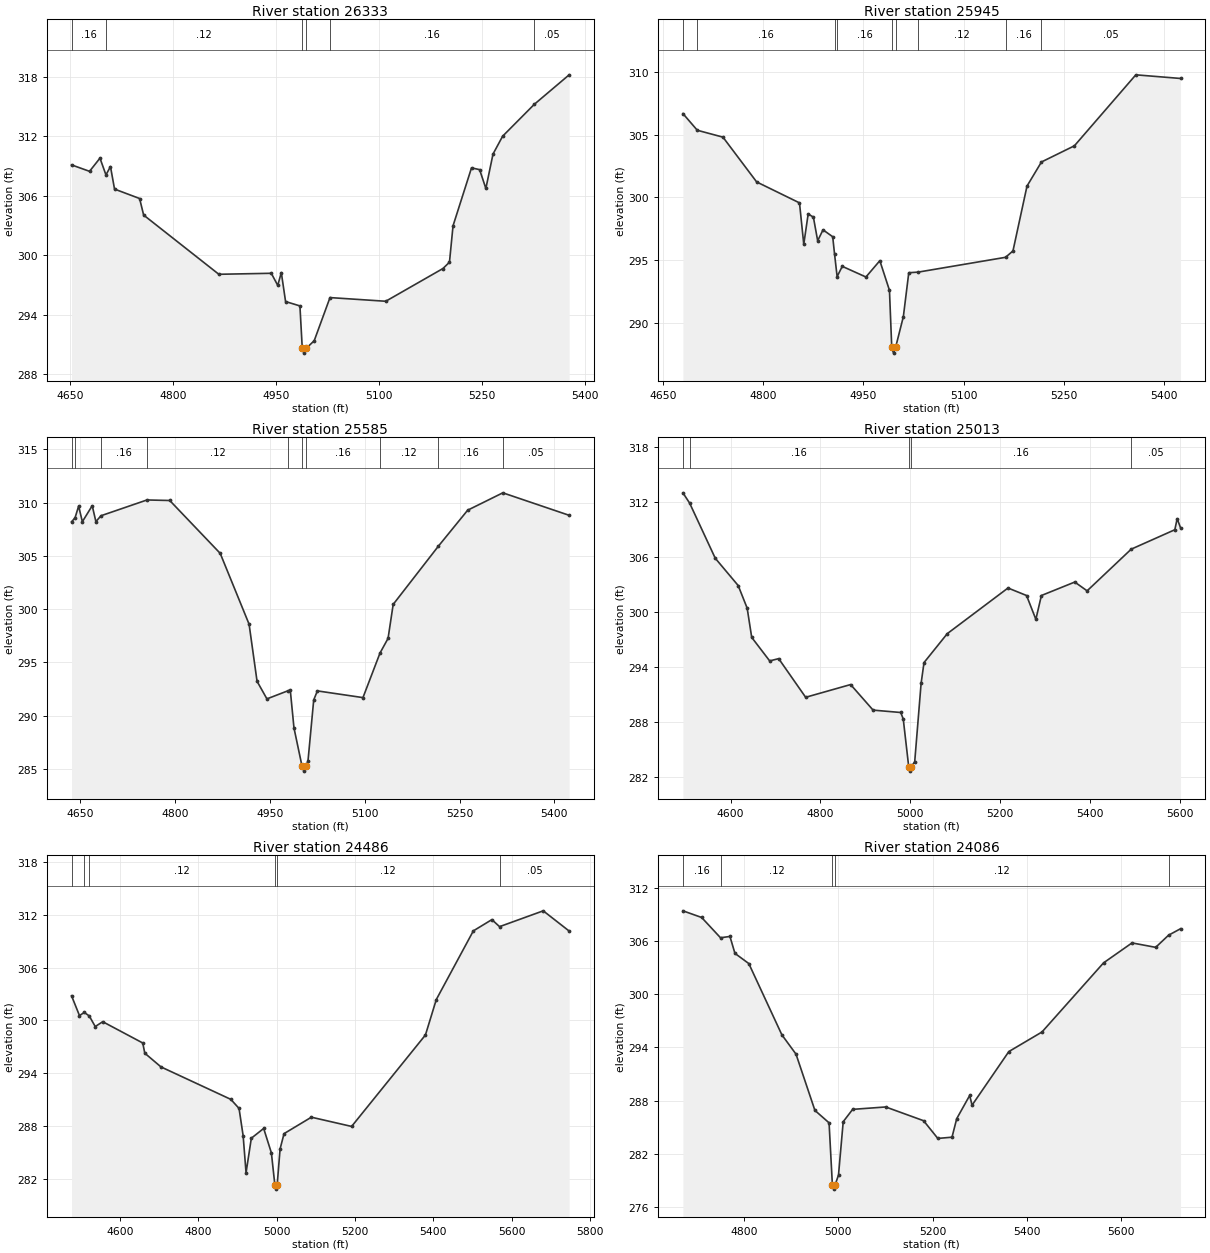
Type RM Length L Ch R = 1,26333,388,388,388
BEGIN DESCRIPTION:
UNT 0487 IN LACR 38.0
END DESCRIPTION:
XS GIS Cut Line= 3
      3695477.51     10647311.39      3695335.13     10647537.11
      3695207.07     10647976.67
#Sta/Elev= 30
  4652.1  309.10  4678.3  308.45  4693.5  309.78  4702.2  308.09  4708.8  308.93
  4714.7  306.66  4751.2  305.71  4757.1  304.04  4866.6  298.07  4943.0  298.17
  4952.4  296.95  4957.6  298.24  4963.8  295.32  4984.7  294.88  4988.1  290.62
  4990.9  290.12  4994.1  290.62  5005.5  291.37  5028.5  295.72  5109.7  295.35
  5193.0  298.65  5202.5  299.29  5207.7  302.96  5234.6  308.80  5246.4  308.62
  5255.5  306.72  5265.9  310.19  5279.9  311.99  5326.1  315.21  5376.8  318.18
#Mann=6,-1,0
  4652.1    0.16       0  4702.2    0.12       0  4988.1    0.07       0
  4994.1    0.12       0  5028.5    0.16       0  5326.1    0.05       0
Bank Sta=4988.1,4994.1
Exp/Cntr=0.3,0.1

Type RM Length L Ch R = 1,25945,360,360,360
BEGIN DESCRIPTION:
UNT 0487 IN LACR 37.0
END DESCRIPTION:
XS GIS Cut Line= 3
      3695346.60     10647163.21      3695092.08     10647485.02
      3694845.58     10647710.69
#Sta/Elev= 30
  4679.9  306.67  4701.4  305.34  4739.8  304.79  4790.2  301.22  4854.3  299.55
  4860.7  296.25  4867.3  298.67  4875.1  298.41  4881.5  296.53  4889.5  297.40
  4904.0  296.85  4906.8  295.45  4910.6  293.67  4918.3  294.49  4953.7  293.64
  4974.5  294.94  4988.9  292.58  4992.3  288.07  4995.0  287.57  4998.3  288.07
  5009.7  290.48  5017.8  293.98  5031.9  294.03  5162.6  295.21  5173.7  295.72
  5194.7  300.89  5216.3  302.81  5265.6  304.10  5357.5  309.76  5424.4  309.47
#Mann=9,-1,0
  4679.9    0.12       0  4701.4    0.16       0  4906.8    0.12       0
  4910.6    0.16       0  4992.3    0.07       0  4998.3    0.16       0
  5031.9    0.12       0  5162.6    0.16       0  5216.3    0.05       0
Bank Sta=4992.3,4998.3
Exp/Cntr=0.3,0.1

Type RM Length L Ch R = 1,25585,572,572,572
BEGIN DESCRIPTION:
UNT 0487 IN LACR 36.0
END DESCRIPTION:
XS GIS Cut Line= 3
      3695102.48     10646919.07      3694866.38     10647314.88
      3694762.22     10647623.92
#Sta/Elev= 30
  4636.3  308.20  4641.8  308.57  4647.5  309.67  4653.4  308.21  4669.0  309.71
  4674.8  308.22  4682.9  308.77  4755.6  310.25  4791.6  310.20  4871.4  305.24
  4917.1  298.59  4929.7  293.23  4945.3  291.58  4978.5  292.34  4982.3  292.37
  4988.1  288.85  5000.7  285.30  5003.5  284.80  5006.7  285.30  5010.2  285.72
  5019.3  291.48  5025.1  292.33  5097.2  291.70  5124.2  295.89  5136.9  297.26
  5145.0  300.45  5216.3  305.90  5262.8  309.29  5318.4  310.92  5423.3  308.81
#Mann=10,-1,0
  4636.3    0.16       0  4641.8    0.12       0  4682.9    0.16       0
  4755.6    0.12       0  4978.5    0.16       0  5000.7    0.07       0
  5006.7    0.16       0  5124.2    0.12       0  5216.3    0.16       0
  5318.4    0.05       0
Bank Sta=5000.7,5006.7
Exp/Cntr=0.3,0.1

Type RM Length L Ch R = 1,25013,527,527,527
BEGIN DESCRIPTION:
UNT 0487 IN LACR 35.0
END DESCRIPTION:
XS GIS Cut Line= 3
      3694533.05     10646957.27      3694542.15     10647400.55
      3694717.09     10648040.60
#Sta/Elev= 30
  4494.0  313.03  4509.0  311.90  4565.9  305.89  4616.9  302.91  4636.9  300.44
  4647.0  297.25  4687.0  294.68  4707.0  294.93  4767.0  290.71  4867.0  292.10
  4917.0  289.31  4978.5  289.05  4984.1  288.34  4996.2  283.15  4998.9  282.65
  5002.2  283.15  5009.6  283.68  5023.8  292.22  5030.3  294.50  5082.1  297.66
  5217.1  302.64  5258.4  301.82  5279.1  299.22  5291.4  301.82  5365.6  303.29
  5393.1  302.33  5491.2  306.88  5588.2  309.00  5593.4  310.21  5600.9  309.22
#Mann=5,-1,0
  4494.0    0.12       0  4509.0    0.16       0  4996.2    0.07       0
  5002.2    0.16       0  5491.2    0.05       0
Bank Sta=4996.2,5002.2
Exp/Cntr=0.3,0.1

Type RM Length L Ch R = 1,24486,400,400,400
BEGIN DESCRIPTION:
UNT 0487 IN LACR 34.0
END DESCRIPTION:
XS GIS Cut Line= 3
      3694029.58     10646922.53      3694221.66     10647529.82
      3694324.67     10648154.85
#Sta/Elev= 30
  4476.1  302.81  4496.3  300.56  4508.7  300.91  4521.2  300.52  4536.6  299.31
  4555.7  299.86  4657.9  297.44  4663.1  296.28  4704.4  294.72  4882.7  291.03
  4903.7  290.00  4914.2  286.89  4921.6  282.68  4935.1  286.61  4966.6  287.72
  4986.3  284.94  4995.1  281.32  4997.8  280.82  5001.1  281.32  5008.5  285.39
  5018.6  287.13  5088.4  289.00  5191.1  287.95  5379.6  298.35  5407.3  302.38
  5501.9  310.19  5549.2  311.47  5568.8  310.67  5680.3  312.47  5746.5  310.17
#Mann=6,-1,0
  4476.1    0.12       0  4508.7    0.16       0  4521.2    0.12       0
  4995.1    0.07       0  5001.1    0.12       0  5568.8    0.05       0
Bank Sta=4995.1,5001.1
Exp/Cntr=0.3,0.1

Type RM Length L Ch R = 1,24086,518,518,518
BEGIN DESCRIPTION:
UNT 0487 IN LACR 33.0
END DESCRIPTION:
XS GIS Cut Line= 3
      3693880.27     10647040.56      3693898.16     10647476.70
      3693956.66     10648092.62
#Sta/Elev= 30
  4670.6  309.42  4710.3  308.67  4750.3  306.38  4770.3  306.53  4780.9  304.62
  4810.3  303.47  4880.4  295.43  4910.4  293.25  4950.5  286.90  4980.5  285.50
  4987.5  278.52  4990.2  278.02  4993.5  278.52  5000.5  279.61  5010.5  285.63
  5030.5  287.02  5100.6  287.29  5180.9  285.74  5211.1  283.74  5241.2  283.88
  5251.2  285.97  5278.7  288.59  5283.7  287.49  5361.7  293.54  5432.0  295.75
  5562.6  303.55  5622.9  305.80  5673.1  305.30  5700.4  306.67  5725.8  307.40
#Mann=5,-1,0
  4670.6    0.16       0  4750.3    0.12       0  4987.5    0.07       0
  4993.5    0.12       0  5700.4    0.05       0
Bank Sta=4987.5,4993.5
Exp/Cntr=0.3,0.1

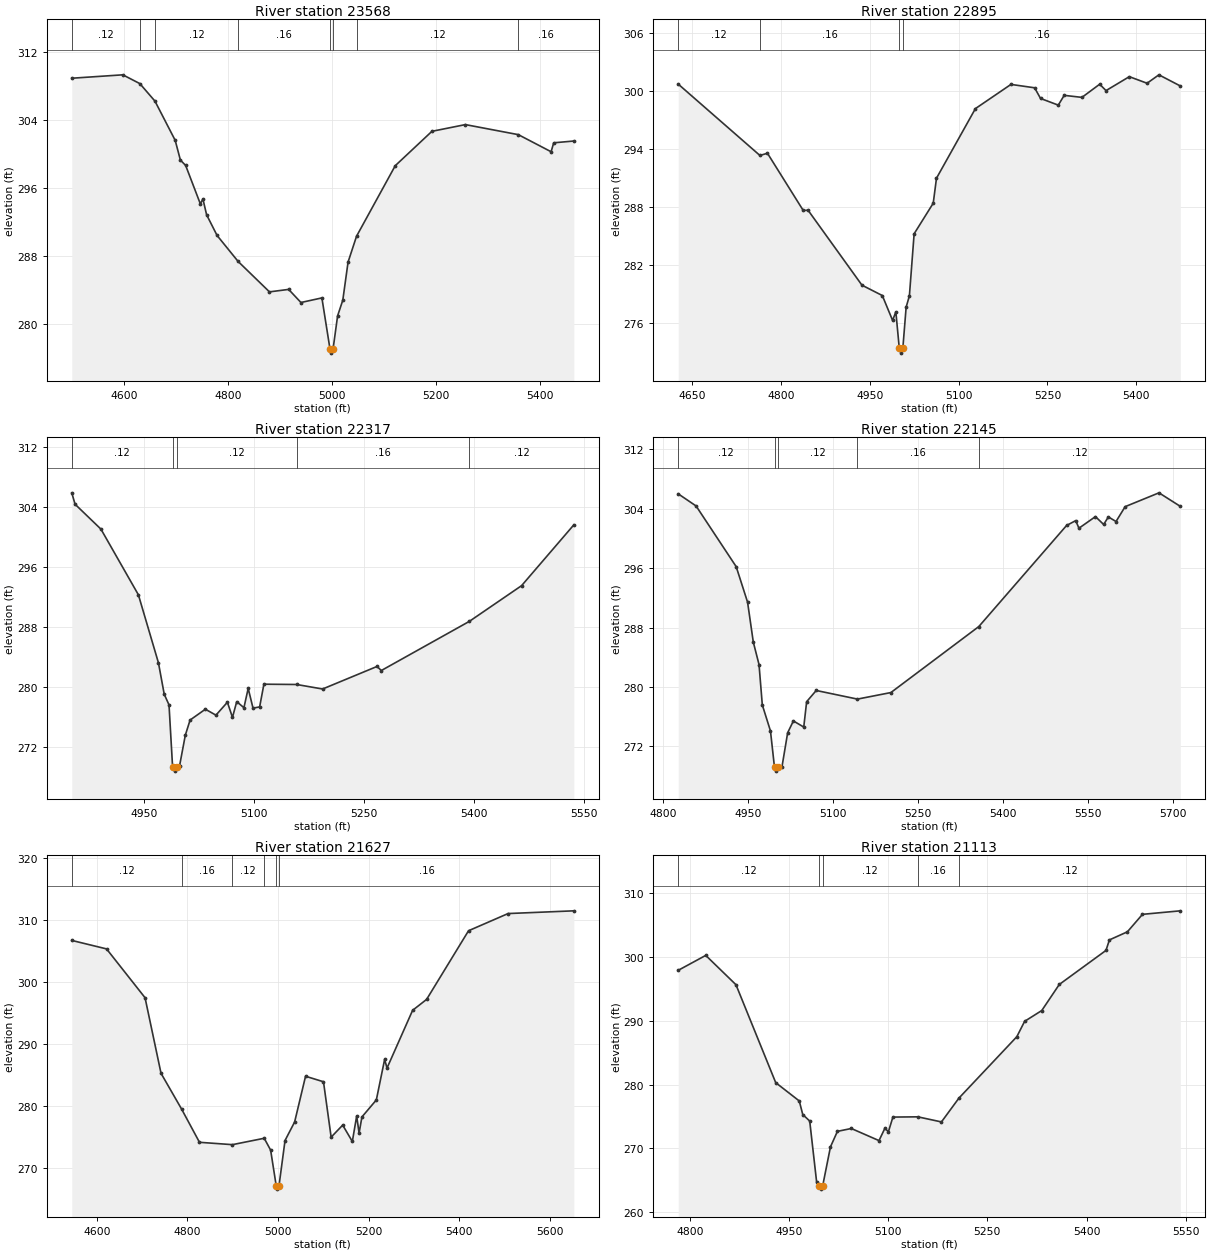
Type RM Length L Ch R = 1,23568,673,673,673
BEGIN DESCRIPTION:
UNT 0487 IN LACR 32.0
END DESCRIPTION:
XS GIS Cut Line= 2
      3693564.30     10647012.83      3693449.72     10647971.10
#Sta/Elev= 30
  4500.0  308.91  4598.1  309.31  4630.8  308.28  4659.9  306.22  4698.8  301.61
  4708.8  299.29  4718.9  298.66  4747.1  294.15  4752.1  294.71  4759.2  292.86
  4779.3  290.43  4819.7  287.38  4880.0  283.80  4916.9  284.09  4940.5  282.55
  4980.8  283.09  4996.3  277.10  4999.1  276.60  5002.3  277.10  5011.0  280.98
  5021.0  282.83  5031.1  287.30  5047.4  290.34  5121.8  298.63  5192.3  302.67
  5256.6  303.46  5358.3  302.28  5421.4  300.27  5426.4  301.32  5465.1  301.53
#Mann=8,-1,0
  4500.0    0.12       0  4630.8    0.16       0  4659.9    0.12       0
  4819.7    0.16       0  4996.3    0.07       0  5002.3    0.16       0
  5047.4    0.12       0  5358.3    0.16       0
Bank Sta=4996.3,5002.3
Exp/Cntr=0.3,0.1

Type RM Length L Ch R = 1,22895,578,578,578
BEGIN DESCRIPTION:
UNT 0487 IN LACR 31.0
END DESCRIPTION:
XS GIS Cut Line= 3
      3693328.18     10646988.51      3693143.91     10647385.22
      3693130.31     10647796.37
#Sta/Elev= 30
  4625.9  300.69  4764.0  293.32  4776.7  293.55  4837.2  287.64  4845.4  287.66
  4936.5  279.92  4970.9  278.85  4988.3  276.28  4993.8  277.17  4999.6  273.40
  5002.4  272.90  5005.6  273.40  5011.2  277.65  5016.7  278.82  5024.7  285.23
  5057.0  288.39  5062.5  290.97  5128.3  298.16  5188.4  300.66  5228.4  300.31
  5238.4  299.21  5268.4  298.52  5278.4  299.53  5308.4  299.32  5338.4  300.68
  5349.1  300.02  5388.5  301.46  5418.5  300.78  5438.5  301.65  5474.7  300.50
#Mann=4,-1,0
  4625.9    0.12       0  4764.0    0.16       0  4999.6    0.07       0
  5005.6    0.16       0
Bank Sta=4999.6,5005.6
Exp/Cntr=0.3,0.1

Type RM Length L Ch R = 1,22317,172,172,172
BEGIN DESCRIPTION:
UNT 0487 IN LACR 30.0
END DESCRIPTION:
XS GIS Cut Line= 3
      3693070.36     10646854.15      3692913.71     10646981.69
      3692668.17     10647395.99
#Sta/Elev= 30
  4852.0  305.84  4856.5  304.32  4891.7  301.01  4942.7  292.27  4970.0  283.22
  4977.9  279.03  4984.4  277.62  4989.3  269.30  4992.0  268.80  4995.3  269.30
  4998.7  269.47  5006.6  273.58  5013.1  275.60  5033.9  277.04  5048.3  276.25
  5063.9  277.97  5070.8  275.95  5076.6  278.05  5086.4  277.24  5092.2  279.81
  5098.8  277.18  5107.8  277.35  5113.6  280.37  5158.2  280.33  5193.5  279.73
  5267.6  282.73  5273.5  282.19  5393.3  288.73  5464.5  293.49  5535.6  301.58
#Mann=5,-1,0
  4852.0    0.12       0  4989.3    0.07       0  4995.3    0.12       0
  5158.2    0.16       0  5393.3    0.12       0
Bank Sta=4989.3,4995.3
Exp/Cntr=0.3,0.1

Type RM Length L Ch R = 1,22145,518,518,518
BEGIN DESCRIPTION:
UNT 0487 IN LACR 29.0
END DESCRIPTION:
XS GIS Cut Line= 3
      3692814.30     10646748.92      3692772.63     10647061.41
      3692498.31     10647561.45
#Sta/Elev= 30
  4826.6  305.98  4858.1  304.35  4928.8  296.19  4948.9  291.41  4959.0  286.04
  4969.1  283.02  4974.9  277.58  4989.3  274.08  4996.4  269.18  4999.1  268.68
  5002.4  269.18  5009.5  269.22  5019.6  273.84  5029.7  275.43  5048.0  274.61
  5053.1  278.02  5070.0  279.53  5142.7  278.37  5201.7  279.25  5356.8  288.13
  5511.6  301.73  5527.7  302.38  5533.4  301.36  5562.5  302.92  5577.0  301.86
  5585.3  302.88  5598.8  302.26  5614.9  304.26  5674.6  306.12  5712.2  304.30
#Mann=5,-1,0
  4826.6    0.12       0  4996.4    0.07       0  5002.4    0.12       0
  5142.7    0.16       0  5356.8    0.12       0
Bank Sta=4996.4,5002.4
Exp/Cntr=0.3,0.1

Type RM Length L Ch R = 1,21627,514,514,514
BEGIN DESCRIPTION:
UNT 0487 IN LACR 28.0
END DESCRIPTION:
XS GIS Cut Line= 3
      3692765.69     10646759.32      3692540.81     10647044.97
      3691838.62     10647294.04
#Sta/Elev= 30
  4544.5  306.75  4621.3  305.38  4706.3  297.51  4741.6  285.32  4786.9  279.57
  4826.5  274.20  4899.2  273.82  4969.4  274.85  4983.6  272.94  4996.0  267.15
  4998.7  266.65  5002.0  267.15  5015.4  274.49  5036.6  277.48  5060.7  284.85
  5100.3  283.96  5117.2  275.03  5142.7  276.97  5164.0  274.33  5173.6  278.44
  5178.9  275.68  5185.2  278.29  5217.0  281.03  5235.3  287.56  5240.6  286.17
  5297.1  295.48  5328.0  297.24  5420.6  308.31  5507.9  311.08  5653.1  311.52
#Mann=6,-1,0
  4544.5    0.12       0  4786.9    0.16       0  4899.2    0.12       0
  4969.4    0.16       0  4996.0    0.07       0  5002.0    0.16       0
Bank Sta=4996,5002
Exp/Cntr=0.3,0.1

Type RM Length L Ch R = 1,21113,566,566,566
BEGIN DESCRIPTION:
UNT 0487 IN LACR 27.0
END DESCRIPTION:
XS GIS Cut Line= 3
      3692686.85     10646623.30      3692517.57     10646631.11
      3691955.05     10646808.20
#Sta/Elev= 30
  4782.6  297.93  4824.2  300.27  4869.9  295.67  4930.0  280.31  4965.6  277.44
  4970.9  275.31  4981.4  274.29  4991.9  264.70  4995.0  264.11  4997.8  263.61
  5001.0  264.11  5012.8  270.24  5023.3  272.67  5044.3  273.12  5086.2  271.22
  5095.1  273.16  5100.4  272.61  5107.2  274.91  5144.8  274.95  5180.6  274.15
  5207.0  277.88  5294.6  287.52  5306.4  289.93  5332.3  291.62  5358.8  295.71
  5429.4  301.05  5434.6  302.70  5461.8  303.97  5484.6  306.71  5541.8  307.26
#Mann=5,-1,0
  4782.6    0.12       0  4995.0    0.07       0  5001.0    0.12       0
  5144.8    0.16       0  5207.0    0.12       0
Bank Sta=4995,5001
Exp/Cntr=0.3,0.1

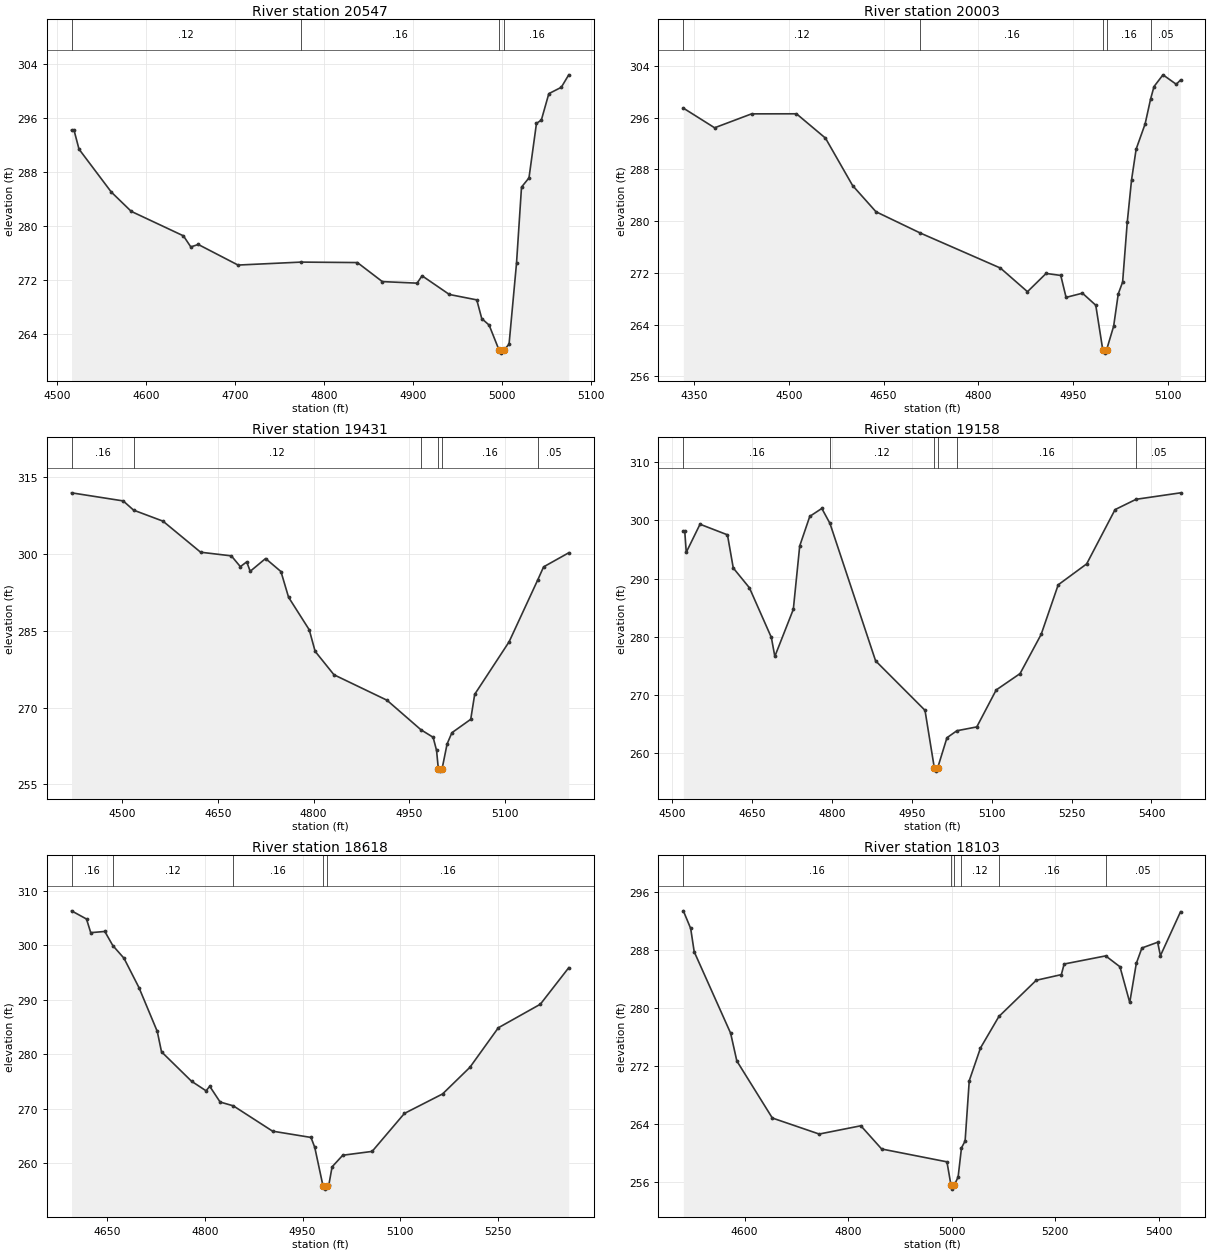
Type RM Length L Ch R = 1,20547,544,544,544
BEGIN DESCRIPTION:
UNT 0487 IN LACR 26.0
END DESCRIPTION:
XS GIS Cut Line= 3
      3692649.58     10646510.18      3692249.61     10646310.19
      3692149.60     10646260.18
#Sta/Elev= 30
  4516.5  294.18  4519.3  294.18  4524.9  291.37  4561.2  285.01  4583.6  282.15
  4642.3  278.52  4650.6  276.88  4659.0  277.24  4703.7  274.19  4774.6  274.63
  4837.9  274.56  4865.9  271.74  4905.0  271.51  4910.6  272.60  4941.3  269.83
  4972.1  269.03  4977.7  266.26  4986.0  265.29  4997.0  261.64  4999.8  261.14
  5003.0  261.64  5008.4  262.47  5016.8  274.49  5022.4  285.74  5030.8  287.11
  5039.2  295.18  5044.7  295.68  5053.1  299.59  5067.1  300.53  5075.5  302.38
#Mann=4,-1,0
  4516.5    0.12       0  4774.6    0.16       0  4997.0    0.07       0
  5003.0    0.16       0
Bank Sta=4997,5003
Exp/Cntr=0.3,0.1

Type RM Length L Ch R = 1,20003,572,572,572
BEGIN DESCRIPTION:
UNT 0487 IN LACR 25.0
END DESCRIPTION:
XS GIS Cut Line= 3
      3692983.73     10646352.47      3692460.28     10646042.57
      3692330.08     10645920.18
#Sta/Elev= 30
  4333.1  297.46  4382.6  294.42  4441.1  296.57  4512.2  296.58  4558.1  292.82
  4601.0  285.50  4638.0  281.45  4708.2  278.16  4835.0  272.75  4877.8  269.10
  4907.3  271.92  4930.5  271.61  4938.9  268.22  4964.8  268.87  4985.9  267.01
  4997.0  260.11  4999.8  259.61  5003.0  260.11  5014.2  263.77  5021.5  268.76
  5028.4  270.59  5035.7  279.79  5042.5  286.34  5049.8  291.12  5064.0  295.01
  5072.7  298.87  5078.1  300.79  5092.3  302.60  5113.3  301.14  5120.1  301.80
#Mann=5,-1,0
  4333.1    0.12       0  4708.2    0.16       0  4997.0    0.07       0
  5003.0    0.16       0  5072.7    0.05       0
Bank Sta=4997,5003
Exp/Cntr=0.3,0.1

Type RM Length L Ch R = 1,19431,273,273,273
BEGIN DESCRIPTION:
UNT 0487 IN LACR 24.0
END DESCRIPTION:
XS GIS Cut Line= 2
      3693154.55     10645530.17      3692433.10     10645823.23
#Sta/Elev= 30
  4421.0  311.96  4501.9  310.38  4518.2  308.58  4564.2  306.43  4623.2  300.36
  4671.3  299.65  4685.4  297.54  4695.4  298.48  4700.8  296.63  4724.9  299.13
  4749.0  296.58  4760.9  291.57  4793.3  285.21  4802.5  281.01  4832.0  276.43
  4915.0  271.46  4968.1  265.70  4987.3  264.22  4992.7  261.64  4995.4  258.11
  4998.1  257.61  5001.4  258.11  5009.2  262.92  5016.7  265.11  5046.2  267.73
  5052.4  272.61  5106.3  282.87  5151.4  295.02  5160.3  297.50  5199.7  300.25
#Mann=6,-1,0
  4421.0    0.16       0  4518.2    0.12       0  4968.1    0.16       0
  4995.4    0.07       0  5001.4    0.16       0  5151.4    0.05       0
Bank Sta=4995.4,5001.4
Exp/Cntr=0.3,0.1

Type RM Length L Ch R = 1,19158,540,540,540
BEGIN DESCRIPTION:
UNT 0487 IN LACR 23.0
END DESCRIPTION:
XS GIS Cut Line= 3
      3693040.02     10645373.91      3692437.94     10645521.86
      3692144.39     10645630.77
#Sta/Elev= 30
  4521.5  298.11  4524.2  298.11  4527.0  294.53  4552.8  299.35  4604.3  297.53
  4615.2  291.84  4645.5  288.44  4686.7  279.91  4693.2  276.66  4727.9  284.74
  4739.9  295.62  4758.8  300.70  4781.4  302.06  4796.7  299.48  4882.3  275.90
  4975.0  267.41  4992.6  257.47  4995.4  256.97  4998.6  257.47  5016.2  262.70
  5034.8  263.90  5072.2  264.56  5108.6  270.90  5153.4  273.71  5193.0  280.44
  5225.0  288.95  5278.4  292.54  5331.7  301.86  5371.2  303.63  5454.6  304.74
#Mann=6,-1,0
  4521.5    0.16       0  4796.7    0.12       0  4992.6    0.07       0
  4998.6    0.12       0  5034.8    0.16       0  5371.2    0.05       0
Bank Sta=4992.6,4998.6
Exp/Cntr=0.3,0.1

Type RM Length L Ch R = 1,18618,515,515,515
BEGIN DESCRIPTION:
UNT 0487 IN LACR 22.0
END DESCRIPTION:
XS GIS Cut Line= 3
      3692699.60     10644860.19      3692349.61     10645060.19
      3692049.58     10645260.21
#Sta/Elev= 30
  4595.1  306.29  4618.1  304.79  4624.6  302.29  4646.2  302.51  4658.5  299.93
  4675.7  297.60  4698.7  292.22  4726.8  284.19  4733.3  280.46  4779.4  275.07
  4801.7  273.32  4807.4  274.14  4823.3  271.26  4843.6  270.56  4903.9  265.92
  4962.9  264.77  4968.7  262.95  4981.5  255.80  4984.3  255.30  4987.5  255.80
  4990.3  256.06  4995.3  259.38  5011.7  261.51  5056.8  262.21  5106.4  269.17
  5165.0  272.74  5207.0  277.62  5250.6  284.86  5315.2  289.18  5358.8  295.87
#Mann=5,-1,0
  4595.1    0.16       0  4658.5    0.12       0  4843.6    0.16       0
  4981.5    0.07       0  4987.5    0.16       0
Bank Sta=4981.5,4987.5
Exp/Cntr=0.3,0.1

Type RM Length L Ch R = 1,18103,378,378,378
BEGIN DESCRIPTION:
Mapping XS 27e619f3
END DESCRIPTION:
XS GIS Cut Line= 3
      3692550.45     10644703.77      3692126.80     10644752.38
      3691630.23     10644950.32
#Sta/Elev= 30
  4481.5  293.40  4495.7  290.97  4502.5  287.76  4572.9  276.54  4584.9  272.71
  4653.5  264.85  4744.1  262.64  4824.6  263.78  4864.8  260.58  4991.0  258.81
  4998.9  255.55  5001.6  255.05  5004.9  255.55  5012.6  256.73  5019.1  260.74
  5026.1  261.68  5034.1  269.99  5055.8  274.50  5091.4  278.84  5163.6  283.83
  5212.1  284.61  5217.5  286.07  5297.8  287.19  5325.4  285.69  5344.3  280.77
  5357.0  286.16  5367.8  288.28  5398.2  289.07  5403.6  287.22  5442.5  293.28
#Mann=6,-1,0
  4481.5    0.16       0  4998.9    0.07       0  5004.9    0.16       0
  5019.1    0.12       0  5091.4    0.16       0  5297.8    0.05       0
Bank Sta=4998.9,5004.9
Exp/Cntr=0.3,0.1