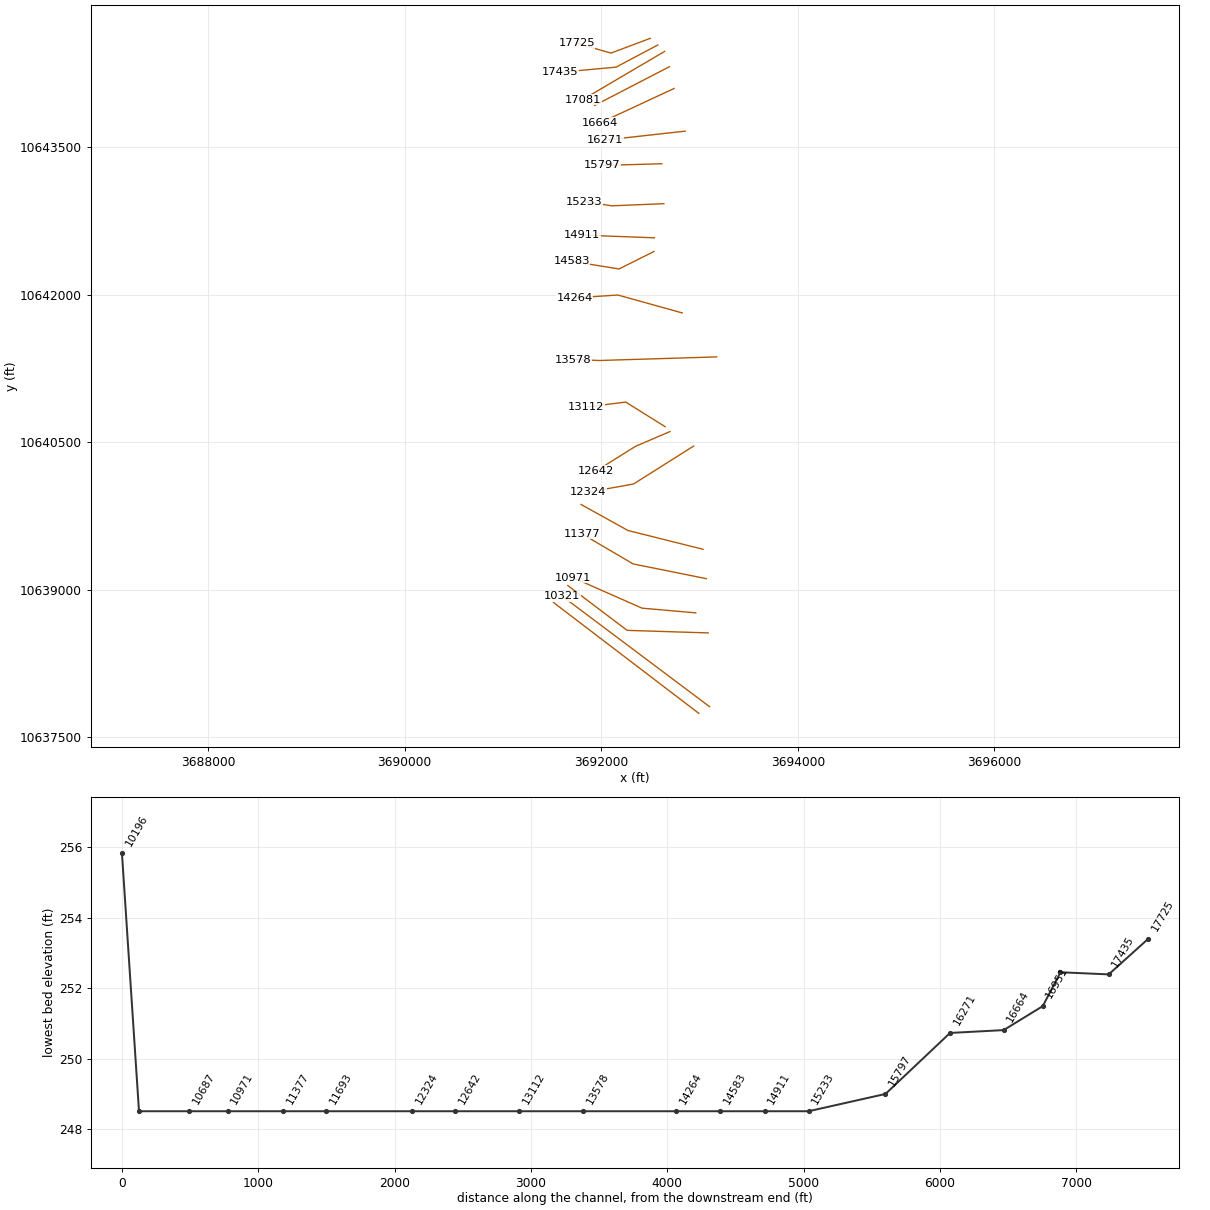
HEC-RAS study UNT 0487 IN LACR.prj: UNT 0487 IN LACR Base Level Engineering

--- UNT 0487 IN LACR.g01 (geometry) --- (continued)

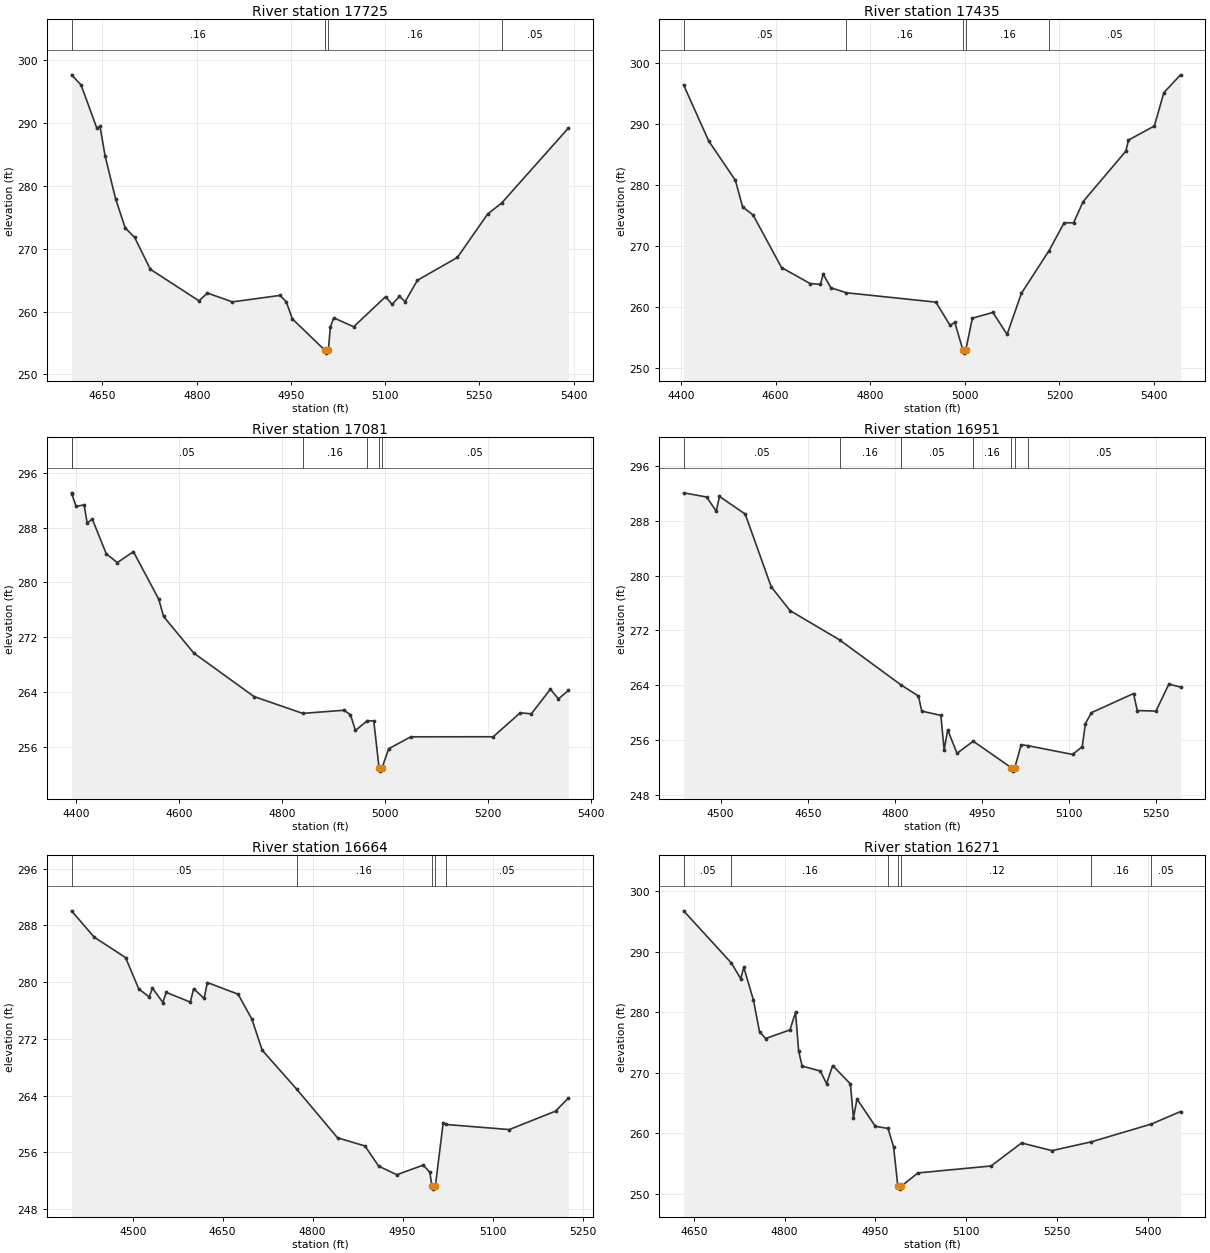
Type RM Length L Ch R = 1,17725,290,290,290
BEGIN DESCRIPTION:
UNT 0487 IN LACR 21.0
END DESCRIPTION:
XS GIS Cut Line= 3
      3692499.63     10644610.20      3692099.61     10644460.19
      3691749.64     10644560.18
#Sta/Elev= 30
  4600.7  297.71  4615.9  296.10  4640.8  289.28  4646.1  289.50  4654.1  284.82
  4671.0  277.93  4686.2  273.33  4701.3  271.81  4726.2  266.75  4803.6  261.73
  4817.0  262.96  4857.0  261.56  4932.7  262.59  4942.5  261.60  4952.3  258.86
  5003.6  253.90  5006.3  253.40  5009.6  253.90  5012.8  257.53  5018.1  259.02
  5050.0  257.60  5100.7  262.39  5111.1  261.16  5122.8  262.43  5131.9  261.60
  5151.4  265.00  5215.1  268.64  5263.2  275.54  5285.6  277.30  5391.9  289.25
#Mann=4,-1,0
  4600.7    0.16       0  5003.6    0.07       0  5009.6    0.16       0
  5285.6    0.05       0
Bank Sta=5003.6,5009.6
Exp/Cntr=0.3,0.1

Type RM Length L Ch R = 1,17435,354,354,354
BEGIN DESCRIPTION:
Mapping XS d2a6c414
END DESCRIPTION:
XS GIS Cut Line= 3
      3692576.38     10644542.79      3692151.06     10644317.11
      3691584.42     10644265.20
#Sta/Elev= 30
  4405.6  296.33  4458.5  287.18  4515.1  280.70  4530.3  276.34  4552.3  275.05
  4612.6  266.41  4672.9  263.80  4694.9  263.66  4700.6  265.36  4716.9  263.10
  4749.9  262.28  4938.8  260.75  4968.9  256.94  4978.9  257.42  4996.0  252.89
  4998.8  252.39  5002.0  252.89  5015.9  258.11  5059.3  259.06  5089.4  255.46
  5119.5  262.17  5178.2  269.20  5209.9  273.75  5230.0  273.75  5250.0  277.22
  5340.4  285.49  5346.0  287.31  5400.7  289.61  5420.8  295.09  5456.1  298.00
#Mann=5,-1,0
  4405.6    0.05       0  4749.9    0.16       0  4996.0    0.07       0
  5002.0    0.16       0  5178.2    0.05       0
Bank Sta=4996,5002
Exp/Cntr=0.3,0.1

Type RM Length L Ch R = 1,17081,130,130,130
BEGIN DESCRIPTION:
UNT 0487 IN LACR 20.0
END DESCRIPTION:
XS GIS Cut Line= 2
      3692645.81     10644477.68      3691813.55     10643987.86
#Sta/Elev= 30
  4390.8  293.09  4391.3  292.93  4399.8  291.11  4415.4  291.34  4421.2  288.65
  4431.1  289.26  4458.3  284.20  4479.8  282.90  4511.1  284.50  4560.4  277.54
  4569.7  275.04  4628.3  269.70  4745.4  263.34  4840.2  260.88  4920.1  261.34
  4932.8  260.70  4942.6  258.39  4965.7  259.82  4978.2  259.77  4988.4  252.95
  4991.1  252.45  4994.4  252.95  5007.0  255.71  5050.0  257.46  5210.2  257.47
  5262.8  260.97  5284.3  260.82  5321.4  264.41  5337.1  263.00  5356.5  264.25
#Mann=6,-1,0
  4390.8    0.08       0  4391.3    0.05       0  4840.2    0.16       0
  4965.7    0.05       0  4988.4    0.04       0  4994.4    0.05       0
Bank Sta=4988.4,4994.4
Exp/Cntr=0.3,0.1

Type RM Length L Ch R = 1,16951,287,287,287
BEGIN DESCRIPTION:
UNT 0487 IN LACR 19.0
END DESCRIPTION:
XS GIS Cut Line= 2
      3692693.62     10644321.46      3691933.26     10643927.63
#Sta/Elev= 30
  4436.2  292.05  4475.9  291.44  4492.4  289.37  4498.0  291.52  4542.3  288.96
  4587.1  278.36  4619.5  274.89  4704.9  270.62  4810.4  264.08  4840.9  262.43
  4846.5  260.24  4879.5  259.61  4885.1  254.59  4891.2  257.51  4907.3  254.09
  4935.3  255.85  5000.8  251.99  5003.6  251.49  5006.8  251.99  5017.9  255.33
  5028.9  255.21  5106.5  253.92  5123.0  255.06  5128.6  258.43  5138.9  260.01
  5211.5  262.80  5217.8  260.32  5250.1  260.24  5272.3  264.17  5292.5  263.74
#Mann=7,-1,0
  4436.2    0.05       0  4704.9    0.16       0  4810.4    0.05       0
  4935.3    0.16       0  5000.8    0.07       0  5006.8    0.16       0
  5028.9    0.05       0
Bank Sta=5000.8,5006.8
Exp/Cntr=0.3,0.1

Type RM Length L Ch R = 1,16664,393,393,393
BEGIN DESCRIPTION:
Mapping XS 9ddbdba5
END DESCRIPTION:
XS GIS Cut Line= 2
      3692741.34     10644100.10      3691990.16     10643750.62
#Sta/Elev= 30
  4398.0  290.06  4435.9  286.34  4488.1  283.47  4510.2  279.03  4527.5  277.92
  4533.0  279.16  4550.3  277.13  4555.9  278.56  4596.1  277.19  4601.6  279.08
  4619.0  277.70  4624.5  279.95  4675.8  278.30  4698.7  274.78  4716.0  270.39
  4773.3  264.92  4841.5  258.05  4887.2  256.90  4910.1  254.05  4940.3  252.84
  4984.5  254.20  4995.5  253.16  4998.7  251.31  5001.4  250.81  5004.7  251.31
  5017.6  260.12  5022.1  259.93  5127.8  259.21  5205.0  261.81  5226.5  263.66
#Mann=5,-1,0
  4398.0    0.05       0  4773.3    0.16       0  4998.7    0.07       0
  5004.7    0.16       0  5022.1    0.05       0
Bank Sta=4998.7,5004.7
Exp/Cntr=0.3,0.1

Type RM Length L Ch R = 1,16271,474,474,474
BEGIN DESCRIPTION:
UNT 0487 IN LACR 18.0
END DESCRIPTION:
XS GIS Cut Line= 2
      3692854.16     10643666.06      3692038.58     10643575.44
#Sta/Elev= 30
  4633.2  296.78  4711.8  288.17  4727.5  285.55  4732.5  287.45  4748.5  282.00
  4758.5  276.78  4768.6  275.65  4808.8  277.08  4818.0  279.99  4823.1  273.59
  4828.9  271.10  4859.1  270.26  4869.2  268.19  4879.3  271.18  4908.6  268.14
  4913.6  262.50  4919.5  265.64  4949.7  261.13  4970.7  260.77  4979.9  257.74
  4986.9  251.23  4989.7  250.73  4992.9  251.23  5020.1  253.41  5140.9  254.56
  5191.2  258.37  5241.5  257.10  5306.5  258.56  5405.6  261.50  5453.8  263.57
#Mann=7,-1,0
  4633.2    0.05       0  4711.8    0.16       0  4970.7    0.12       0
  4986.9    0.07       0  4992.9    0.12       0  5306.5    0.16       0
  5405.6    0.05       0
Bank Sta=4986.9,4992.9
Exp/Cntr=0.3,0.1

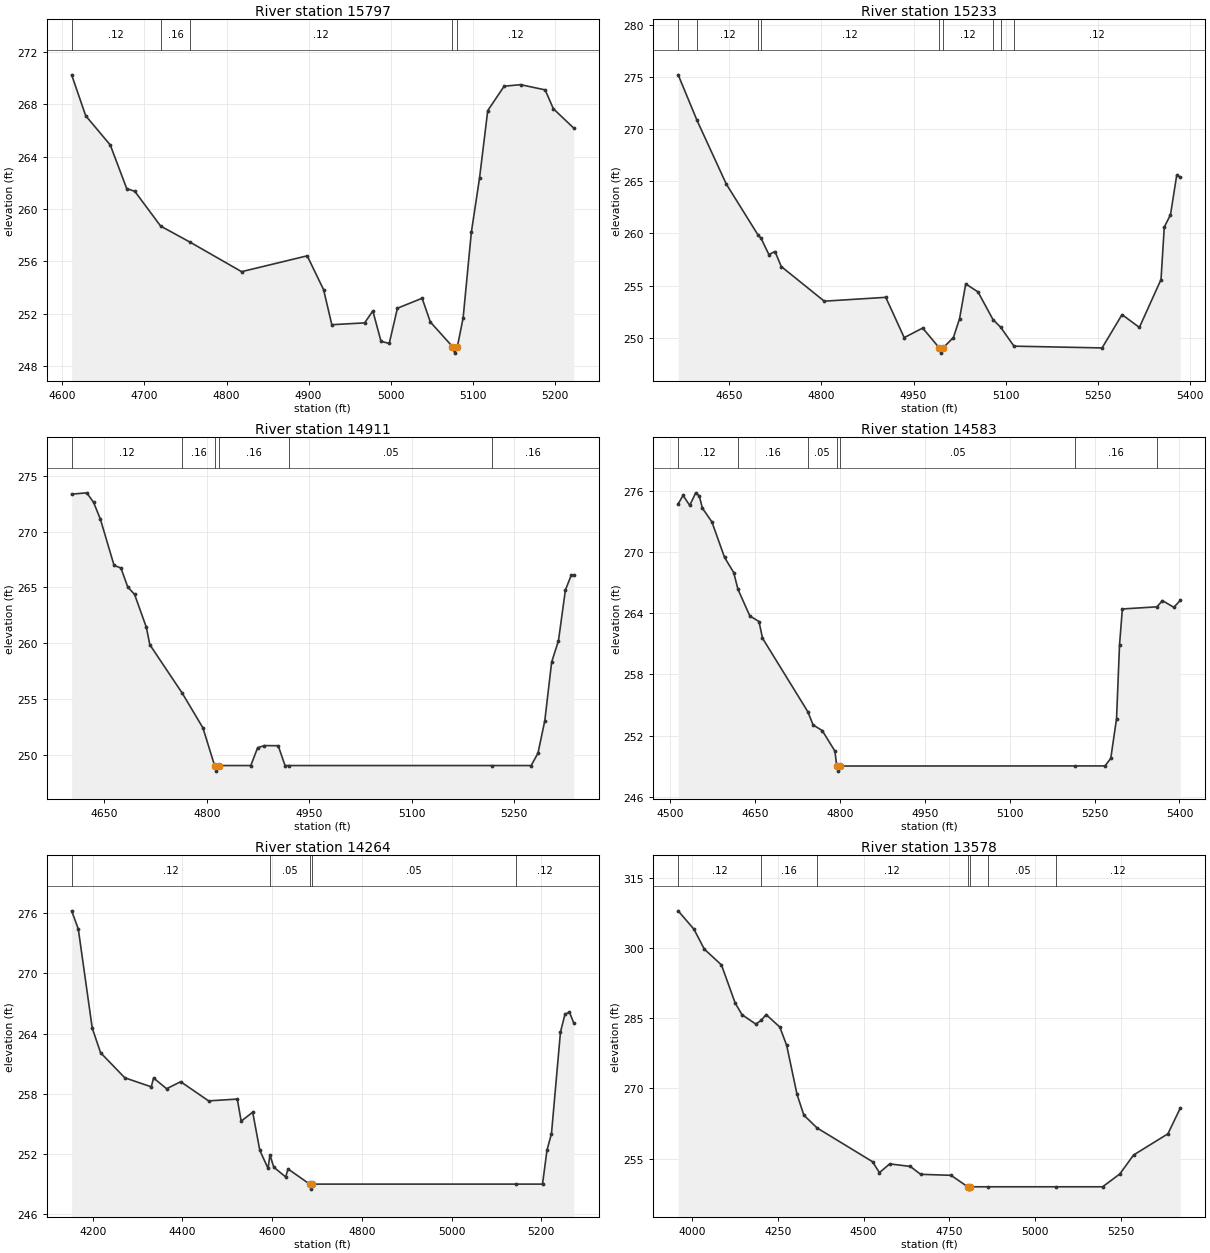
Type RM Length L Ch R = 1,15797,564,564,564
BEGIN DESCRIPTION:
UNT 0487 IN LACR 17.0
END DESCRIPTION:
XS GIS Cut Line= 3
      3692616.70     10643334.40      3692266.94     10643324.68
      3692004.76     10643316.71
#Sta/Elev= 30
  4611.2  270.25  4628.3  267.13  4658.3  264.89  4678.3  261.57  4688.3  261.35
  4719.7  258.70  4755.7  257.47  4818.4  255.22  4898.4  256.43  4918.4  253.84
  4928.4  251.17  4968.4  251.31  4978.4  252.22  4988.4  249.90  4998.4  249.74
  5008.4  252.43  5038.5  253.19  5048.5  251.38  5075.5  249.50  5078.2  249.00
  5081.5  249.50  5088.5  251.69  5098.5  258.22  5108.5  262.37  5118.5  267.52
  5138.5  269.38  5158.5  269.50  5188.5  269.10  5198.5  267.66  5223.4  266.18
#Mann=5,-1,0
  4611.2    0.12       0  4719.7    0.16       0  4755.7    0.12       0
  5075.5    0.07       0  5081.5    0.12       0
Bank Sta=5075.5,5081.5
Exp/Cntr=0.3,0.1

Type RM Length L Ch R = 1,15233,322,322,322
BEGIN DESCRIPTION:
UNT 0487 IN LACR 16.0
END DESCRIPTION:
XS GIS Cut Line= 3
      3692637.13     10642928.22      3692107.65     10642906.52
      3691823.78     10642949.97
#Sta/Elev= 30
  4567.0  275.24  4597.7  270.86  4645.3  264.75  4696.5  259.90  4701.9  259.54
  4714.6  257.98  4724.6  258.27  4734.7  256.83  4804.7  253.50  4904.8  253.87
  4934.8  250.00  4964.9  250.92  4991.9  249.01  4994.6  248.51  4997.9  249.01
  5014.9  250.01  5024.9  251.82  5034.9  255.16  5054.9  254.39  5079.3  251.73
  5092.0  250.98  5113.4  249.18  5256.8  249.01  5289.3  252.21  5317.5  250.98
  5352.7  255.58  5358.0  260.61  5368.1  261.80  5378.2  265.58  5384.1  265.42
#Mann=9,-1,0
  4567.0    0.16       0  4597.7    0.12       0  4696.5    0.16       0
  4701.9    0.12       0  4991.9    0.07       0  4997.9    0.12       0
  5079.3    0.16       0  5092.0    0.05       0  5113.4    0.12       0
Bank Sta=4991.9,4997.9
Exp/Cntr=0.3,0.1

Type RM Length L Ch R = 1,14911,328,328,328
BEGIN DESCRIPTION:
UNT 0487 IN LACR 15.0
END DESCRIPTION:
XS GIS Cut Line= 2
      3692541.65     10642581.00      3691807.27     10642608.58
#Sta/Elev= 30
  4602.3  273.35  4624.4  273.47  4634.4  272.62  4644.4  271.10  4664.4  266.96
  4674.4  266.73  4684.4  265.03  4694.4  264.36  4711.7  261.40  4716.7  259.85
  4764.3  255.49  4794.5  252.38  4811.5  249.01  4814.2  248.51  4817.5  249.01
  4864.5  249.01  4874.5  250.61  4884.5  250.80  4904.6  250.79  4914.6  249.01
  4920.5  249.01  5217.9  249.01  5274.8  249.01  5284.8  250.12  5294.8  253.04
  5304.8  258.29  5314.8  260.21  5324.9  264.74  5333.5  266.09  5337.2  266.09
#Mann=6,-1,0
  4602.3    0.12       0  4764.3    0.16       0  4811.5   0.033       0
  4817.5    0.16       0  4920.5    0.05       0  5217.9    0.16       0
Bank Sta=4811.5,4817.5
Exp/Cntr=0.3,0.1

Type RM Length L Ch R = 1,14583,319,319,319
BEGIN DESCRIPTION:
UNT 0487 IN LACR 14.0
END DESCRIPTION:
XS GIS Cut Line= 3
      3692537.33     10642442.10      3692181.44     10642264.16
      3691698.32     10642342.31
#Sta/Elev= 30
  4514.2  274.69  4522.8  275.53  4534.6  274.55  4545.2  275.78  4551.4  275.49
  4557.0  274.28  4573.8  272.93  4596.1  269.46  4612.3  267.97  4619.9  266.32
  4640.8  263.72  4657.0  263.17  4663.2  261.54  4743.3  254.33  4752.6  253.04
  4768.8  252.48  4791.2  250.47  4794.4  249.01  4797.1  248.51  4800.4  249.01
  5215.1  249.02  5268.5  249.02  5278.6  249.76  5288.8  253.64  5294.1  260.88
  5299.1  264.40  5360.3  264.61  5369.8  265.22  5390.1  264.56  5401.5  265.25
#Mann=7,-1,0
  4514.2    0.12       0  4619.9    0.16       0  4743.3    0.05       0
  4794.4   0.033       0  4800.4    0.05       0  5215.1    0.16       0
  5360.3    0.05       0
Bank Sta=4794.4,4800.4
Exp/Cntr=0.3,0.1

Type RM Length L Ch R = 1,14264,686,686,686
BEGIN DESCRIPTION:
UNT 0487 IN LACR 13.0
END DESCRIPTION:
XS GIS Cut Line= 3
      3692823.82     10641817.10      3692168.42     10641999.40
      3691730.02     10641969.42
#Sta/Elev= 30
  4152.9  276.23  4167.7  274.43  4198.8  264.55  4217.4  262.10  4271.4  259.60
  4330.4  258.70  4335.6  259.58  4364.7  258.51  4396.0  259.21  4458.3  257.30
  4522.3  257.48  4530.9  255.28  4556.6  256.17  4572.5  252.37  4590.8  250.58
  4595.1  251.91  4603.6  250.70  4630.2  249.72  4635.4  250.52  4683.6  249.01
  4686.4  248.51  4689.6  249.01  5143.9  249.01  5202.9  249.01  5212.9  252.40
  5222.9  254.05  5242.9  264.15  5253.0  265.93  5263.0  266.14  5272.6  265.05
#Mann=5,-1,0
  4152.9    0.12       0  4595.1    0.05       0  4683.6   0.033       0
  4689.6    0.05       0  5143.9    0.12       0
Bank Sta=4683.6,4689.6
Exp/Cntr=0.3,0.1

Type RM Length L Ch R = 1,13578,466,466,466
BEGIN DESCRIPTION:
UNT 0487 IN LACR 12.0
END DESCRIPTION:
XS GIS Cut Line= 3
      3693175.67     10641369.59      3691982.92     10641333.13
      3691713.50     10641342.88
#Sta/Elev= 30
  3959.6  307.91  4005.7  303.97  4035.7  299.74  4085.7  296.36  4125.7  288.22
  4145.7  285.73  4185.8  283.74  4201.1  284.51  4215.8  285.77  4255.8  283.09
  4275.8  279.17  4305.8  268.75  4325.8  264.30  4364.1  261.58  4525.9  254.36
  4545.9  252.03  4575.9  253.90  4636.0  253.35  4666.0  251.67  4754.6  251.46
  4803.1  249.01  4805.8  248.51  4809.1  249.01  4863.6  249.01  5061.3  249.01
  5196.2  249.01  5246.3  251.75  5286.3  255.79  5386.4  260.32  5422.5  265.82
#Mann=7,-1,0
  3959.6    0.12       0  4201.1    0.16       0  4364.1    0.12       0
  4803.1   0.033       0  4809.1    0.12       0  4863.6    0.05       0
  5061.3    0.12       0
Bank Sta=4803.1,4809.1
Exp/Cntr=0.3,0.1

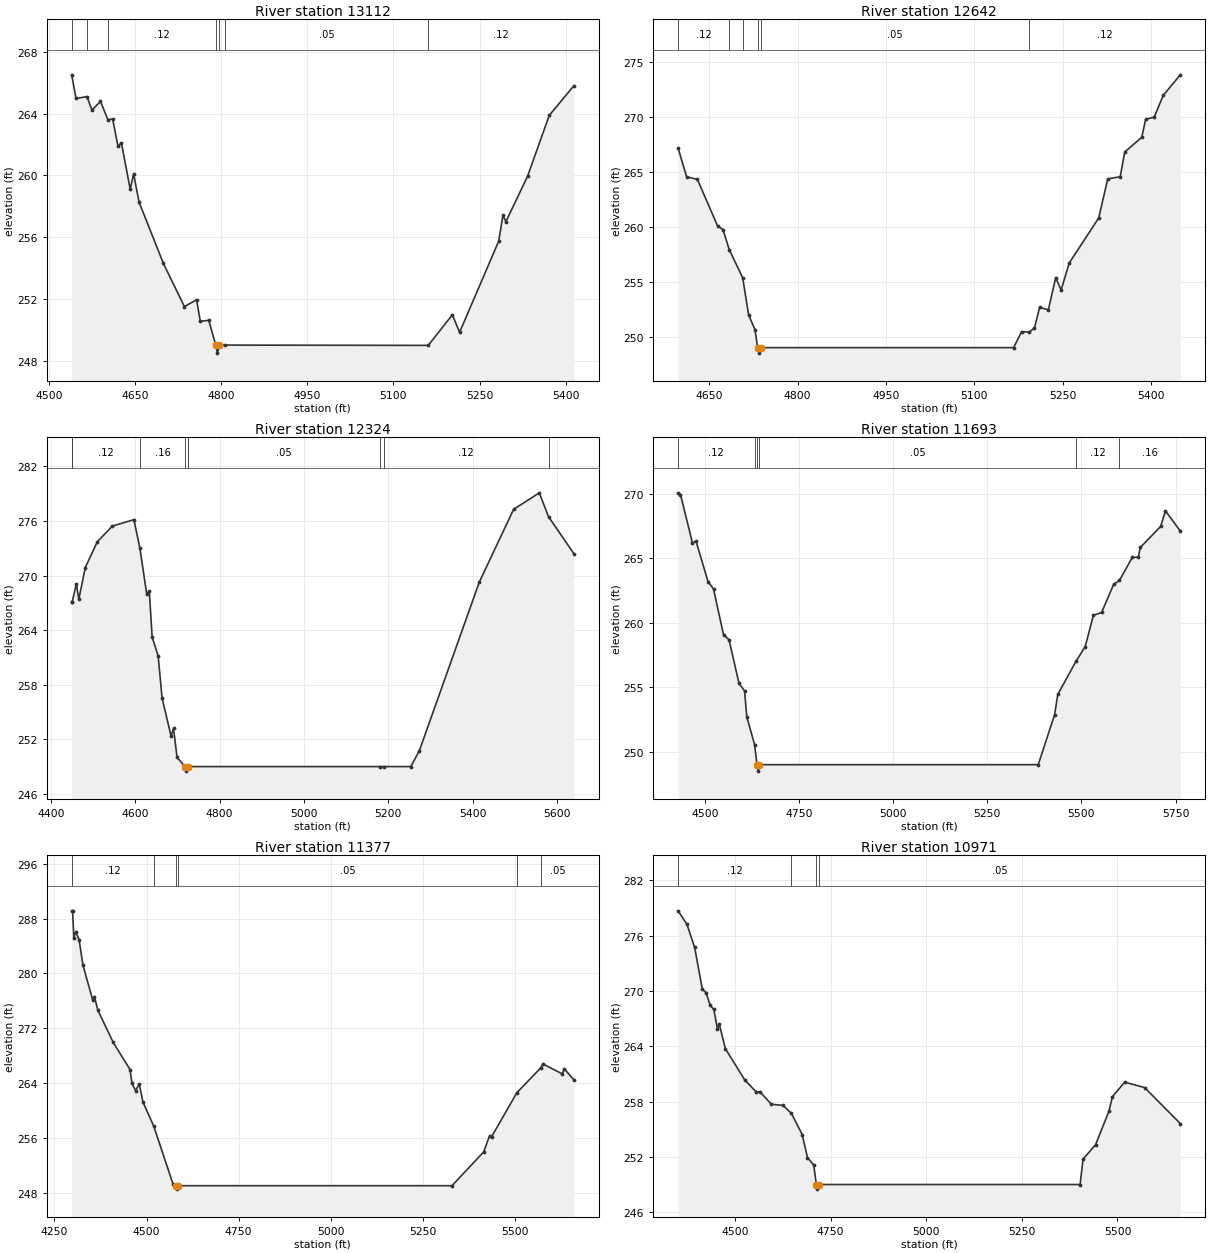
Type RM Length L Ch R = 1,13112,470,470,470
BEGIN DESCRIPTION:
UNT 0487 IN LACR 11.0
END DESCRIPTION:
XS GIS Cut Line= 3
      3692649.64     10640660.17      3692249.61     10640910.19
      3691849.66     10640860.19
#Sta/Elev= 30
  4539.5  266.51  4547.2  264.98  4566.3  265.10  4574.9  264.22  4589.7  264.80
  4602.7  263.60  4610.9  263.66  4620.3  261.88  4626.2  262.10  4641.5  259.11
  4647.4  260.11  4656.9  258.28  4699.3  254.31  4735.9  251.52  4757.1  251.96
  4763.6  250.57  4778.3  250.63  4790.7  249.01  4793.4  248.51  4796.7  249.01
  4807.5  249.03  5160.7  249.01  5202.7  250.99  5215.3  249.86  5283.3  255.74
  5290.9  257.44  5295.9  257.01  5333.7  259.95  5371.5  263.89  5414.3  265.80
#Mann=7,-1,0
  4539.5    0.12       0  4566.3    0.07       0  4602.7    0.12       0
  4790.7   0.033       0  4796.7    0.12       0  4807.5    0.05       0
  5160.7    0.12       0
Bank Sta=4790.7,4796.7
Exp/Cntr=0.3,0.1

Type RM Length L Ch R = 1,12642,318,318,318
BEGIN DESCRIPTION:
UNT 0487 IN LACR 10.0
END DESCRIPTION:
XS GIS Cut Line= 3
      3692699.65     10640610.20      3692349.61     10640460.19
      3691949.63     10640210.20
#Sta/Elev= 30
  4597.2  267.15  4611.7  264.55  4629.9  264.32  4664.3  260.07  4673.4  259.75
  4684.0  257.92  4706.8  255.37  4716.9  251.98  4727.8  250.63  4732.1  249.01
  4734.8  248.51  4738.1  249.01  5166.7  249.01  5180.3  250.46  5193.2  250.42
  5202.1  250.80  5210.9  252.67  5225.7  252.45  5238.1  255.36  5247.5  254.27
  5261.0  256.70  5311.2  260.81  5326.5  264.36  5347.7  264.56  5355.4  266.81
  5384.3  268.15  5390.8  269.77  5405.5  269.99  5420.8  271.97  5449.7  273.83
#Mann=6,-1,0
  4597.2    0.12       0  4684.0    0.16       0  4706.8    0.05       0
  4732.1   0.033       0  4738.1    0.05       0  5193.2    0.12       0
Bank Sta=4732.1,4738.1
Exp/Cntr=0.3,0.1

Type RM Length L Ch R = 1,12324,631,631,631
BEGIN DESCRIPTION:
UNT 0487 IN LACR 9.0
END DESCRIPTION:
XS GIS Cut Line= 3
      3692941.01     10640462.95      3692329.01     10640076.66
      3691868.96     10639994.19
#Sta/Elev= 30
  4449.2  267.05  4450.1  267.05  4460.3  269.06  4466.2  267.40  4481.5  270.89
  4510.0  273.71  4545.5  275.44  4596.8  276.15  4611.0  273.04  4627.3  267.93
  4633.3  268.32  4640.1  263.25  4654.4  261.16  4663.7  256.53  4685.0  252.36
  4690.9  253.20  4699.2  250.01  4718.5  249.01  4721.2  248.51  4724.5  249.01
  4725.2  249.01  5180.9  249.01  5188.9  249.01  5253.6  249.01  5273.9  250.76
  5416.1  269.29  5497.4  277.28  5558.4  279.10  5580.2  276.48  5640.3  272.42
#Mann=9,-1,0
  4449.2    0.16       0  4450.1    0.12       0  4611.0    0.16       0
  4718.5   0.033       0  4724.5    0.16       0  4725.2    0.05       0
  5180.9    0.07       0  5188.9    0.12       0  5580.2    0.16       0
Bank Sta=4718.5,4724.5
Exp/Cntr=0.3,0.1

Type RM Length L Ch R = 1,11693,316,316,316
BEGIN DESCRIPTION:
UNT 0487 IN LACR 8.0
END DESCRIPTION:
XS GIS Cut Line= 3
      3693036.50     10639412.59      3692272.58     10639603.57
      3691795.11     10639868.34
#Sta/Elev= 30
  4429.3  270.07  4435.6  269.94  4467.3  266.19  4476.9  266.32  4508.6  263.20
  4523.3  262.62  4549.8  259.09  4564.5  258.69  4591.0  255.30  4605.7  254.73
  4611.6  252.72  4632.3  250.57  4638.8  249.01  4641.5  248.51  4644.8  249.01
  5385.5  249.01  5429.0  252.89  5437.4  254.45  5485.5  257.01  5510.2  258.16
  5532.0  260.58  5553.7  260.80  5585.8  262.98  5601.1  263.28  5635.0  265.06
  5651.0  265.09  5656.7  265.84  5710.5  267.47  5723.3  268.67  5762.7  267.11
#Mann=6,-1,0
  4429.3    0.12       0  4632.3    0.05       0  4638.8   0.033       0
  4644.8    0.05       0  5485.5    0.12       0  5601.1    0.16       0
Bank Sta=4638.8,4644.8
Exp/Cntr=0.3,0.1

Type RM Length L Ch R = 1,11377,406,406,406
BEGIN DESCRIPTION:
UNT 0487 IN LACR 7.0
END DESCRIPTION:
XS GIS Cut Line= 3
      3693069.56     10639113.84      3692325.18     10639263.58
      3691804.48     10639569.49
#Sta/Elev= 30
  4296.8  289.12  4299.3  289.12  4302.7  285.21  4307.8  286.06  4317.1  284.88
  4327.3  281.24  4353.6  276.16  4358.7  276.59  4368.1  274.60  4409.6  269.92
  4455.3  265.96  4460.4  263.95  4470.2  262.90  4480.4  263.83  4490.6  261.18
  4519.4  257.73  4572.2  249.21  4579.4  249.01  4582.1  248.51  4585.4  249.01
  5329.3  249.01  5415.4  253.95  5431.1  256.28  5436.9  256.17  5505.5  262.59
  5571.0  266.25  5575.6  266.79  5628.4  265.33  5634.2  266.05  5660.0  264.46
#Mann=6,-1,0
  4296.8    0.12       0  4519.4    0.05       0  4579.4   0.033       0
  4585.4    0.05       0  5505.5    0.16       0  5571.0    0.05       0
Bank Sta=4579.4,4585.4
Exp/Cntr=0.3,0.1

Type RM Length L Ch R = 1,10971,284,284,284
BEGIN DESCRIPTION:
UNT 0487 IN LACR 6.0
END DESCRIPTION:
XS GIS Cut Line= 3
      3692962.66     10638765.89      3692415.81     10638813.63
      3691717.07     10639121.78
#Sta/Elev= 30
  4351.7  278.69  4374.8  277.22  4394.9  274.72  4415.0  270.19  4425.0  269.81
  4435.1  268.47  4445.1  267.99  4454.3  265.89  4459.4  266.38  4475.2  263.74
  4525.4  260.38  4555.5  259.06  4565.6  259.06  4595.7  257.71  4625.8  257.59
  4647.8  256.73  4676.0  254.43  4689.8  251.93  4706.1  251.12  4713.1  249.01
  4715.9  248.51  4719.1  249.01  5402.4  249.01  5410.1  251.76  5442.9  253.33
  5477.8  256.96  5486.7  258.53  5519.0  260.11  5571.1  259.52  5664.3  255.62
#Mann=4,-1,0
  4351.7    0.12       0  4647.8    0.05       0  4713.1   0.033       0
  4719.1    0.05       0
Bank Sta=4713.1,4719.1
Exp/Cntr=0.3,0.1

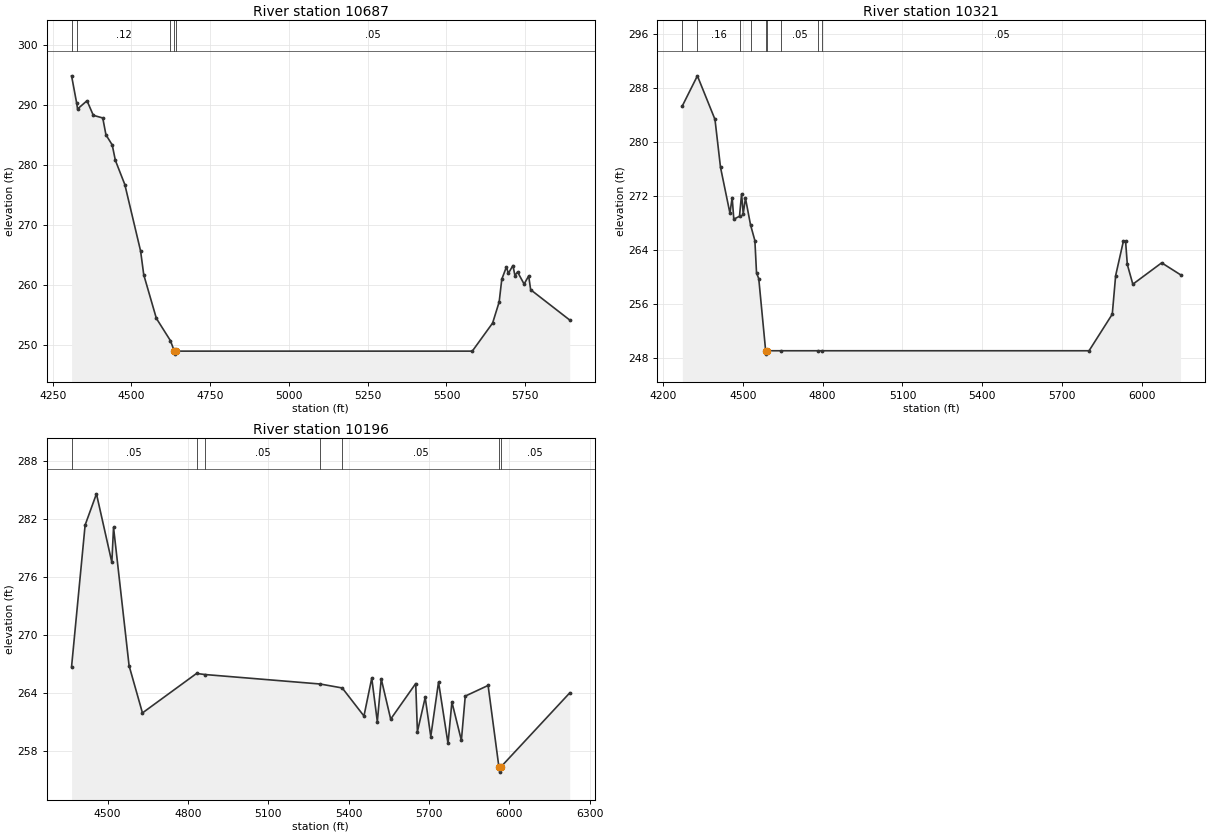
Type RM Length L Ch R = 1,10687,366,366,366
BEGIN DESCRIPTION:
UNT 0487 IN LACR 5.0
END DESCRIPTION:
XS GIS Cut Line= 3
      3693088.56     10638561.90      3692263.90     10638587.94
      3691660.64     10639043.64
#Sta/Elev= 30
  4310.0  294.87  4326.3  290.29  4329.0  289.35  4359.0  290.72  4379.0  288.29
  4409.0  287.85  4419.1  285.04  4439.0  283.36  4449.0  280.79  4479.0  276.76
  4529.1  265.68  4539.1  261.72  4579.1  254.47  4623.6  250.77  4636.1  249.01
  4638.9  248.51  4642.1  249.01  5581.9  249.01  5646.4  253.69  5667.2  257.21
  5675.5  260.99  5690.1  263.02  5696.4  261.97  5710.9  263.27  5717.2  261.60
  5725.5  262.20  5746.3  260.18  5760.9  261.54  5767.1  259.24  5891.1  254.19
#Mann=5,-1,0
  4310.0    0.07       0  4326.3    0.12       0  4623.6    0.05       0
  4636.1   0.033       0  4642.1    0.05       0
Bank Sta=4636.1,4642.1
Exp/Cntr=0.3,0.1

Type RM Length L Ch R = 1,10321,125,125,125
BEGIN DESCRIPTION:
UNT 0487 IN LACR 4.0
END DESCRIPTION:
XS GIS Cut Line= 2
      3693102.48     10637811.49      3691604.40     10638935.05
#Sta/Elev= 30
  4272.6  285.30  4329.1  289.75  4395.2  283.29  4416.0  276.19  4451.4  269.41
  4459.8  271.71  4466.0  268.50  4487.4  268.94  4495.2  272.24  4501.4  269.33
  4509.8  271.62  4528.8  267.68  4545.2  265.33  4551.4  260.54  4559.8  259.69
  4585.7  249.01  4588.4  248.51  4591.7  249.01  4642.8  249.01  4783.6  249.01
  4798.3  249.01  5801.4  249.01  5888.7  254.43  5901.4  260.15  5930.6  265.27
  5938.7  265.25  5945.2  261.80  5966.0  258.87  6074.4  262.04  6145.2  260.27
#Mann=9,-1,0
  4272.6    0.05       0  4329.1    0.16       0  4487.4    0.05       0
  4528.8    0.16       0  4585.7   0.033       0  4591.7    0.16       0
  4642.8    0.05       0  4783.6    0.16       0  4798.3    0.05       0
Bank Sta=4585.7,4591.7
Exp/Cntr=0.3,0.1

Type RM Length L Ch R = 1,10196,107,107,107
BEGIN DESCRIPTION:
UNT 0487 IN LACR 3.0
END DESCRIPTION:
XS GIS Cut Line= 2
      3692993.48     10637743.42      3691514.45     10638871.78
#Sta/Elev= 30
  4365.3  266.72  4415.9  281.36  4458.2  284.59  4515.7  277.51  4522.0  281.12
  4580.1  266.82  4630.0  261.94  4832.0  266.02  4863.2  265.91  5293.6  264.93
  5376.1  264.52  5457.2  261.62  5486.3  265.54  5507.1  261.04  5521.7  265.46
  5557.0  261.30  5650.5  264.98  5656.8  260.00  5685.9  263.54  5706.7  259.50
  5735.7  265.13  5771.1  258.78  5785.6  263.07  5821.0  259.10  5835.5  263.68
  5920.8  264.78  5961.3  256.32  5964.1  255.82  5967.3  256.32  6225.6  264.01
#Mann=7,-1,0
  4365.3    0.05       0  4832.0    0.16       0  4863.2    0.05       0
  5293.6    0.08       0  5376.1    0.05       0  5961.3    0.03       0
  5967.3    0.05       0
Bank Sta=5961.3,5967.3
Exp/Cntr=0.3,0.1