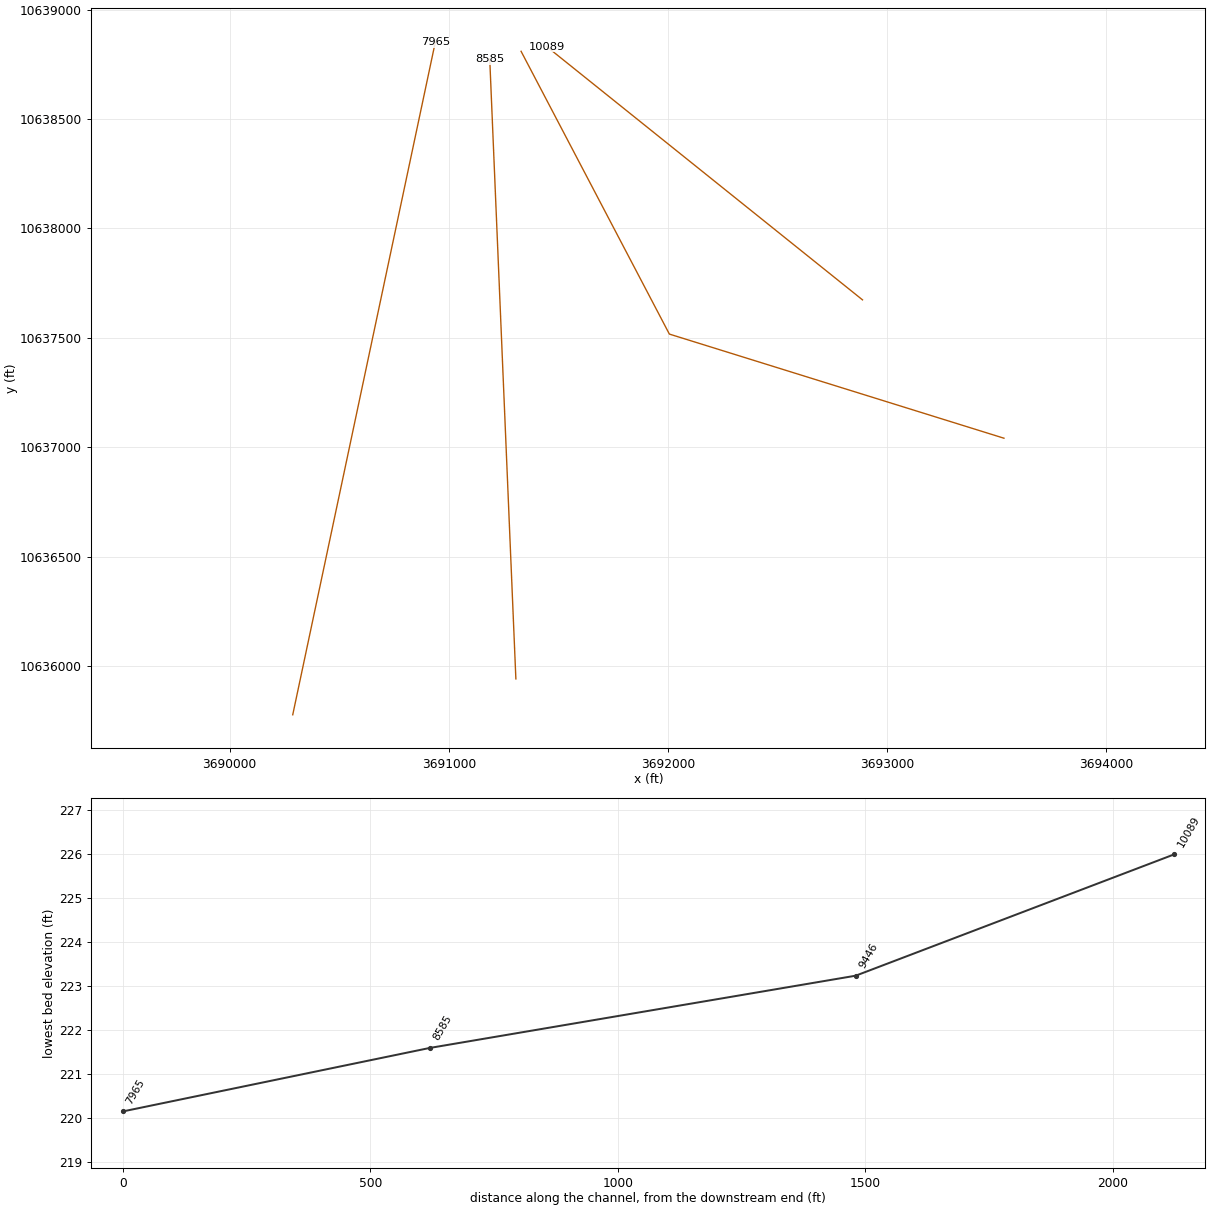
HEC-RAS study UNT 0487 IN LACR.prj: UNT 0487 IN LACR Base Level Engineering

--- UNT 0487 IN LACR.g01 (geometry) --- (continued)

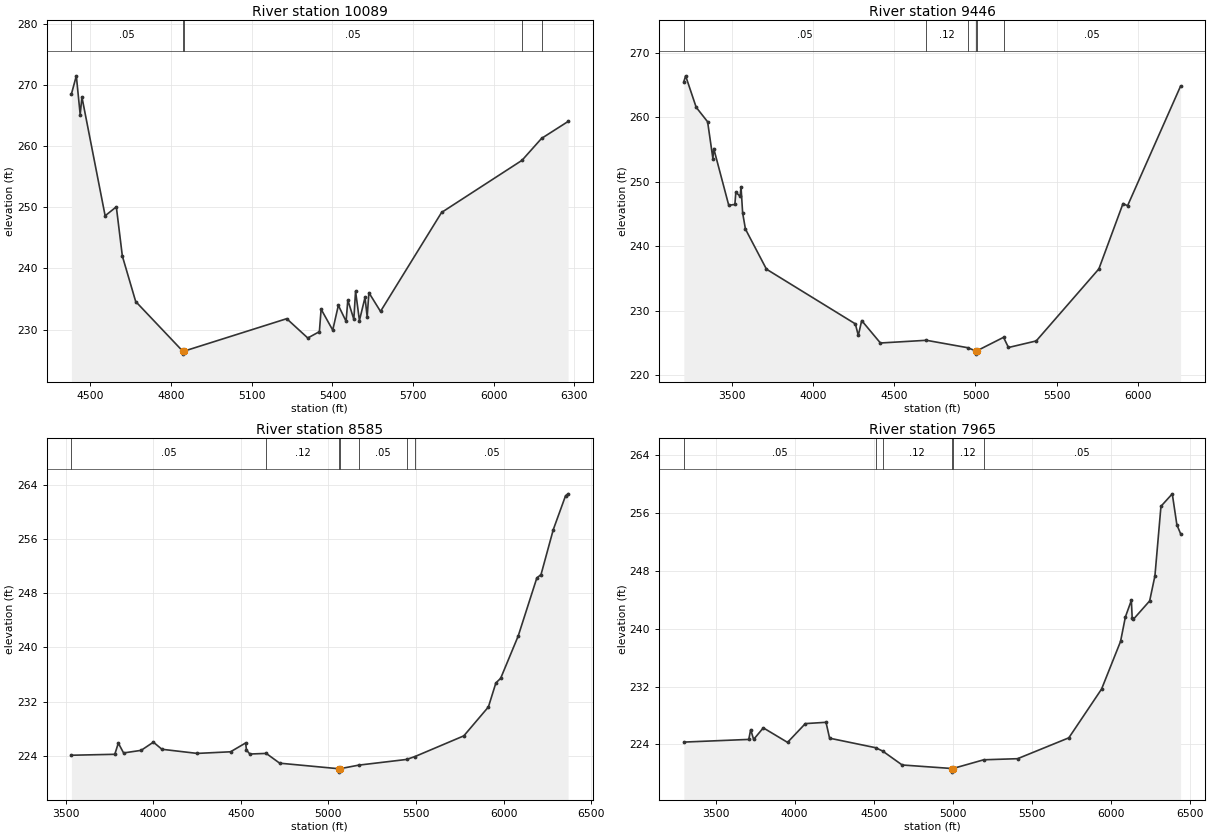
Type RM Length L Ch R = 1,10089,643,643,643
BEGIN DESCRIPTION:
Mapping XS b28180d0
END DESCRIPTION:
XS GIS Cut Line= 2
      3692889.32     10637673.96      3691448.36     10638830.20
#Sta/Elev= 30
  4428.9  268.52  4447.3  271.53  4461.7  265.18  4468.1  268.06  4554.5  248.62
  4596.1  250.09  4618.5  242.03  4668.1  234.59  4842.8  226.48  4845.5  225.98
  4848.8  226.48  5229.8  231.78  5308.2  228.62  5351.4  229.66  5357.8  233.33
  5401.0  229.91  5421.9  233.96  5450.7  231.35  5457.1  234.83  5479.5  231.68
  5485.9  236.29  5500.3  231.48  5521.1  235.26  5529.1  232.08  5535.5  236.04
  5578.7  232.97  5805.9  249.17  6105.0  257.70  6177.8  261.29  6276.4  264.06
#Mann=5,-1,0
  4428.9    0.05       0  4842.8    0.03       0  4848.8    0.05       0
  6105.0    0.08       0  6177.8    0.05       0
Bank Sta=4842.8,4848.8
Exp/Cntr=0.3,0.1

Type RM Length L Ch R = 1,9446,861,861,861
BEGIN DESCRIPTION:
Mapping XS d780939b
END DESCRIPTION:
XS GIS Cut Line= 3
      3693535.13     10637042.03      3692007.38     10637517.71
      3691330.28     10638809.41
#Sta/Elev= 30
  3204.5  265.57  3215.3  266.47  3280.4  261.58  3350.7  259.33  3383.2  253.62
  3388.4  255.17  3480.8  246.36  3518.6  246.48  3524.5  248.39  3551.1  247.74
  3556.3  249.24  3566.4  245.17  3583.6  242.66  3713.0  236.43  4260.4  227.93
  4278.6  226.13  4299.5  228.44  4414.7  224.96  4697.9  225.38  4951.8  224.23
  5001.7  223.73  5004.4  223.23  5007.7  223.73  5172.9  225.84  5203.2  224.26
  5374.1  225.28  5759.9  236.47  5908.6  246.63  5936.5  246.28  6263.0  264.87
#Mann=6,-1,0
  3204.5    0.05       0  4697.9    0.12       0  4951.8    0.07       0
  5001.7    0.07       0  5007.7    0.07       0  5172.9    0.05       0
Bank Sta=5001.7,5007.7
Exp/Cntr=0.3,0.1

Type RM Length L Ch R = 1,8585,620,620,620
BEGIN DESCRIPTION:
UNT 0487 IN LACR 2.0
END DESCRIPTION:
XS GIS Cut Line= 2
      3691306.51     10635942.56      3691187.15     10638774.54
#Sta/Elev= 30
  3533.5  224.08  3781.3  224.22  3801.4  225.87  3831.4  224.42  3931.5  224.80
  4001.5  226.01  4050.1  224.96  4251.8  224.35  4441.9  224.59  4527.8  225.89
  4532.8  224.84  4552.0  224.26  4645.4  224.35  4722.2  222.91  5059.5  222.09
  5062.2  221.59  5065.5  222.09  5173.0  222.62  5446.3  223.46  5494.4  223.89
  5773.1  226.94  5913.2  231.20  5955.9  234.74  5983.3  235.43  6083.4  241.67
  6189.7  250.23  6213.5  250.72  6283.6  257.36  6353.6  262.35  6368.0  262.63
#Mann=7,-1,0
  3533.5    0.05       0  4645.4    0.12       0  5059.5    0.07       0
  5065.5    0.12       0  5173.0    0.05       0  5446.3    0.16       0
  5494.4    0.05       0
Bank Sta=5059.5,5065.5
Exp/Cntr=0.3,0.1

Type RM Length L Ch R = 1,7965,0,0,0
BEGIN DESCRIPTION:
UNT 0487 IN LACR 1.0
END DESCRIPTION:
XS GIS Cut Line= 2
      3690287.68     10635778.69      3690938.72     10638851.58
#Sta/Elev= 30
  3299.4  224.31  3709.8  224.68  3722.0  226.03  3740.5  224.68  3801.8  226.28
  3955.0  224.27  4067.6  226.87  4198.3  227.05  4220.9  224.85  4512.2  223.53
  4556.3  223.07  4679.8  221.14  4994.8  220.65  4997.5  220.15  5000.8  220.65
  5195.8  221.86  5409.6  222.01  5733.8  224.90  5940.8  231.65  6060.9  238.25
  6091.5  241.64  6129.2  243.94  6134.4  241.54  6142.6  241.33  6244.9  243.86
  6278.3  247.33  6316.4  256.96  6388.0  258.69  6417.1  254.40  6440.5  253.17
#Mann=6,-1,0
  3299.4    0.05       0  4512.2    0.16       0  4556.3    0.12       0
  4994.8    0.07       0  5000.8    0.12       0  5195.8    0.05       0
Bank Sta=4994.8,5000.8
Exp/Cntr=0.3,0.1

Chan Stop Cuts=-1