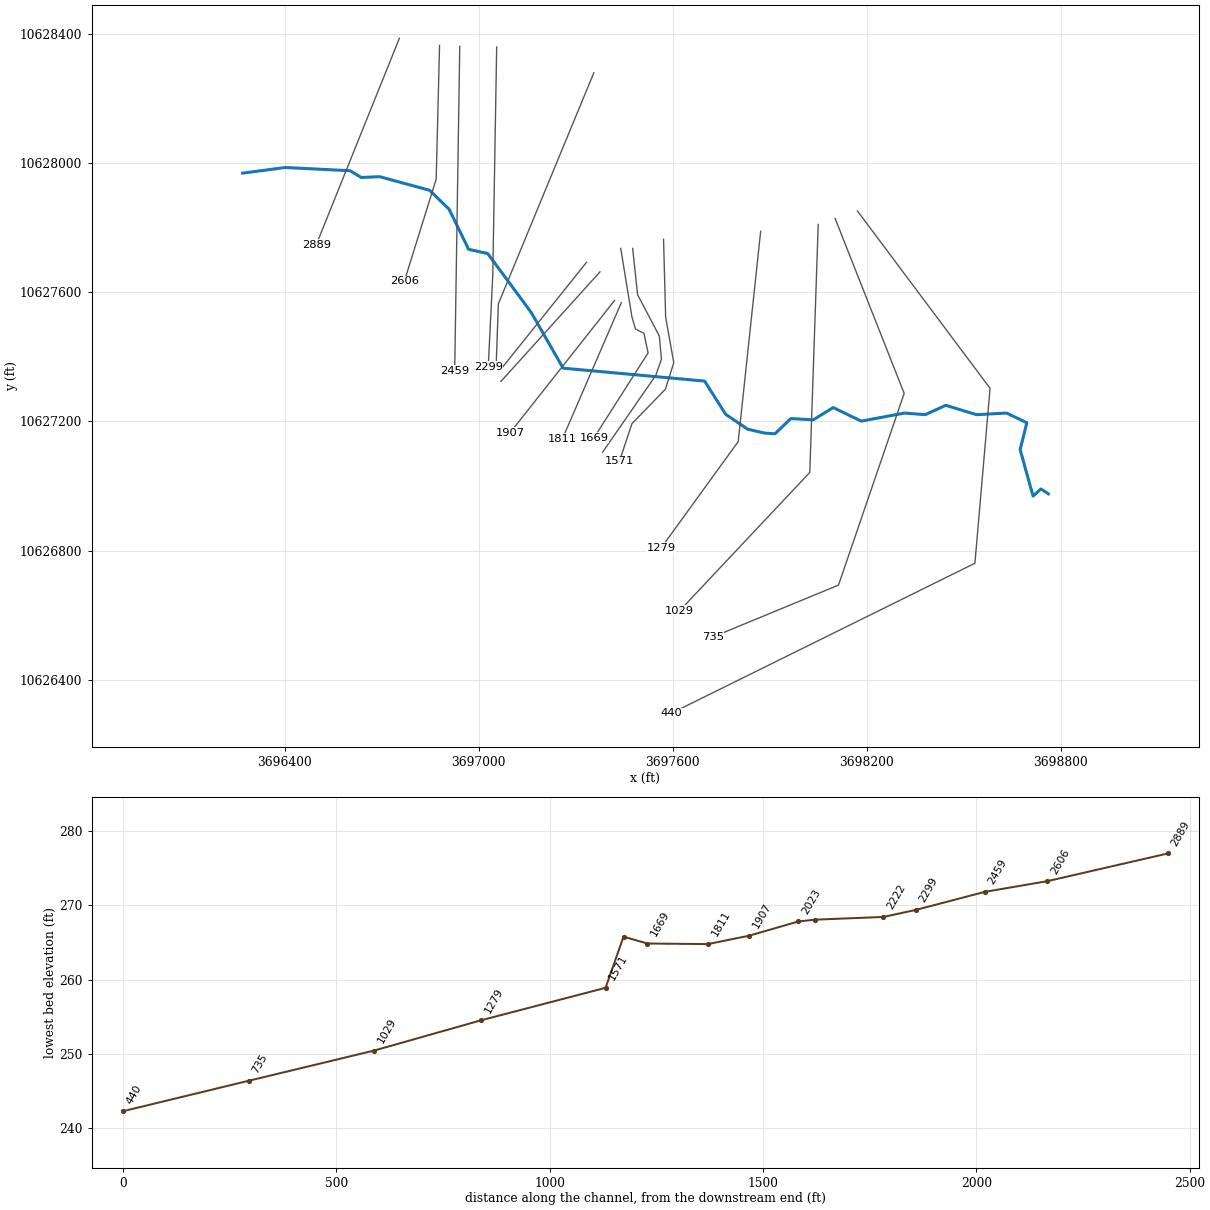
--- UNT 488 IN LACR.prj (project) ---

Proj Title=UNT 488 IN LACR Base Level Engineering
Current Plan=p01
Default Exp/Contr=0.3,0.1
English Units
Geom File=g01
Flow File=f01
Plan File=p01
Y Axis Title=Elevation
X Axis Title(PF)=Main Channel Distance
X Axis Title(XS)=Station
BEGIN DESCRIPTION:
UNT 488 IN LACR
END DESCRIPTION:
DSS Export Rating Curves= 0
DSS Export Rating Curve Sorted= 0
DSS Export Volume Flow Curves= 0
DXF OffsetX= 0
DXF OffsetY= 0
DXF ScaleX= 1
DXF ScaleY= 10

--- UNT 488 IN LACR.p01 (plan) ---

Plan Title=Multiple Run
Short Identifier=Multiple
Geom File=g01
Flow File=f01
Subcritical Flow
K Sum by GR= 0
Std Step Tol= 0.01
Critical Tol= 0.01
Num of Std Step Trials= 20
Max Error Tol= 0.3
Flow Tol Ratio= 0.001
Split Flow NTrial= 30
Split Flow Tol= 0.02
Split Flow Ratio= 0.02
Log Output Level= 0
Friction Slope Method= 1
Unsteady Friction Slope Method= 2
Unsteady Bridges Friction Slope Method= 1
Parabolic Critical Depth
Global Vel Dist=  1 , 1 , 1
Global Log Level= 0
CheckData=True
Encroach Param= -1, 0, 0, 0
BEGIN DESCRIPTION:
Multiple Run
END DESCRIPTION:

--- UNT 488 IN LACR.f01 (steady flow) ---

Flow Title=Multiple
Program Version=4.10
Number of Profiles= 7
Profile Names=10-year,25-year,50-year,1pct_min,100-year,1pct_plu,500-year
River Rch & RM=UNT 488 IN LACR,Reach-1         ,2889
      98     117     131     108     147     198     183
Boundary for River Rch & Prof#=UNT 488 IN LACR,Reach-1         , 1
Up Type= 0
Dn Type= 3
Dn Slope=0.014
Boundary for River Rch & Prof#=UNT 488 IN LACR,Reach-1         , 2
Up Type= 0
Dn Type= 3
Dn Slope=0.014
Boundary for River Rch & Prof#=UNT 488 IN LACR,Reach-1         , 3
Up Type= 0
Dn Type= 3
Dn Slope=0.014
Boundary for River Rch & Prof#=UNT 488 IN LACR,Reach-1         , 4
Up Type= 0
Dn Type= 3
Dn Slope=0.014
Boundary for River Rch & Prof#=UNT 488 IN LACR,Reach-1         , 5
Up Type= 0
Dn Type= 3
Dn Slope=0.014
Boundary for River Rch & Prof#=UNT 488 IN LACR,Reach-1         , 6
Up Type= 0
Dn Type= 3
Dn Slope=0.014
Boundary for River Rch & Prof#=UNT 488 IN LACR,Reach-1         , 7
Up Type= 0
Dn Type= 3
Dn Slope=0.014
DSS Import GetInterval= 0
DSS Import GetPeak= 0
DSS Import FillOption= 0

--- UNT 488 IN LACR.g01 (geometry) ---

Geom Title=Existing Conditions
Program Version=4.10

River Reach=UNT 488 IN LACR ,Reach-1
Reach XY= 30
      3696269.59       10627969.      3696401.54     10627986.36
      3696601.88     10627976.42      3696636.84      10627955.4
      3696693.26       10627958.      3696847.78      10627915.9
      3696908.25       10627857.       3696968.5       10627733.
       3697027.5       10627720.      3697161.75       10627538.
      3697260.75       10627365.      3697698.25       10627325.
       3697763.5       10627222.       3697831.5       10627176.
      3697883.75       10627164.        3697916.       10627162.
        3697965.       10627209.      3698034.25       10627205.
        3698096.       10627243.      3698182.75       10627201.
       3698316.5       10627226.       3698380.5       10627221.
      3698444.25       10627250.        3698539.       10627221.
      3698632.25       10627226.      3698694.75       10627196.
        3698674.       10627113.        3698714.       10626969.
      3698738.25       10626991.      3698761.25       10626976.

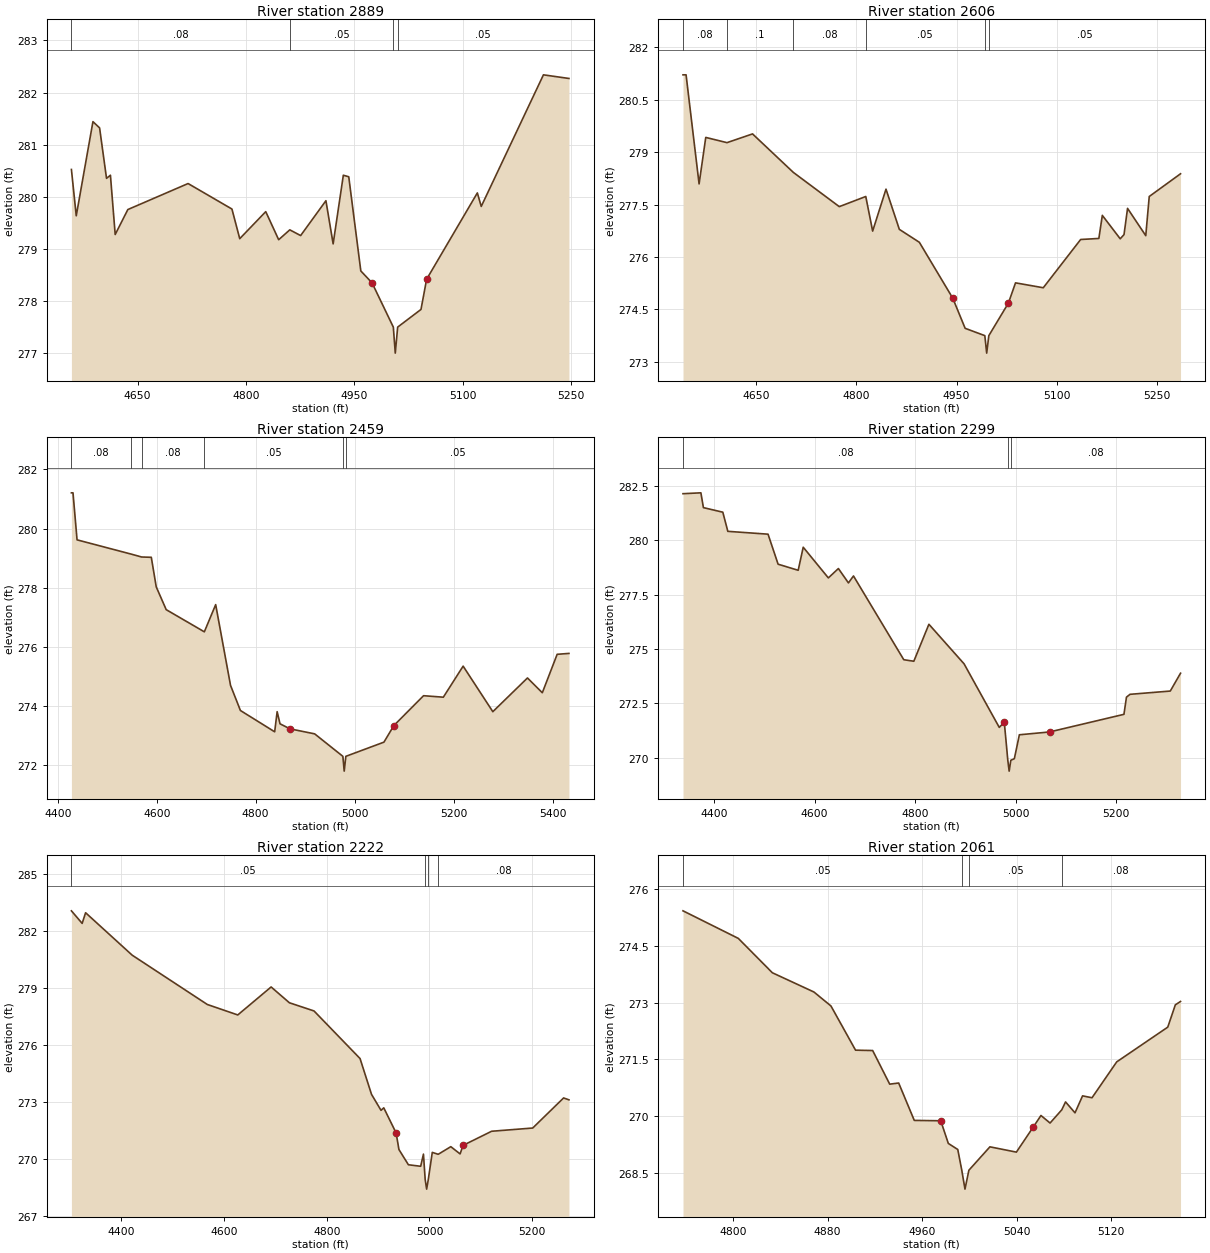
Type RM Length L Ch R = 1 ,2889    ,283,283,283
BEGIN DESCRIPTION:
UNT 488 IN LACR 6.0
END DESCRIPTION:
XS GIS Cut Line= 2
       3696754.3     10628386.37      3696497.33      10627747.4
#Sta/Elev= 30
  4558.3  280.52    4565  279.63  4588.1  281.44  4597.3  281.32  4606.9  280.35
  4612.3  280.41  4618.9  279.27  4636.4  279.75  4719.8  280.25  4780.5  279.76
  4791.3  279.19  4827.3  279.71  4845.2  279.17  4860.6  279.36  4875.6  279.25
  4910.6  279.92  4920.6  279.09  4934.7  280.41  4942.2  280.38  4958.9  278.57
  4974.5  278.34  5003.9  277.49  5006.6  276.99  5009.9  277.49  5042.2  277.83
    5050  278.41  5120.2  280.07  5125.6  279.81  5211.7  282.34    5247  282.27
#Mann= 4 ,-1 , 0
  4558.3     .08       0  4860.6     .05       0  5003.9     .03       0
  5009.9     .05       0
Bank Sta=4974.5,5050
XS Rating Curve= 0 ,0
Exp/Cntr=0.3,0.1

Type RM Length L Ch R = 1 ,2606    ,147,147,147
BEGIN DESCRIPTION:
Mapping XS dc93daed
END DESCRIPTION:
XS GIS Cut Line= 3
      3696878.56     10628364.31      3696868.14      10627950.2
       3696769.6     10627633.84
#Sta/Elev= 30
  4540.1  281.21  4544.7  281.21  4564.2  278.09  4574.2  279.42    4606  279.27
  4644.3  279.52  4705.4  278.42  4774.3  277.44    4814  277.73  4824.3  276.74
  4844.3  277.94  4864.3  276.79  4894.3  276.42  4944.4  274.82  4962.9  273.96
  4992.4  273.75  4995.2  273.25  4998.4  273.75  5027.7  274.68  5038.4  275.26
    5080  275.12    5136   276.5  5163.3  276.53  5168.5  277.19  5195.3  276.52
    5201  276.64  5206.3  277.39  5233.6  276.61  5238.8  277.73  5285.7  278.38
#Mann= 6 ,-1 , 0
  4540.1     .08       0    4606      .1       0  4705.4     .08       0
    4814     .05       0  4992.4     .03       0  4998.4     .05       0
Bank Sta=4944.4,5027.7
XS Rating Curve= 0 ,0
Exp/Cntr=0.3,0.1

Type RM Length L Ch R = 1 ,2459    ,160,160,160
BEGIN DESCRIPTION:
UNT 488 IN LACR 5.0
END DESCRIPTION:
XS GIS Cut Line= 2
      3696941.06     10628361.62      3696925.43     10627356.44
#Sta/Elev= 30
  4427.7  281.21  4430.9  281.21  4439.1  279.62    4548  279.14  4569.6  279.04
  4589.1  279.03  4599.1  278.03  4619.2  277.26  4696.3  276.51  4719.2  277.43
  4749.2   274.7  4769.2  273.85  4838.4  273.13  4843.4  273.81  4849.2   273.4
  4869.2  273.23  4919.2  273.06  4976.2   272.3  4978.9   271.8  4982.2   272.3
  5059.2  272.78  5079.2  273.34  5139.2  274.35  5179.2   274.3  5219.2  275.35
  5279.2  273.81  5349.2  274.95  5379.2  274.45  5409.2  275.75    5433  275.78
#Mann= 6 ,-1 , 0
  4427.7     .08       0    4548      .1       0  4569.6     .08       0
  4696.3     .05       0  4976.2     .03       0  4982.2     .05       0
Bank Sta=4869.2,5079.2
XS Rating Curve= 0 ,0
Exp/Cntr=0.3,0.1

Type RM Length L Ch R = 1 ,2299    ,77,77,77
BEGIN DESCRIPTION:
Mapping XS c15b76c5
END DESCRIPTION:
XS GIS Cut Line= 3
      3697055.24     10628359.38      3697043.09     10627651.03
       3697029.2     10627369.82
#Sta/Elev= 30
  4338.2  282.14  4373.8  282.18  4378.8   281.5  4417.4  281.29  4427.4  280.41
  4507.4  280.28  4527.4   278.9  4567.4  278.62  4577.4  279.68  4627.4  278.27
  4647.4   278.7  4667.4  278.04  4677.4  278.36  4777.5  274.51  4797.5  274.44
  4827.5  276.14  4897.5  274.32  4967.5   271.4  4977.5  271.64  4984.5  269.89
  4987.2  269.39  4990.5  269.89  4997.5  269.96  5007.5  271.06  5067.5  271.19
  5215.6     272  5220.6  272.79  5227.7  272.92  5307.8  273.07  5328.2  273.89
#Mann= 3 ,-1 , 0
  4338.2     .08       0  4984.5     .07       0  4990.5     .08       0
Bank Sta=4977.5,5067.5
XS Rating Curve= 0 ,0
Exp/Cntr=0.3,0.1

Type RM Length L Ch R = 1 ,2222    ,161,161,161
BEGIN DESCRIPTION:
Mapping XS 443f2461
END DESCRIPTION:
XS GIS Cut Line= 3
       3697355.6     10628279.53      3697060.45     10627564.23
      3697053.51     10627369.76
#Sta/Elev= 30
  4303.1  283.05    4324  282.39  4330.7  282.95  4421.4  280.72  4567.6  278.13
  4626.9  277.58  4691.8  279.05  4727.4  278.22  4775.3  277.79  4864.9  275.29
  4887.2  273.41  4905.7  272.57  4911.1   272.7  4935.1  271.38  4940.6  270.51
    4959  269.71  4982.9  269.63  4988.3  270.27  4991.7  268.93  4994.5  268.43
  4997.7  268.93  5005.5  270.36    5017  270.26  5041.6  270.66  5059.6  270.28
  5065.5  270.73    5121  271.47    5201  271.64  5261.1  273.22  5271.5  273.12
#Mann= 4 ,-1 , 0
  4303.1     .05       0  4991.7     .04       0  4997.7     .05       0
    5017     .08       0
Bank Sta=4935.1,5065.5
XS Rating Curve= 0 ,0
Exp/Cntr=0.3,0.1

Type RM Length L Ch R = 1 ,2061    ,38,38,38
BEGIN DESCRIPTION:
Mapping XS 188850aa
END DESCRIPTION:
XS GIS Cut Line= 2
      3697333.04     10627692.73      3697070.05     10627363.98
#Sta/Elev= 30
  4757.6  275.43  4804.4   274.7  4833.2  273.79  4868.4  273.28  4882.8  272.91
  4903.6  271.74  4918.1  271.73  4932.5  270.84  4940.1  270.87  4953.3  269.88
  4975.7  269.87  4982.1  269.27  4990.1  269.11  4993.5  268.56  4996.2  268.06
  4999.5  268.56  5017.3  269.18  5039.7  269.04  5054.1  269.71  5060.5  270.01
  5068.2  269.81  5078.1  270.16  5081.3  270.37  5089.3  270.08  5095.7  270.53
  5103.7  270.48  5124.6  271.43  5167.8  272.35  5174.2  272.94  5178.6  273.03
#Mann= 4 ,-1 , 0
  4757.6     .05       0  4993.5     .04       0  4999.5     .05       0
  5078.1     .08       0
Bank Sta=4975.7,5054.1
XS Rating Curve= 0 ,0
Exp/Cntr=0.3,0.1

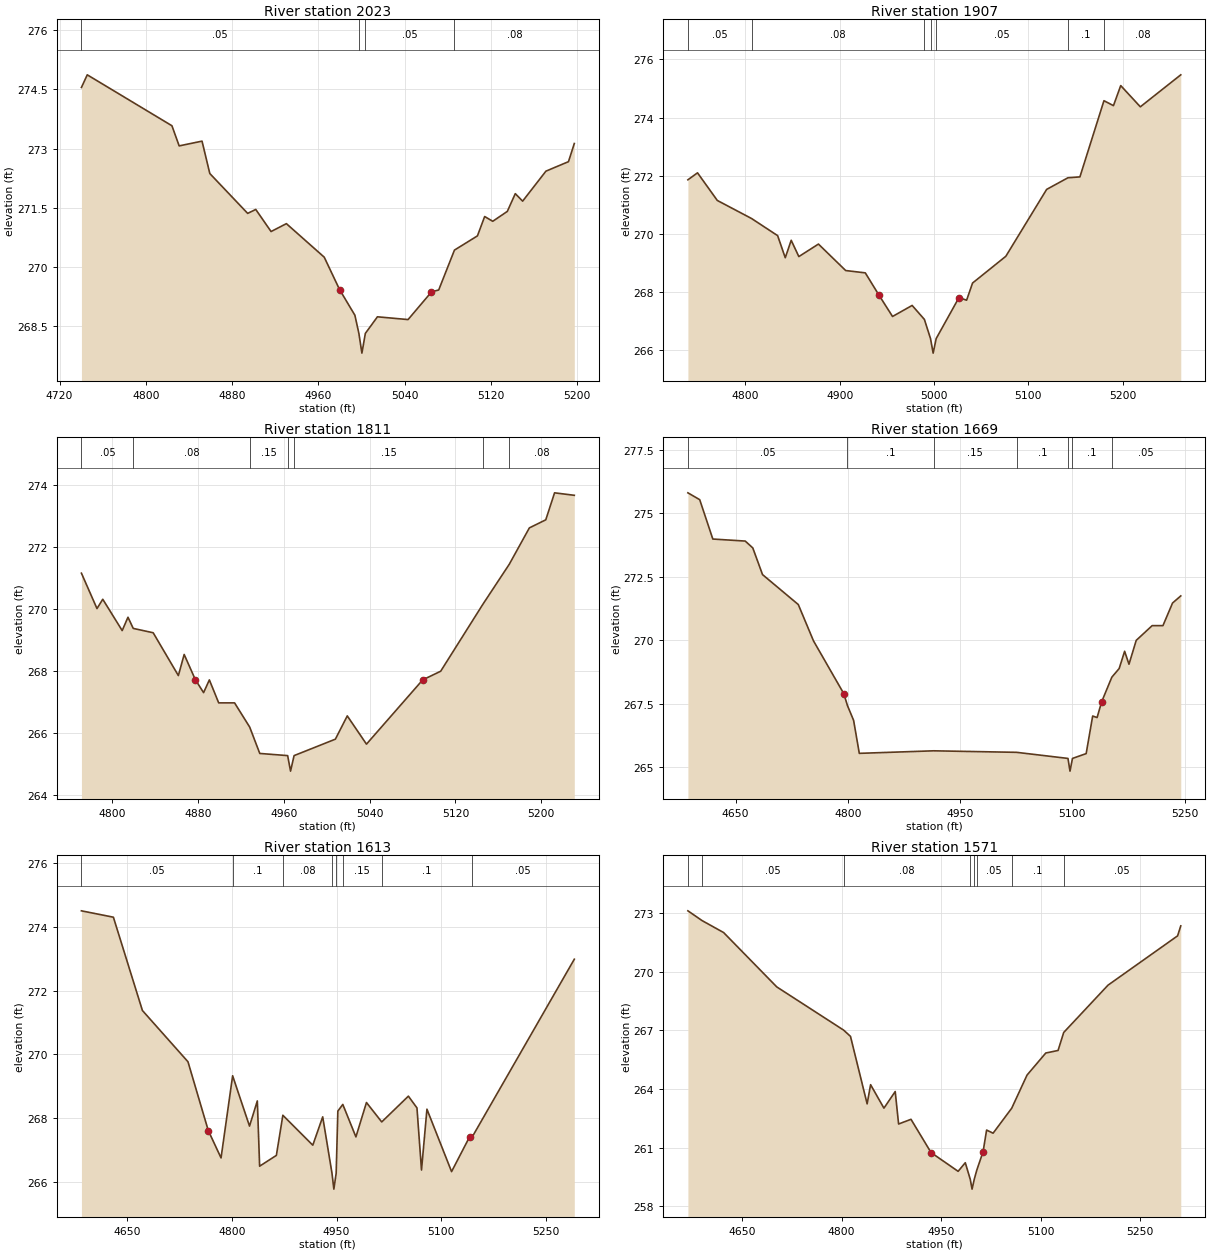
Type RM Length L Ch R = 1 ,2023    ,116,116,116
BEGIN DESCRIPTION:
Mapping XS 04f20cca
END DESCRIPTION:
XS GIS Cut Line= 2
      3697374.66     10627663.16      3697068.44     10627324.07
#Sta/Elev= 30
  4740.3  274.55  4745.7  274.87  4824.2  273.58  4830.9  273.07  4852.1  273.19
  4859.3  272.37  4894.4  271.36  4901.9  271.46  4916.1   270.9  4930.3   271.1
  4965.4  270.25  4979.6  269.43  4993.8  268.78  4997.5  268.32  5000.3  267.82
  5003.5  268.32  5014.7  268.74  5043.1  268.67  5064.8  269.37  5071.5  269.42
  5086.1  270.43  5107.4  270.79  5114.1  271.28  5121.6  271.16  5135.1  271.41
  5142.5  271.86  5149.3  271.67  5170.9  272.43  5191.8  272.67  5197.2  273.13
#Mann= 4 ,-1 , 0
  4740.3     .05       0  4997.5     .04       0  5003.5     .05       0
  5086.1     .08       0
Bank Sta=4979.6,5064.8
XS Rating Curve= 0 ,0
Exp/Cntr=0.3,0.1

Type RM Length L Ch R = 1 ,1907    ,96,96,96
BEGIN DESCRIPTION:
UNT 488 IN LACR 4.0
END DESCRIPTION:
XS GIS Cut Line= 2
      3697419.83     10627574.66      3697095.93     10627164.15
#Sta/Elev= 30
  4738.9  271.86  4749.1   272.1  4770.1  271.15  4806.4  270.53  4834.1  269.94
  4842.2  269.18  4848.5  269.78  4856.6  269.22  4877.4  269.65  4906.3  268.74
  4927.1  268.66  4941.5   267.9    4956  267.16  4976.8  267.54  4989.8  267.06
  4996.3   266.4  4999.1   265.9  5002.3   266.4  5026.5  267.81  5034.6  267.72
  5040.9  268.31  5076.2  269.23  5119.5  271.53  5142.1  271.93  5154.8  271.96
  5180.3  274.58  5190.4  274.41  5198.1   275.1  5218.9  274.37  5261.8  275.47
#Mann= 7 ,-1 , 0
  4738.9     .05       0  4806.4     .08       0  4989.8     .05       0
  4996.3     .04       0  5002.3     .05       0  5142.1      .1       0
  5180.3     .08       0
Bank Sta=4941.5,5026.5
XS Rating Curve= 0 ,0
Exp/Cntr=0.3,0.1

Type RM Length L Ch R = 1 ,1811    ,142,142,142
BEGIN DESCRIPTION:
Mapping XS fbafac65
END DESCRIPTION:
XS GIS Cut Line= 2
      3697440.66     10627567.71      3697258.36     10627145.81
#Sta/Elev= 30
  4771.2  271.15  4785.7  270.01  4791.1  270.31  4809.2   269.3  4814.6  269.73
  4819.5  269.37  4838.1  269.23  4861.6  267.85    4867  268.53  4877.4  267.72
  4885.1   267.3  4890.5  267.71  4899.2  266.97    4914  266.97  4928.1  266.19
  4937.5  265.34  4963.5  265.27  4966.2  264.77  4969.5  265.27    5008   265.8
  5019.1  266.55    5037  265.64  5089.4  267.71  5106.2  267.99  5145.4  270.14
  5170.2  271.44  5188.9  272.61  5204.2  272.87  5212.4  273.74  5230.8  273.66
#Mann= 7 ,-1 , 0
  4771.2     .05       0  4819.5     .08       0  4928.1     .15       0
  4963.5     .07       0  4969.5     .15       0  5145.4     .05       0
  5170.2     .08       0
Bank Sta=4877.4,5089.4
XS Rating Curve= 0 ,0
Exp/Cntr=0.3,0.1

Type RM Length L Ch R = 1 ,1669    ,56,56,56
BEGIN DESCRIPTION:
Mapping XS 9056f8a2
END DESCRIPTION:
XS GIS Cut Line= 6
      3697438.89     10627735.79      3697473.61     10627523.12
      3697484.46     10627486.23       3697510.5     10627473.21
      3697523.52     10627412.44      3697356.41     10627149.84
#Sta/Elev= 30
  4586.3  275.81  4602.1  275.54  4619.6  273.99  4662.9  273.91    4673  273.64
    4686  272.59  4733.8  271.41  4754.1  269.98  4794.6   267.9  4799.5  267.43
  4807.7  266.85  4815.3  265.55  4914.6  265.65  5025.5  265.59  5094.1  265.35
  5096.8  264.85  5100.1  265.35  5118.4  265.54  5127.1  267.02    5133  266.96
  5139.1  267.58  5152.7  268.55  5162.5  268.89  5169.8  269.57  5175.6  269.06
  5185.3     270  5206.6  270.58    5221  270.58  5233.8  271.47  5244.8  271.75
#Mann= 7 ,-1 , 0
  4586.3     .05       0  4799.5      .1       0  4914.6     .15       0
  5025.5      .1       0  5094.1     .07       0  5100.1      .1       0
  5152.7     .05       0
Bank Sta=4794.6,5139.1
XS Rating Curve= 0 ,0
Exp/Cntr=0.3,0.1

Type RM Length L Ch R = 1 ,1613    ,42,42,42
BEGIN DESCRIPTION:
Mapping XS c787c282
END DESCRIPTION:
XS GIS Cut Line= 6
      3697475.78     10627735.77      3697490.97     10627592.56
      3697558.25     10627464.52      3697564.76     10627392.91
      3697547.39       10627343.      3697382.76     10627104.77
#Sta/Elev= 30
  4584.4  274.51  4630.2  274.31  4671.8  271.38  4737.1  269.77  4766.2  267.61
  4784.5  266.75  4801.1  269.33  4825.3  267.75  4836.5  268.54  4839.8  266.49
  4863.8  266.83  4873.1  268.09    4916  267.15  4930.2  268.04  4943.5  266.27
  4946.2  265.77  4949.5  266.27  4951.9  268.22    4959  268.43  4977.8  267.41
  4992.9  268.49  5014.8  267.88    5053  268.69  5065.3  268.32  5071.8  266.37
  5079.6  268.28  5114.9  266.32  5140.7  267.41  5144.5  267.41  5290.8  272.99
#Mann= 8 ,-1 , 0
  4584.4     .05       0  4801.1      .1       0  4873.1     .08       0
  4943.5     .07       0  4949.5     .08       0    4959     .15       0
  5014.8      .1       0  5144.5     .05       0
Bank Sta=4766.2,5140.7
XS Rating Curve= 0 ,0
Exp/Cntr=0.3,0.1

Type RM Length L Ch R = 1 ,1571    ,292,292,292
BEGIN DESCRIPTION:
UNT 488 IN LACR 3.0
END DESCRIPTION:
XS GIS Cut Line= 6
      3697571.27     10627763.99      3697577.78     10627523.12
      3697602.87     10627381.91      3697577.02     10627299.95
      3697473.61     10627193.26      3697434.59     10627076.19
#Sta/Elev= 30
  4568.5  273.11  4589.9  272.61  4622.3     272  4702.4  269.22  4803.2  267.01
  4813.5  266.69  4838.6  263.24  4843.8  264.22  4863.9  263.02  4880.9  263.87
    4886  262.21  4904.7  262.45  4934.9  260.75  4975.7  259.79  4986.5  260.23
    4994  259.38  4996.7  258.88    5000  259.38  5003.8  259.85  5013.3  260.79
  5018.6   261.9  5028.4  261.74  5056.5  263.02  5079.5  264.71  5107.8  265.84
  5126.3  265.97  5134.8  266.89  5201.6  269.31  5306.4  271.83  5311.2  272.34
#Mann= 8 ,-1 , 0
  4568.5     .08       0  4589.9     .05       0  4803.2     .08       0
    4994     .07       0    5000     .08       0  5003.8     .05       0
  5056.5      .1       0  5134.8     .05       0
Bank Sta=4934.9,5013.3
XS Rating Curve= 0 ,0
Exp/Cntr=0.3,0.1

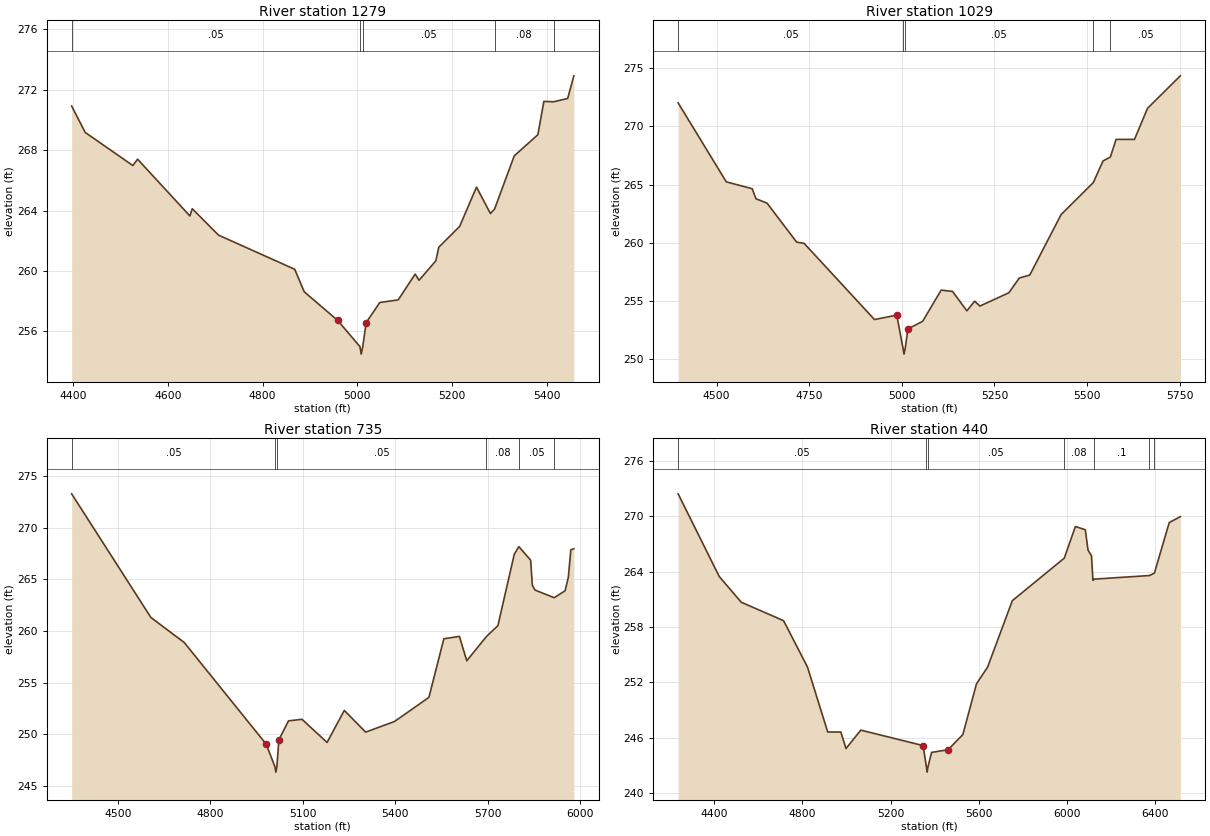
Type RM Length L Ch R = 1 ,1279    ,250,250,250
BEGIN DESCRIPTION:
Mapping XS 94794eb6
END DESCRIPTION:
XS GIS Cut Line= 3
      3697871.61     10627788.74      3697802.17      10627137.7
      3697564.04     10626808.65
#Sta/Elev= 30
  4396.6  270.93  4425.3  269.18  4525.9  266.99  4535.9  267.41  4646.4  263.65
  4651.4  264.13  4706.9  262.38  4867.8  260.12  4887.9  258.63  4958.3  256.74
  5005.6     255  5008.3   254.5  5011.6     255  5018.7  256.58  5047.6  257.92
  5086.4  258.09  5122.3   259.8  5130.5  259.39    5166  260.68  5172.2  261.58
  5216.3  262.96  5251.9  265.56  5281.3  263.81  5290.1  264.11  5331.6  267.63
  5381.5  269.03  5394.2  271.24  5414.6  271.21  5444.5  271.43  5457.5  272.93
#Mann= 5 ,-1 , 0
  4396.6     .05       0  5005.6     .03       0  5011.6     .05       0
  5290.1     .08       0  5414.6     .05       0
Bank Sta=4958.3,5018.7
XS Rating Curve= 0 ,0
Exp/Cntr=0.3,0.1

Type RM Length L Ch R = 1 ,1029    ,294,294,294
BEGIN DESCRIPTION:
UNT 488 IN LACR 2.0
END DESCRIPTION:
XS GIS Cut Line= 3
      3698049.61     10627810.22      3698023.52     10627042.22
       3697621.1     10626613.84
#Sta/Elev= 30
  4395.9  272.02    4526  265.23    4596  264.64  4606.1  263.78  4636.1   263.4
  4716.1  260.05  4736.1  259.95  4926.2   253.4  4986.3  253.78  5003.3  250.93
    5006  250.43  5009.3  250.93  5016.3  252.59  5056.3  253.25  5106.3  255.93
  5136.9  255.82  5175.7  254.15  5196.7  254.98  5210.9  254.56    5289   255.7
  5317.3  256.97  5345.5  257.22  5430.2  262.42  5517.2  265.17  5543.5  267.03
  5563.1  267.36  5578.7  268.88  5628.4  268.88  5663.6  271.55  5752.1  274.34
#Mann= 5 ,-1 , 0
  4395.9     .05       0  5003.3     .03       0  5009.3     .05       0
  5517.2     .08       0  5563.1     .05       0
Bank Sta=4986.3,5016.3
XS Rating Curve= 0 ,0
Exp/Cntr=0.3,0.1

Type RM Length L Ch R = 1 ,735     ,295,295,295
BEGIN DESCRIPTION:
Mapping XS 2442bbc5
END DESCRIPTION:
XS GIS Cut Line= 4
      3698101.87     10627828.65      3698315.41     10627287.01
      3698112.28     10626693.26      3697723.16     10626532.42
#Sta/Elev= 30
  4349.2  273.28  4606.5  261.32  4714.8   258.9  4980.9  249.07  5009.6  246.86
  5012.4  246.36  5015.6  246.86  5022.2  249.49  5053.5  251.32  5097.2  251.47
  5178.7  249.23  5234.6  252.33  5303.9  250.23  5397.8  251.26  5509.4  253.59
  5557.9  259.26  5608.4  259.49  5632.3  257.13  5696.2  259.48  5733.4  260.53
  5786.6  267.44  5801.6  268.17  5839.8  266.86  5845.2  264.44    5854  263.97
  5916.5  263.23  5951.7  263.91  5962.2  265.21  5970.2  267.86    5980  267.97
#Mann= 6 ,-1 , 0
  4349.2     .05       0  5009.6     .03       0  5015.6     .05       0
  5696.2     .08       0  5801.6     .05       0  5916.5     .08       0
Bank Sta=4980.9,5022.2
XS Rating Curve= 0 ,0
Exp/Cntr=0.3,0.1

Type RM Length L Ch R = 1 ,440     ,0,0,0
BEGIN DESCRIPTION:
UNT 488 IN LACR 1.0
END DESCRIPTION:
XS GIS Cut Line= 4
      3698170.95      10627851.6      3698581.03     10627302.63
      3698534.16     10626760.97      3697594.61     10626296.07
#Sta/Elev= 30
  4236.4  272.46  4422.7  263.49  4522.8  260.69  4714.6  258.69    4823  253.66
  4914.7  246.61  4974.3   246.6  4997.7  244.81  5064.6  246.81  5347.4  245.13
  5362.7  242.75  5365.5  242.25  5368.7  242.75  5385.8  244.39  5460.6  244.68
  5527.6  246.33  5589.3  251.83  5639.8  253.65  5751.9  260.86  5987.5  265.48
  6037.9  268.91  6082.8  268.56  6095.2  266.35  6110.8  265.74  6117.5  263.07
  6122.5   263.2  6373.6  263.59  6396.1  263.85  6463.4  269.34  6513.6  269.98
#Mann= 7 ,-1 , 0
  4236.4     .05       0  5362.7     .03       0  5368.7     .05       0
  5987.5     .08       0  6122.5      .1       0  6373.6     .08       0
  6396.1     .05       0
Bank Sta=5347.4,5460.6
XS Rating Curve= 0 ,0
Exp/Cntr=0.3,0.1

Chan Stop Cuts=-1
Use User Specified Reach Order=0
Composite Channel Slope=5