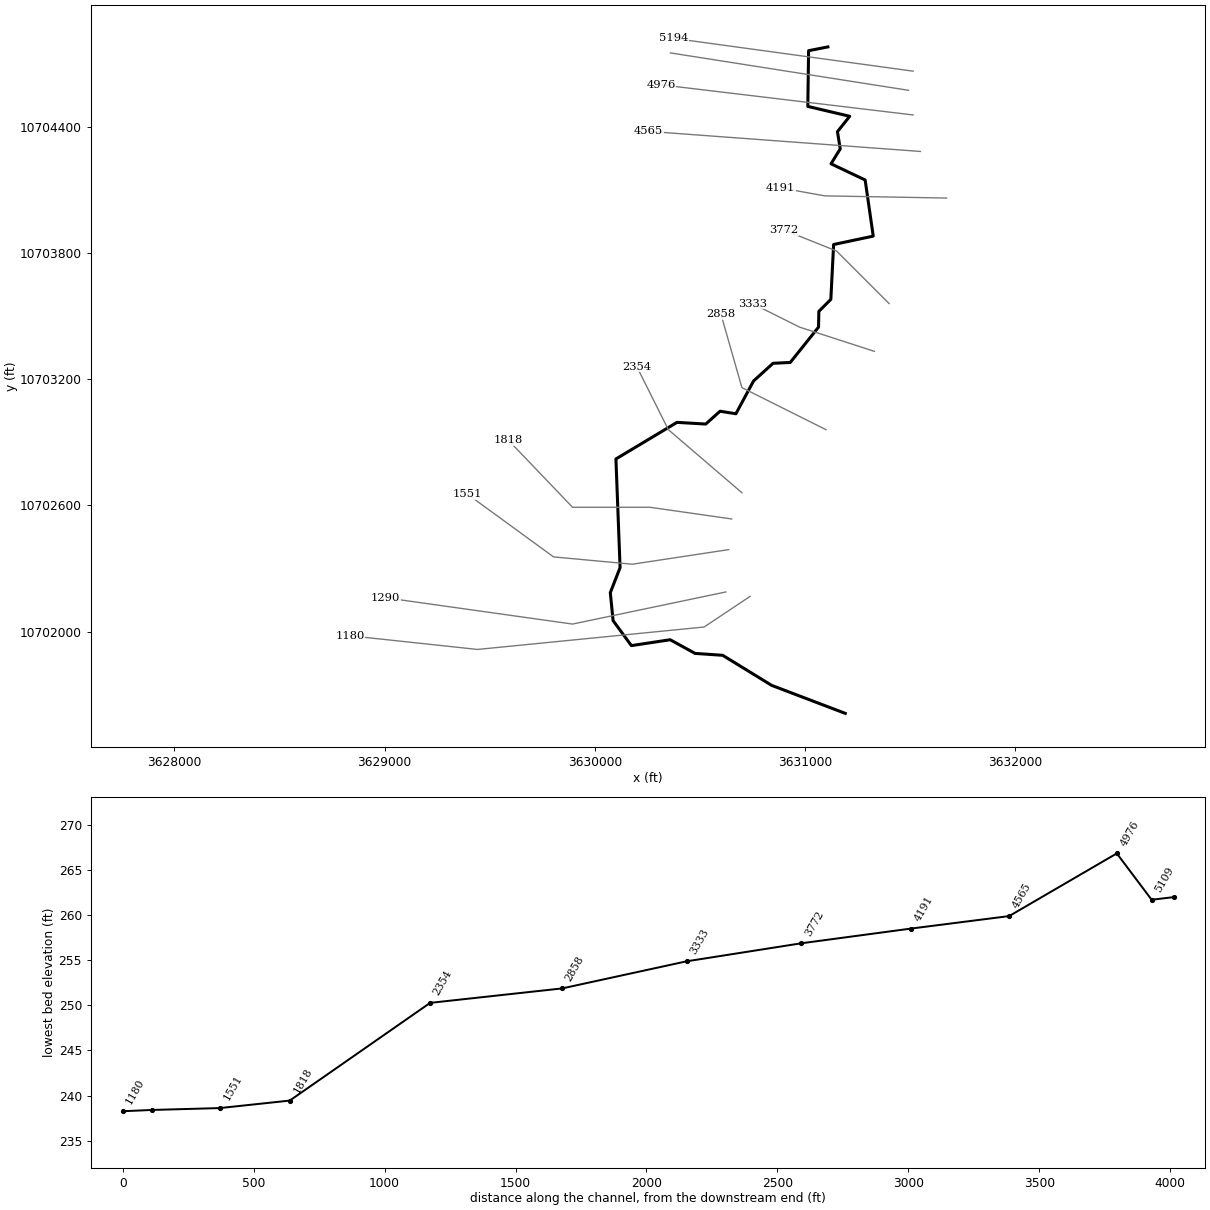
--- UNT 489 IN LACR.prj (project) ---

Proj Title=UNT 489 IN LACR Base Level Engineering
Current Plan=p01
Default Exp/Contr=0.3,0.1
English Units
Geom File=g01
Flow File=f01
Plan File=p01
BEGIN DESCRIPTION:
UNT 489 IN LACR
END DESCRIPTION:

--- UNT 489 IN LACR.p01 (plan) ---

Plan Title=Multiple Run
Short Identifier=Multiple
Geom File=g01
Flow File=f01
Subcritical Flow
K Sum by GR= 0
Std Step Tol= 0.01
Critical Tol= 0.01
Num of Std Step Trials= 20
Max Error Tol= 0.3
Flow Tol Ratio= 0.001
Split Flow NTrial= 30
Split Flow Tol= 0.02
Split Flow Ratio= 0.02
Log Output Level= 0
Friction Slope Method= 1
Unsteady Friction Slope Method= 2
Unsteady Bridges Friction Slope Method= 1
Parabolic Critical Depth
Global Vel Dist=  1 , 1 , 1
Global Log Level= 0
CheckData=True
Encroach Param= -1, 0, 0, 0
BEGIN DESCRIPTION:
Multiple Run
END DESCRIPTION:

--- UNT 489 IN LACR.f01 (steady flow) ---

Flow Title=Multiple
Number of Profiles=7
Profile Names=10-year,25-year,50-year,1pct_min,100-year,1pct_plu,500-year
River Rch & RM= UNT 489 IN LACR,Reach-1,5194
     748     995    1191    1041    1407    1903    1956
River Rch & RM= UNT 489 IN LACR,Reach-1,3333
    1073    1459    1771    1568    2120    2867    3028
Boundary for River Rch & Prof#=UNT 489 IN LACR,Reach-1,1
Up Type=0
Dn Type=3
Dn Slope=0.005
Boundary for River Rch & Prof#=UNT 489 IN LACR,Reach-1,2
Up Type=0
Dn Type=3
Dn Slope=0.005
Boundary for River Rch & Prof#=UNT 489 IN LACR,Reach-1,3
Up Type=0
Dn Type=3
Dn Slope=0.005
Boundary for River Rch & Prof#=UNT 489 IN LACR,Reach-1,4
Up Type=0
Dn Type=3
Dn Slope=0.005
Boundary for River Rch & Prof#=UNT 489 IN LACR,Reach-1,5
Up Type=0
Dn Type=3
Dn Slope=0.005
Boundary for River Rch & Prof#=UNT 489 IN LACR,Reach-1,6
Up Type=0
Dn Type=3
Dn Slope=0.005
Boundary for River Rch & Prof#=UNT 489 IN LACR,Reach-1,7
Up Type=0
Dn Type=3
Dn Slope=0.005

--- UNT 489 IN LACR.g01 (geometry) ---

Geom Title=Existing Conditions

River Reach=UNT 489 IN LACR,Reach-1
Reach XY= 30
      3631108.50     10704781.00      3631016.75     10704763.00
      3631013.00     10704498.00      3631212.25     10704451.00
      3631154.00     10704378.00      3631167.25     10704296.00
      3631123.50     10704225.00      3631285.75     10704148.00
      3631324.25     10703881.00      3631135.75     10703841.00
      3631122.50     10703580.00      3631065.50     10703523.00
      3631064.00     10703448.00      3630929.50     10703280.00
      3630847.75     10703276.00      3630755.00     10703192.00
      3630671.00     10703036.00      3630595.50     10703048.00
      3630527.50     10702987.00      3630390.75     10702995.00
      3630100.25     10702821.00      3630120.00     10702304.00
      3630073.50     10702185.00      3630086.75     10702052.00
      3630173.75     10701933.00      3630358.25     10701961.00
      3630476.75     10701896.00      3630608.00     10701887.00
      3630841.00     10701744.00      3631191.14     10701610.73

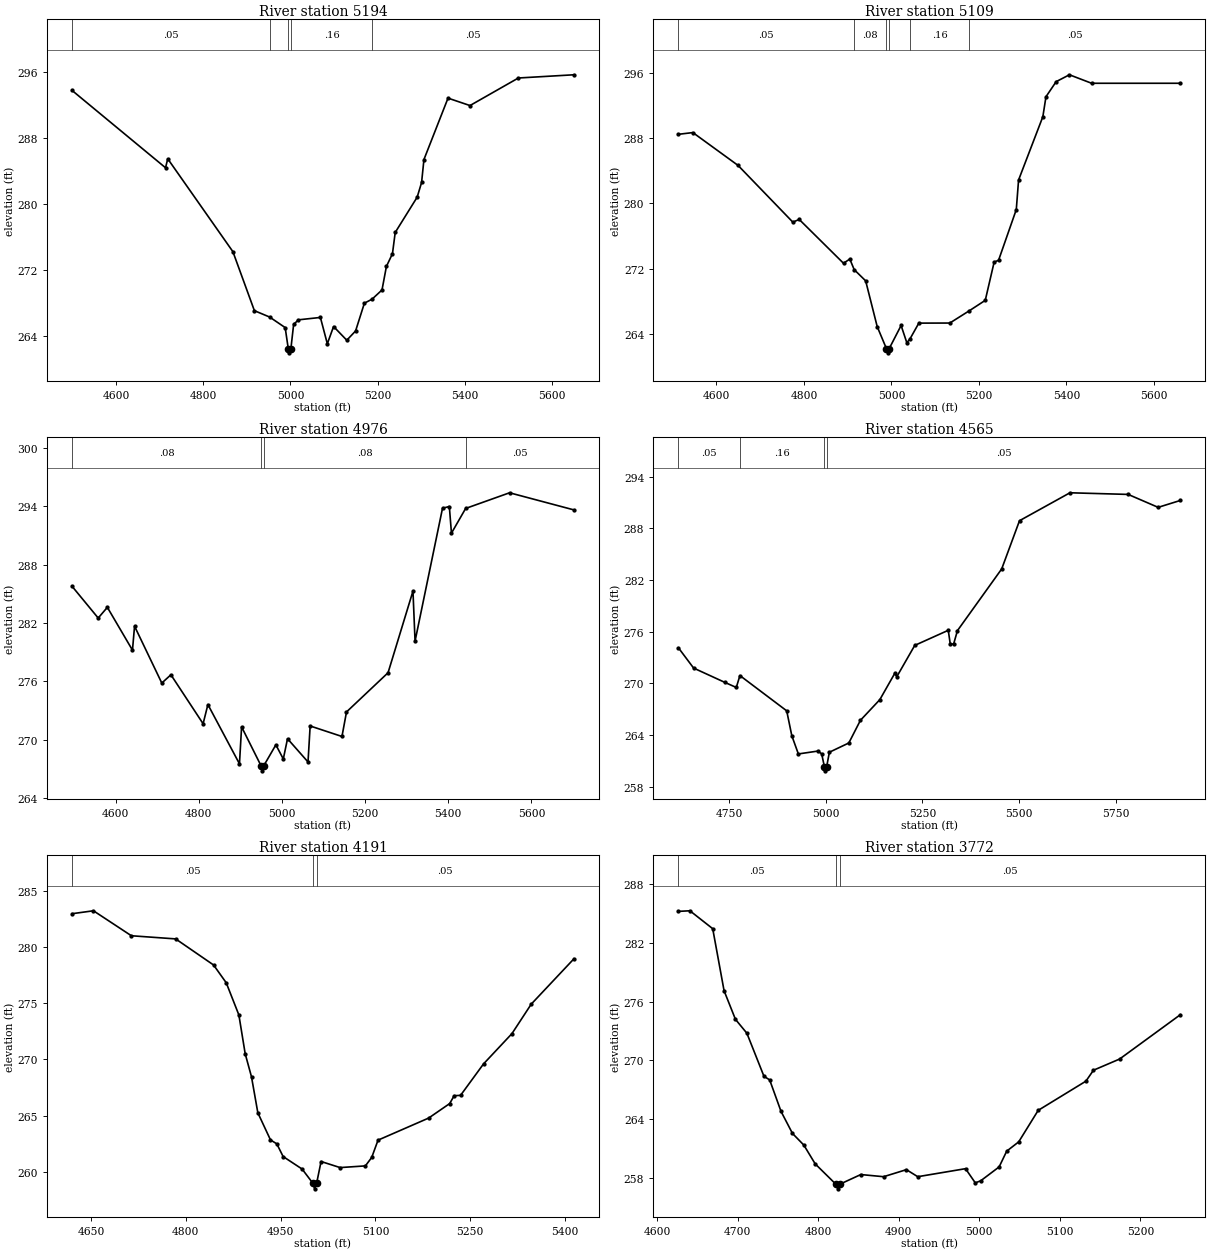
Type RM Length L Ch R = 1,5194,85,85,85
BEGIN DESCRIPTION:
UNT 489 IN LACR 10.0
END DESCRIPTION:
XS GIS Cut Line= 2
      3631513.91     10704665.69      3630373.45     10704821.80
#Sta/Elev= 30
  4499.2  293.77  4713.6  284.40  4718.6  285.49  4868.1  274.23  4917.4  267.08
  4952.3  266.31  4988.0  265.03  4995.1  262.47  4997.9  261.97  5001.1  262.47
  5007.4  265.41  5018.3  265.97  5068.8  266.26  5084.7  263.07  5099.0  265.16
  5129.3  263.50  5149.5  264.62  5169.7  267.99  5187.2  268.47  5210.1  269.59
  5220.2  272.44  5234.1  273.99  5240.4  276.56  5290.8  280.84  5300.9  282.62
  5306.3  285.40  5361.5  292.84  5411.9  291.94  5522.9  295.28  5650.3  295.67
#Mann=5,-1,0
  4499.2    0.05       0  4952.3    0.16       0  4995.1    0.07       0
  5001.1    0.16       0  5187.2    0.05       0
Bank Sta=4995.1,5001.1
Exp/Cntr=0.3,0.1

Type RM Length L Ch R = 1,5109,133,133,133
BEGIN DESCRIPTION:
Mapping XS b4773510
END DESCRIPTION:
XS GIS Cut Line= 2
      3631492.12     10704574.56      3630359.32     10704752.51
#Sta/Elev= 30
  4513.4  288.45  4546.3  288.66  4649.5  284.64  4774.7  277.69  4789.3  278.02
  4890.5  272.65  4904.9  273.17  4914.9  271.87  4941.1  270.50  4967.5  264.89
  4988.7  262.18  4991.5  261.68  4994.7  262.18  5022.1  265.03  5035.1  262.93
  5042.0  263.35  5062.6  265.32  5133.4  265.33  5178.1  266.84  5214.4  268.11
  5234.7  272.80  5244.8  273.02  5285.3  279.23  5290.5  282.85  5346.0  290.61
  5353.1  293.05  5376.4  294.90  5406.7  295.74  5457.4  294.70  5660.1  294.70
#Mann=6,-1,0
  4513.4    0.05       0  4914.9    0.08       0  4988.7    0.07       0
  4994.7    0.08       0  5042.0    0.16       0  5178.1    0.05       0
Bank Sta=4988.7,4994.7
Exp/Cntr=0.3,0.1

Type RM Length L Ch R = 1,4976,411,411,411
BEGIN DESCRIPTION:
Mapping XS 89e33a63
END DESCRIPTION:
XS GIS Cut Line= 2
      3631513.83     10704457.37      3630315.96     10704600.59
#Sta/Elev= 30
  4495.6  285.77  4558.4  282.51  4580.4  283.61  4640.8  279.21  4645.8  281.67
  4711.3  275.83  4733.2  276.68  4810.6  271.65  4822.1  273.62  4898.0  267.53
  4903.1  271.33  4950.1  267.31  4952.8  266.81  4956.1  267.31  4985.5  269.48
  5003.4  268.03  5013.5  270.11  5062.8  267.72  5067.9  271.42  5144.4  270.34
  5155.3  272.86  5255.2  276.89  5315.1  285.28  5320.1  280.14  5386.1  293.79
  5402.5  293.97  5407.6  291.23  5441.7  293.77  5547.3  295.38  5702.0  293.62
#Mann=4,-1,0
  4495.6    0.08       0  4950.1    0.07       0  4956.1    0.08       0
  5441.7    0.05       0
Bank Sta=4950.1,4956.1
Exp/Cntr=0.3,0.1

Type RM Length L Ch R = 1,4565,374,374,374
BEGIN DESCRIPTION:
Mapping XS 2fa381e7
END DESCRIPTION:
XS GIS Cut Line= 2
      3631548.57     10704283.75      3630255.19     10704379.24
#Sta/Elev= 30
  4619.4  274.13  4658.5  271.79  4738.7  270.14  4768.8  269.54  4778.2  270.92
  4899.1  266.83  4912.3  263.94  4929.2  261.83  4979.3  262.16  4989.4  261.85
  4996.4  260.37  4999.1  259.87  5002.4  260.37  5009.4  262.03  5059.6  263.10
  5089.6  265.73  5139.8  268.13  5178.5  271.19  5183.5  270.78  5230.0  274.42
  5316.6  276.17  5321.6  274.63  5330.3  274.55  5340.3  276.13  5454.7  283.29
  5500.7  288.88  5631.1  292.12  5781.5  291.93  5859.0  290.43  5916.3  291.23
#Mann=4,-1,0
  4619.4    0.05       0  4778.2    0.16       0  4996.4    0.03       0
  5002.4    0.05       0
Bank Sta=4996.4,5002.4
Exp/Cntr=0.3,0.1

Type RM Length L Ch R = 1,4191,419,419,419
BEGIN DESCRIPTION:
UNT 489 IN LACR 9.0
END DESCRIPTION:
XS GIS Cut Line= 3
      3631673.39     10704062.05      3631093.57     10704072.46
      3630883.18     10704110.40
#Sta/Elev= 30
  4620.2  282.95  4654.0  283.21  4714.0  280.99  4784.0  280.71  4844.0  278.39
  4864.0  276.81  4884.0  273.95  4894.0  270.50  4904.0  268.44  4914.0  265.25
  4934.0  262.84  4944.0  262.49  4954.0  261.36  4984.0  260.25  5001.0  258.99
  5003.8  258.49  5007.0  258.99  5014.0  260.92  5044.1  260.38  5084.1  260.53
  5094.1  261.28  5104.1  262.82  5184.1  264.78  5217.4  266.07  5224.5  266.77
  5234.6  266.80  5271.0  269.60  5315.9  272.29  5346.4  274.91  5413.9  278.94
#Mann=3,-1,0
  4620.2    0.05       0  5001.0    0.03       0  5007.0    0.05       0
Bank Sta=5001,5007
Exp/Cntr=0.3,0.1

Type RM Length L Ch R = 1,3772,439,439,439
BEGIN DESCRIPTION:
UNT 489 IN LACR 8.0
END DESCRIPTION:
XS GIS Cut Line= 3
      3631399.64     10703560.16      3631149.61     10703810.19
      3630899.56     10703910.21
#Sta/Elev= 30
  4626.7  285.21  4640.9  285.27  4669.2  283.44  4683.3  277.10  4697.4  274.18
  4711.6  272.76  4732.8  268.36  4739.9  267.99  4754.0  264.77  4768.2  262.52
  4782.3  261.33  4796.4  259.41  4821.7  257.36  4824.5  256.86  4827.7  257.36
  4853.0  258.32  4881.3  258.10  4909.6  258.82  4923.7  258.10  4983.0  258.92
  4995.1  257.47  5001.8  257.68  5024.7  259.10  5034.1  260.71  5049.0  261.66
  5073.2  264.88  5132.4  267.86  5141.8  268.98  5174.2  270.12  5249.6  274.65
#Mann=3,-1,0
  4626.7    0.05       0  4821.7    0.03       0  4827.7    0.05       0
Bank Sta=4821.7,4827.7
Exp/Cntr=0.3,0.1

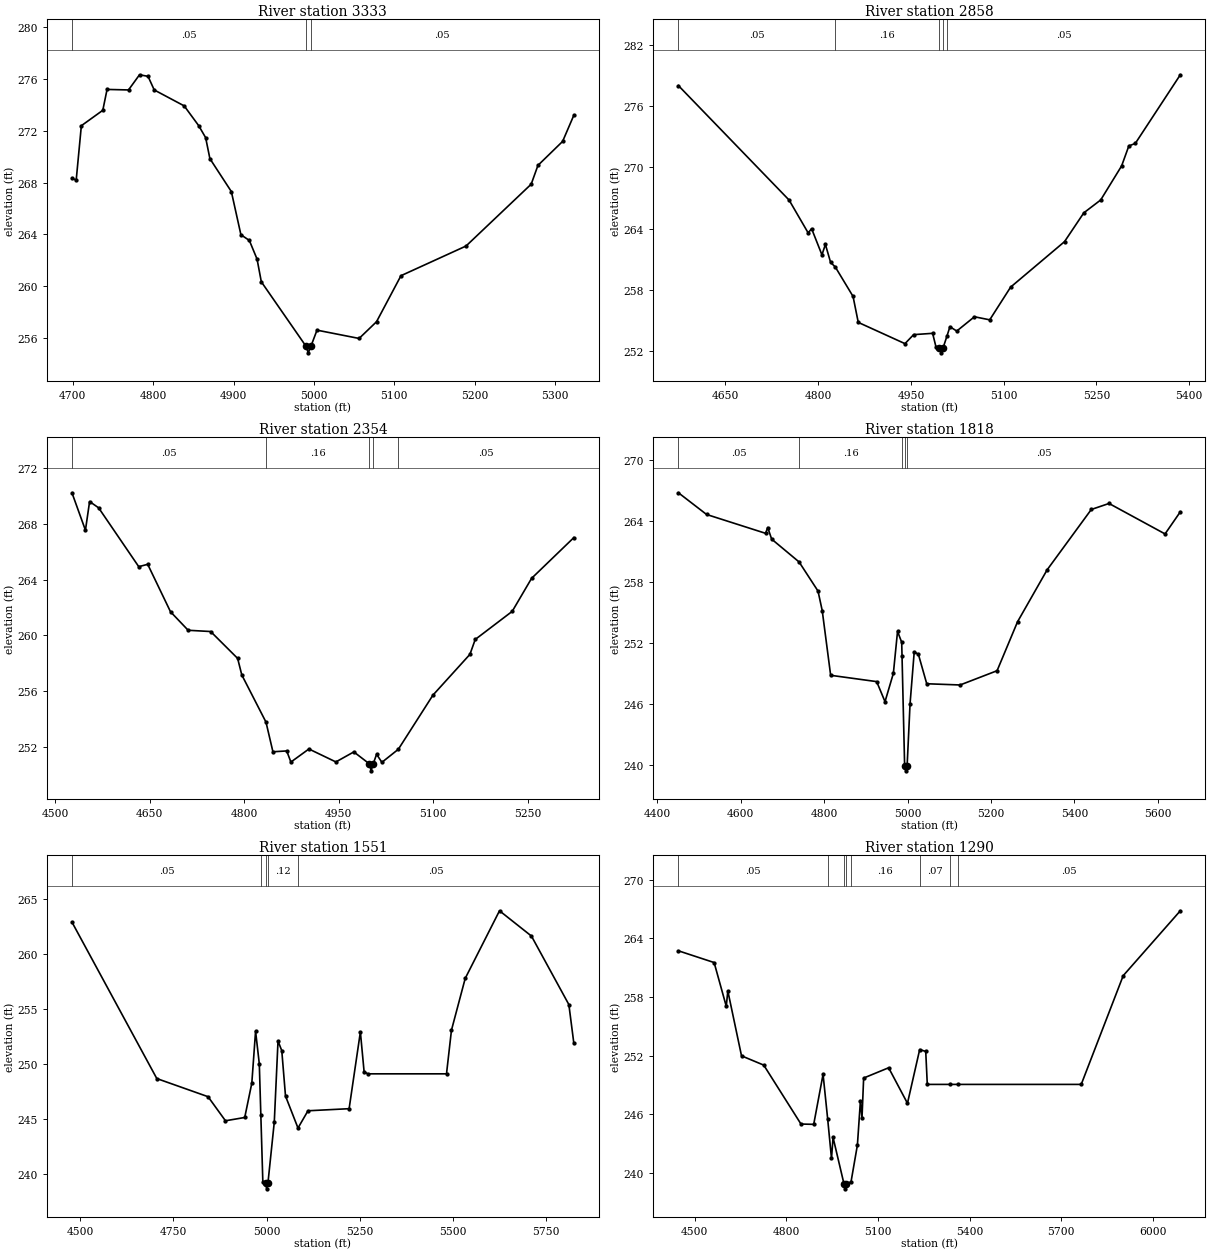
Type RM Length L Ch R = 1,3333,475,475,475
BEGIN DESCRIPTION:
UNT 489 IN LACR 7.0
END DESCRIPTION:
XS GIS Cut Line= 3
      3631329.67     10703332.89      3630974.03     10703447.98
      3630749.61     10703560.19
#Sta/Elev= 30
  4698.9  268.32  4704.2  268.19  4710.6  272.38  4737.3  273.57  4742.6  275.18
  4769.3  275.14  4783.0  276.31  4793.6  276.19  4801.3  275.14  4838.6  273.91
  4856.6  272.39  4865.3  271.46  4870.6  269.84  4897.3  267.30  4909.2  263.97
  4919.7  263.53  4929.3  262.09  4934.6  260.34  4990.3  255.36  4993.0  254.86
  4996.3  255.36  5003.9  256.61  5056.3  255.97  5078.0  257.26  5108.4  260.81
  5189.4  263.10  5270.5  267.87  5278.9  269.32  5309.6  271.17  5323.6  273.19
#Mann=3,-1,0
  4698.9    0.05       0  4990.3    0.03       0  4996.3    0.05       0
Bank Sta=4990.3,4996.3
Exp/Cntr=0.3,0.1

Type RM Length L Ch R = 1,2858,504,504,504
BEGIN DESCRIPTION:
UNT 489 IN LACR 6.0
END DESCRIPTION:
XS GIS Cut Line= 3
      3631099.64     10702960.17      3630699.61     10703160.19
      3630599.60     10703510.23
#Sta/Elev= 30
  4574.2  278.01  4753.1  266.81  4783.9  263.60  4789.5  264.01  4806.2  261.45
  4811.8  262.47  4820.2  260.71  4827.8  260.26  4856.5  257.38  4864.9  254.84
  4940.4  252.76  4954.4  253.64  4985.1  253.77  4990.7  252.40  4996.1  252.36
  4998.8  251.86  5002.1  252.36  5008.4  253.52  5013.1  254.42  5024.1  253.99
  5052.7  255.39  5077.4  255.09  5111.2  258.29  5198.3  262.74  5229.5  265.56
  5256.8  266.82  5290.6  270.15  5302.3  272.11  5312.7  272.35  5385.5  279.07
#Mann=5,-1,0
  4574.2    0.05       0  4827.8    0.16       0  4996.1    0.07       0
  5002.1    0.16       0  5008.4    0.05       0
Bank Sta=4996.1,5002.1
Exp/Cntr=0.3,0.1

Type RM Length L Ch R = 1,2354,536,536,536
BEGIN DESCRIPTION:
UNT 489 IN LACR 5.0
END DESCRIPTION:
XS GIS Cut Line= 3
      3630699.64     10702660.16      3630349.61     10702960.19
      3630199.62     10703260.16
#Sta/Elev= 30
  4526.9  270.24  4548.3  267.55  4554.9  269.61  4569.2  269.16  4632.9  264.93
  4647.1  265.10  4683.3  261.69  4711.3  260.36  4747.0  260.27  4789.8  258.34
  4796.4  257.15  4834.8  253.76  4845.8  251.63  4867.7  251.69  4874.3  250.89
  4902.9  251.83  4945.7  250.90  4974.2  251.62  4998.9  250.76  5001.6  250.26
  5004.9  250.76  5010.3  251.45  5018.7  250.87  5044.8  251.81  5099.7  255.70
  5158.4  258.63  5166.8  259.70  5225.5  261.72  5256.2  264.09  5323.3  267.02
#Mann=5,-1,0
  4526.9    0.05       0  4834.8    0.16       0  4998.9    0.07       0
  5004.9    0.16       0  5044.8    0.05       0
Bank Sta=4998.9,5004.9
Exp/Cntr=0.3,0.1

Type RM Length L Ch R = 1,1818,267,267,267
BEGIN DESCRIPTION:
UNT 489 IN LACR 4.0
END DESCRIPTION:
XS GIS Cut Line= 4
      3630650.84     10702535.55      3630261.91     10702591.12
      3629893.85     10702591.12      3629588.29     10702910.57
#Sta/Elev= 30
  4450.8  266.74  4518.3  264.61  4659.7  262.76  4664.8  263.33  4674.3  262.19
  4740.0  259.95  4785.4  257.09  4795.5  255.17  4815.7  248.82  4926.0  248.20
  4946.0  246.23  4966.0  249.01  4976.0  253.13  4986.0  252.06  4986.8  250.67
  4993.0  239.94  4995.7  239.44  4999.0  239.94  5006.0  246.02  5016.0  251.12
  5026.0  250.88  5046.0  247.99  5126.0  247.87  5214.6  249.27  5263.7  254.08
  5334.5  259.17  5440.4  265.10  5482.9  265.69  5617.2  262.70  5653.8  264.87
#Mann=5,-1,0
  4450.8    0.05       0  4740.0    0.16       0  4986.8    0.05       0
  4993.0    0.03       0  4999.0    0.05       0
Bank Sta=4993,4999
Exp/Cntr=0.3,0.1

Type RM Length L Ch R = 1,1551,261,261,261
BEGIN DESCRIPTION:
UNT 489 IN LACR 3.0
END DESCRIPTION:
XS GIS Cut Line= 4
      3630636.91     10702389.73      3630178.58     10702320.28
      3629803.58     10702355.01      3629394.22     10702653.35
#Sta/Elev= 30
  4477.6  262.87  4705.3  248.64  4842.8  246.99  4889.5  244.80  4941.2  245.10
  4960.2  248.22  4970.3  252.95  4980.3  249.98  4984.4  245.34  4989.8  239.22
  4997.4  239.11  5000.1  238.61  5003.4  239.11  5020.5  244.68  5030.5  252.05
  5040.6  251.18  5050.6  247.05  5084.1  244.14  5110.9  245.71  5221.3  245.90
  5251.5  252.88  5261.5  249.26  5271.5  249.07  5482.6  249.07  5495.9  253.04
  5532.8  257.75  5624.8  263.90  5710.5  261.60  5810.9  255.37  5824.3  251.84
#Mann=5,-1,0
  4477.6    0.05       0  4984.4    0.12       0  4997.4    0.07       0
  5003.4    0.12       0  5084.1    0.05       0
Bank Sta=4997.4,5003.4
Exp/Cntr=0.3,0.1

Type RM Length L Ch R = 1,1290,110,110,110
BEGIN DESCRIPTION:
UNT 489 IN LACR 2.0
END DESCRIPTION:
XS GIS Cut Line= 3
      3630622.97     10702188.33      3629893.85     10702035.56
      3629004.95     10702160.56
#Sta/Elev= 30
  4447.1  262.72  4564.0  261.52  4603.7  257.05  4608.8  258.62  4653.6  251.99
  4726.4  251.04  4848.2  245.02  4889.9  244.99  4920.5  250.10  4935.7  245.50
  4948.1  241.50  4953.2  243.65  4989.0  238.90  4991.8  238.40  4995.0  238.90
  5012.0  239.11  5032.9  242.88  5042.8  247.41  5047.9  245.63  5053.3  249.72
  5135.1  250.77  5196.7  247.14  5236.7  252.63  5256.5  252.44  5261.6  249.07
  5337.1  249.07  5360.9  249.07  5765.4  249.07  5902.8  260.18  6089.7  266.81
#Mann=8,-1,0
  4447.1    0.05       0  4935.7    0.12       0  4989.0    0.07       0
  4995.0    0.12       0  5012.0    0.16       0  5236.7    0.07       0
  5337.1    0.16       0  5360.9    0.05       0
Bank Sta=4989,4995
Exp/Cntr=0.3,0.1

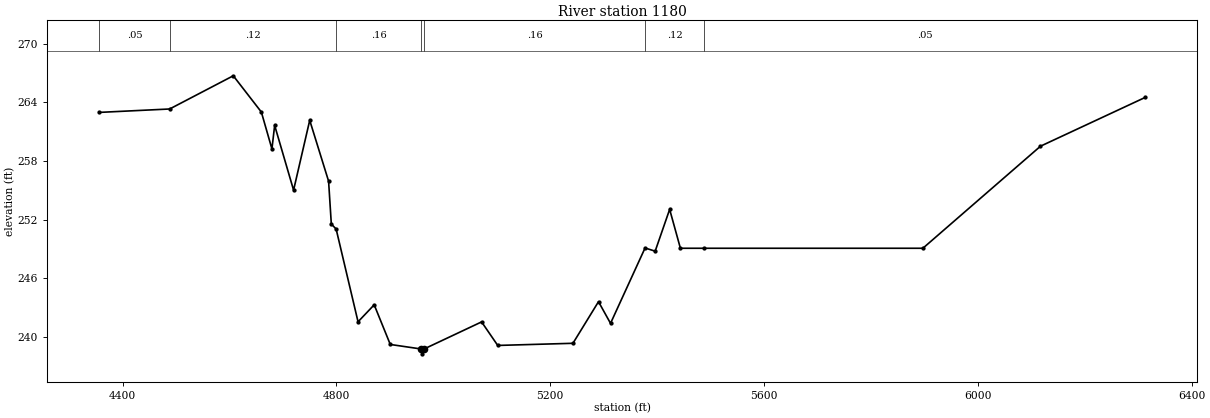
Type RM Length L Ch R = 1,1180,0,0,0
BEGIN DESCRIPTION:
UNT 489 IN LACR 1.0
END DESCRIPTION:
XS GIS Cut Line= 4
      3630738.69     10702167.43      3630519.94     10702021.60
      3629441.81     10701914.83      3628835.00     10701979.94
#Sta/Elev= 30
  4356.2  262.98  4488.1  263.33  4607.1  266.73  4659.6  263.02  4679.4  259.24
  4684.5  261.65  4719.9  255.02  4750.1  262.17  4785.4  255.94  4790.5  251.55
  4799.5  251.04  4840.5  241.54  4870.7  243.28  4900.8  239.22  4958.1  238.76
  4960.9  238.26  4964.1  238.76  5071.6  241.53  5101.8  239.12  5242.5  239.34
  5290.3  243.60  5312.8  241.38  5377.4  249.10  5396.3  248.77  5423.4  253.05
  5443.5  249.07  5487.4  249.07  5897.1  249.07  6117.1  259.52  6312.8  264.51
#Mann=7,-1,0
  4356.2    0.05       0  4488.1    0.12       0  4799.5    0.16       0
  4958.1    0.07       0  4964.1    0.16       0  5377.4    0.12       0
  5487.4    0.05       0
Bank Sta=4958.1,4964.1
Exp/Cntr=0.3,0.1

Chan Stop Cuts=-1