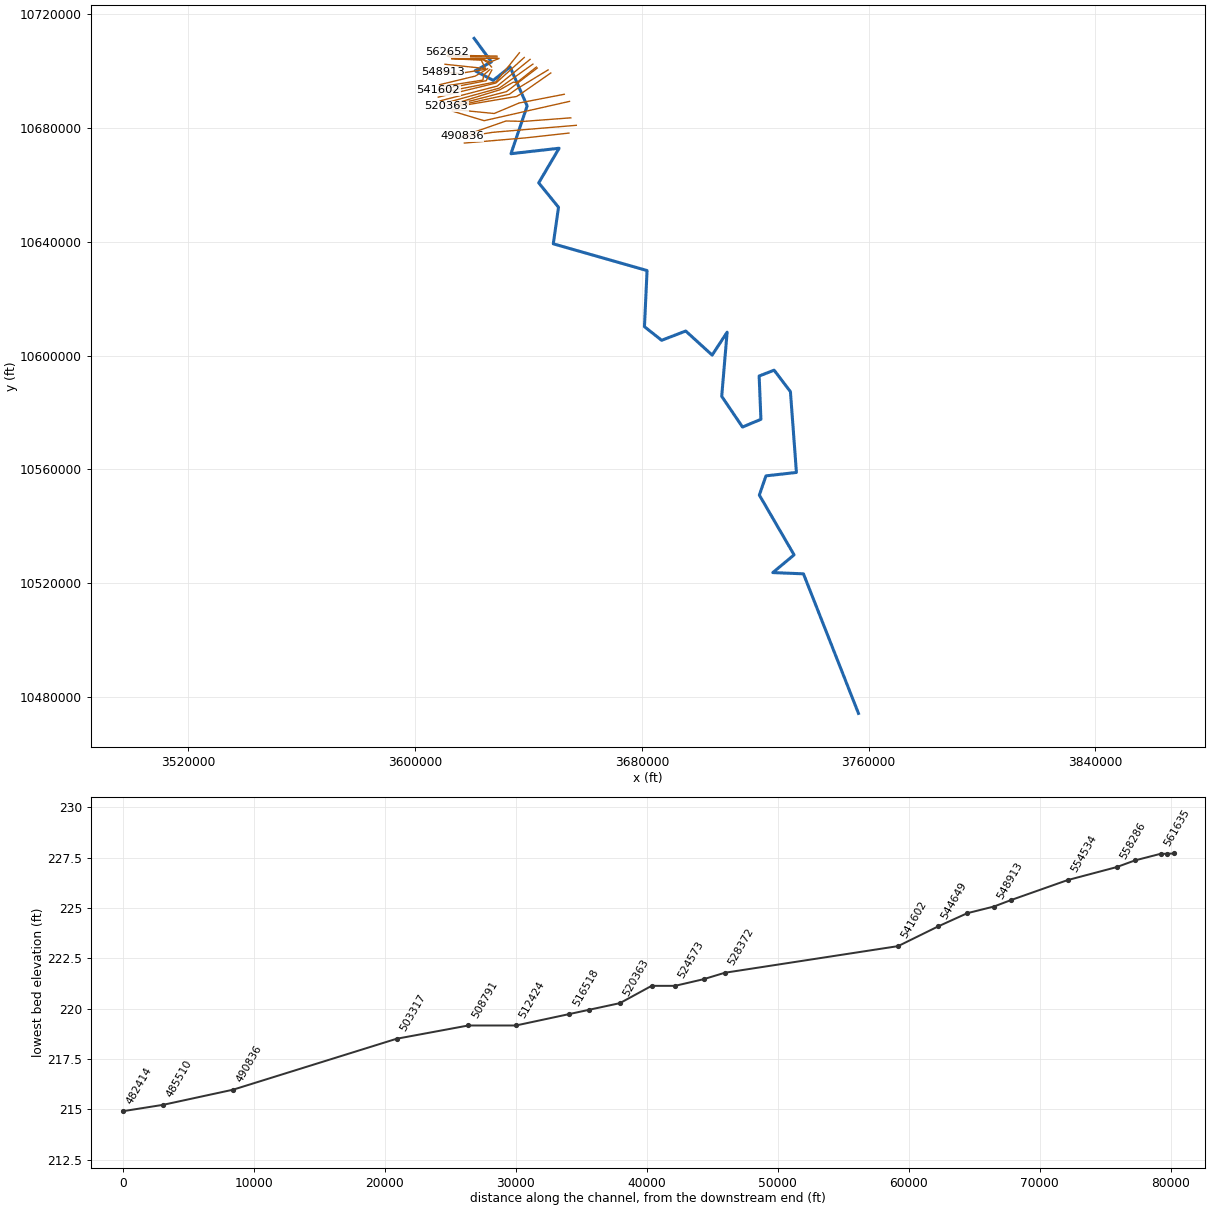
--- TRINITY RIVER.prj (project) ---

Proj Title=TRINITY RIVER Base Level Engineering
Current Plan=p07
Default Exp/Contr=0.3,0.1
English Units
Geom File=g06
Flow File=f06
Plan File=p07
Y Axis Title=Elevation
X Axis Title(PF)=Main Channel Distance
X Axis Title(XS)=Station
BEGIN DESCRIPTION:
END DESCRIPTION:
DSS Export Rating Curves= 0
DSS Export Rating Curve Sorted= 0
DSS Export Volume Flow Curves= 0
DXF Filename=..\..\HEC-RAS_5.0.7_nvalue\LTT_Mainstem.
DXF OffsetX= 0
DXF OffsetY= 0
DXF ScaleX= 1
DXF ScaleY= 10

--- TRINITY RIVER.p07 (plan) ---

Plan Title=Multiple_Profiles
Program Version=4.10
Short Identifier=MP
Geom File=g06
Flow File=f06
Subcritical Flow
K Sum by GR= 0
Std Step Tol= 0.01
Critical Tol= 0.01
Num of Std Step Trials= 20
Max Error Tol= 0.3
Flow Tol Ratio= 0.001
Split Flow NTrial= 30
Split Flow Tol= 0.02
Split Flow Ratio= 0.02
Log Output Level= 0
Friction Slope Method= 1
Unsteady Friction Slope Method= 2
Unsteady Bridges Friction Slope Method= 1
Parabolic Critical Depth
Global Vel Dist= 0 , 0 , 0
Global Log Level= 0
CheckData=True
Encroach Param=-1 ,0,0, 0
Computation Interval=1MIN
Output Interval=1HOUR
Run HTab= 0
Run UNet= 0
Run PostProcess= 0
Run WQNet= 0
UNET Theta= 1
UNET Theta Warmup= 1
UNET ZTol= 0.02
UNET ZSATol= 0.02
UNET MxIter= 20
UNET MaxInSteps= 0
UNET DtIC= 0
UNET DtMin= 0
UNET MaxCRTS= 20
UNET WFStab= 2
UNET SFStab= 1
UNET WFX= 1
UNET SFX= 1
UNET DSS MLevel= 4
UNET DZMax Abort= 100
UNET Convert EG Bridges= 0
UNET Use Existing IB Tables=-1
UNET Froude Reduction=False
UNET Froude Limit= 0.8
UNET Froude Power= 4
UNET Time Slicing=0,0, 5
UNET Junction Losses=0
Instantaneous Interval=1HOUR
Write IC File= 0
Write IC File at Sim End=0
Echo Input=False
Echo Parameters=False
Echo Output=False
Write Detailed= 0
WQ AD Non Conservative
WQ ULTIMATE=-1
WQ Max Comp Step=1HOUR
WQ Output Interval=15MIN
WQ Output Selected Increments= 0
WQ Output face flow=0
WQ Output face velocity=0
WQ Output face area=0
WQ Output face dispersion=0
WQ Output cell volume=0
WQ Output cell surface area=0
WQ Output cell continuity=0
WQ Output cumulative cell continuity=0
WQ Output face conc=0
WQ Output face dconc_dx=0
WQ Output face courant=0
WQ Output face peclet=0
WQ Output face adv mass=0
WQ Output face disp mass=0
WQ Output cell mass=0
WQ Output cell source sink temp=0
WQ Output cell source sink nsm=0
WQ Output MaxMinRange=-1
WQ Daily Max Min Mean=-1
WQ Daily Range=0
WQ Daily Time=0
WQ Create Restart=0
WQ Fixed Restart=0
WQ System Summary=0
WQ Use Fixed Temperature=0
Sorting and Armoring Iterations= 10
XS Update Threshold= 0.02
Hydraulics Update Threshold= 0.02
Energy Slope Method= 1
Volume Change Method= 1
XS Weighting Method= 0
Number of US Weighted Cross Sections= 1
Number of DS Weighted Cross Sections= 1
Upstream XS Weight=0
Main XS Weight=1
Downstream XS Weight=0
Number of DS XS's Weighted with US Boundary= 1
Upstream Boundary Weight= 1
Weight of XSs Associated with US Boundary= 0
Number of US XS's Weighted with DS Boundary= 1
Downstream Boundary Weight= 0.5
Weight of XSs Associated with DS Boundary= 0.5
Sediment Output Level= 3
Mass or Volume Output= 0
Output Increment Type= 1
Profile and TS Output Increment= 1
XS Output Flag= 0
XS Output Increment= 10
Disregard all LS=0
Disregard all Conn=0
Disregard all Breaches=0
Disregard all Pumps=0

--- TRINITY RIVER.f06 (steady flow) ---

Flow Title=Final_Discharges
Program Version=4.10
Number of Profiles= 7
Profile Names=10-yr,25-yr,50-yr,100-yr MIN,100-yr,100-yr PLUS,500-yr
River Rch & RM=LTT_River,1               ,562652
   78515  105321  128053  113360  153307  207329  219265
River Rch & RM=LTT_River,1               ,559672
   80679  108082  131317  116170  157106  212468  224325
River Rch & RM=LTT_River,1               ,419929
   81646  109393  132928  117615  159061  215111  227214
River Rch & RM=LTT_River,1               ,377940
   84627  113243  137513  121598  164447  222395  234561
River Rch & RM=LTT_River,1               ,261337
   86308  115402  140077  123817  167449  226455  238618
River Rch & RM=LTT_River,1               ,243302
   91817  122753  148990  131688  178092  240849  253749
River Rch & RM=LTT_River,1               ,162501
   92500  123630  150032  132590  179312  242499  255400
River Rch & RM=LTT_River,1               ,140445
   93222  124563  151144  133556  180619  244266  257186
River Rch & RM=LTT_River,1               ,92327
   93523  124951  151606  133958  181163  245001  257929
River Rch & RM=LTT_River,1               ,31238
   96512  128852  156288  138059  186709  252502  265661
River Rch & RM=LTT_River,1               ,21122
   96557  128910  156357  138119  186789  252611  265772
River Rch & RM=LTT_River,1               ,2034
   97409  130007  157661  139250  188319  254679  267850
Boundary for River Rch & Prof#=LTT_River,1               , 1
Up Type= 0
Dn Type= 1
Dn Known WS=186.82
Boundary for River Rch & Prof#=LTT_River,1               , 2
Up Type= 0
Dn Type= 1
Dn Known WS=188.7
Boundary for River Rch & Prof#=LTT_River,1               , 3
Up Type= 0
Dn Type= 1
Dn Known WS=190.03
Boundary for River Rch & Prof#=LTT_River,1               , 4
Up Type= 0
Dn Type= 1
Dn Known WS=189.14
Boundary for River Rch & Prof#=LTT_River,1               , 5
Up Type= 0
Dn Type= 1
Dn Known WS=191.3
Boundary for River Rch & Prof#=LTT_River,1               , 6
Up Type= 0
Dn Type= 1
Dn Known WS=193.61
Boundary for River Rch & Prof#=LTT_River,1               , 7
Up Type= 0
Dn Type= 1
Dn Known WS=193.98
DSS Import GetInterval= 0
DSS Import GetPeak= 0
DSS Import FillOption= 0

--- TRINITY RIVER.g06 (geometry) ---

Geom Title=Existing Conditions_Mod
Program Version=4.10

River Reach=LTT_River       ,1
Reach XY= 30
3620849.6090573810711575.18861243626954.6349050610703276.7695137
3621215.1224339810700165.09102583627585.7776716410696788.4862305
3633542.3179238910701503.88592043639558.4331882110687781.4251764
3633851.6270165610670994.50501013650834.5930505510672917.3039861
 3643633.787570310660739.61574313650617.1049684710652149.0489347
3648777.6909963810639290.18160793681849.9463740610629894.3240873
3680929.6089758910610140.18839883686991.5637154710605354.7478385
3695483.9866912210608615.81087013704805.8988216410600147.7933574
 3710086.406633310608204.02658873708179.77133897 10585640.907345
3715515.1985972210574841.30525663722004.8834524810577561.3165488
3721381.8318770510592793.49868283726663.3692142210594841.0962936
 3732412.428910310587285.20819023734530.9459987110558871.5347027
3723778.8589071310557665.95279633721450.1959135510550912.7920901
3733704.4115625510529871.84073373726200.1175160610523645.0241191
3737008.1047583110523208.5942177 3756409.099420810474119.7694953

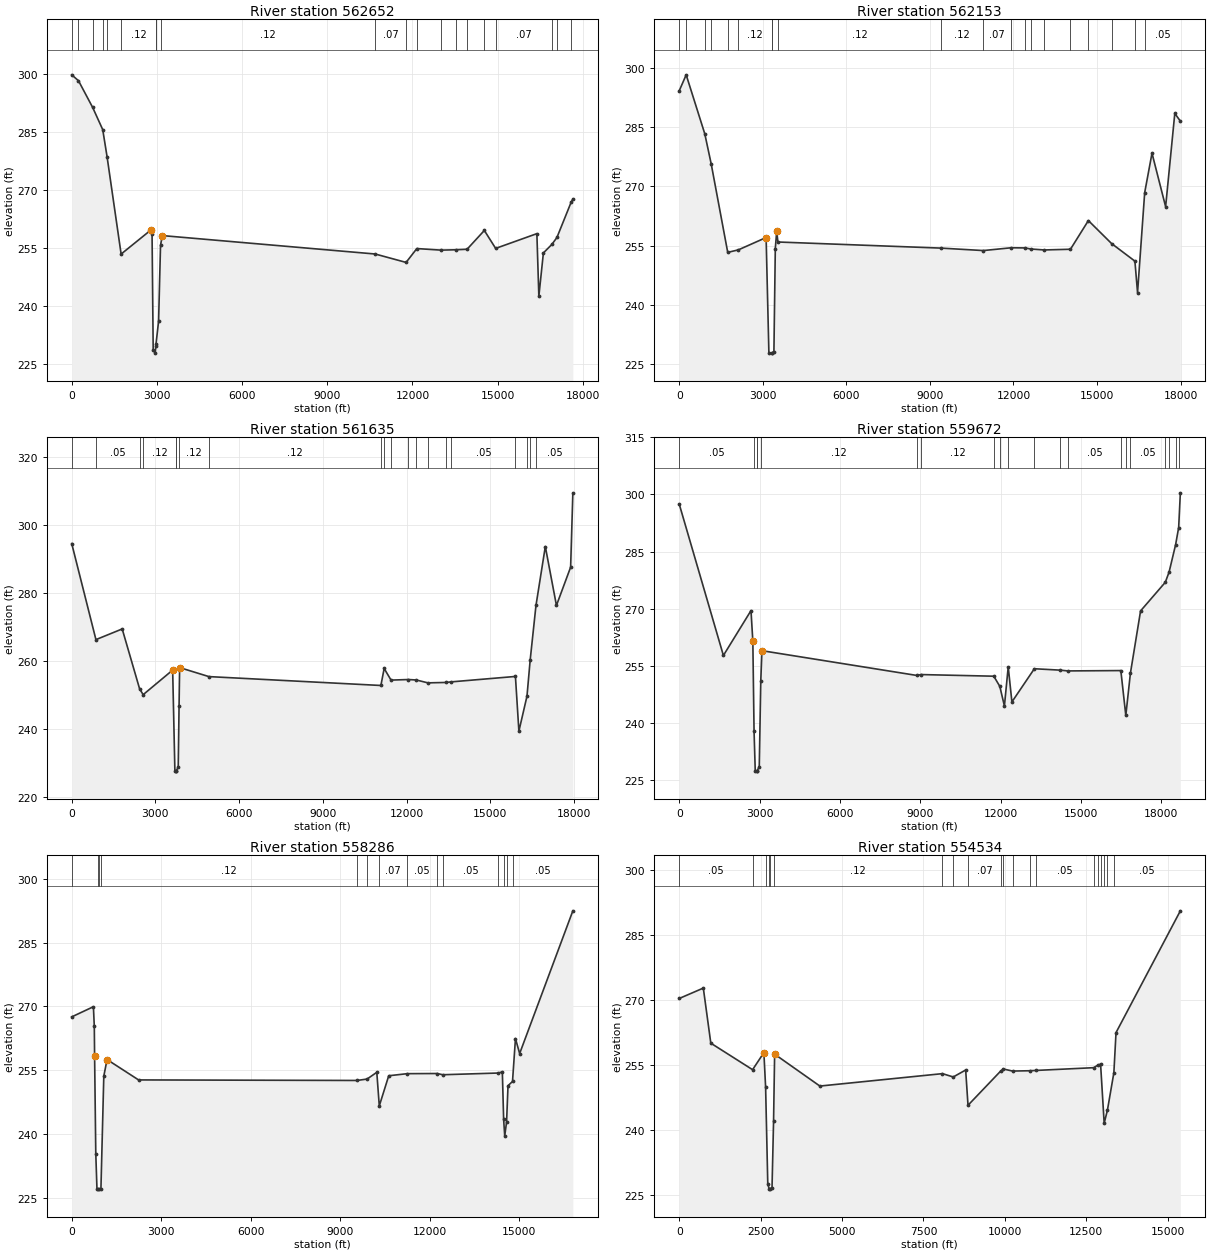
Type RM Length L Ch R = 1 ,562652  ,499,499,499
XS GIS Cut Line= 3
3628919.0745457310705347.52193393614662.8842261310705584.6956721
3611358.8268578810706748.6756276
#Sta/Elev= 30
       0  299.73   237.7298.2083   736.5291.3052  1092.3285.5446  1245.8278.5062
    1740 253.345 2789.46  259.58 2829.64  258.62 2869.64  228.55 2939.63  227.71
  2962.9229.5704  2968.9230.0726 3059.61  235.94  3128.1255.5955  3189.6  258.13
 10689.3253.3607 11777.6251.1836 12155.7254.7704 13007.9254.3634 13529.7254.4558
 13925.9 254.591 14533.5259.4547 14932.3254.811616384.08  258.6316453.94  242.44
16613.63  253.64 16912.6255.8473 17090.4257.6341 17591.5266.7725 17651.6  267.59
#Mann= 20 ,-1 , 0
       0     .05       0   237.7     .16       0   736.5     .12       0
  1092.3     .16       0  1245.8     .12       0    1740     .12       0
  2962.9     .05       0  2968.9     .05       0  3128.1     .12       0
 10689.3     .07       0 11777.6     .07       0 12155.7     .05       0
 13007.9     .07       0 13529.7     .05       0 13925.9     .05       0
 14533.5     .05       0 14932.3     .07       0 16912.6     .12       0
 17090.4     .05       0 17591.5     .16       0
Bank Sta=2789.46,3189.6
XS Rating Curve= 0 ,0
Exp/Cntr=0.3,0.1

Type RM Length L Ch R = 1 ,562153  ,518,518,518
XS GIS Cut Line= 3
3628958.1371316310704982.93867363614472.5253548910705243.1664996
3611168.4679866310706407.1464551
#Sta/Elev= 30
       0  294.29   249.4298.3493   917.1283.3893  1147.1275.7658  1741.4253.2708
  2120.9253.9028 3119.55  257.04 3219.53  227.69  3327.3227.6943  3333.3227.6948
 3399.51  228.05  3449.5  254.23 3499.49  258.62    3543255.9049  9402.1 254.353
 10916.6253.7298 11914.4254.4378 12406.8254.4027 12633.9254.1234 13104.4253.8841
 14045.6254.0646   14689261.3451 15521.6255.5163 16359.5251.045516454.23  243.05
 16710.6268.442416973.22  278.4517462.26  264.8717791.62  288.5517991.23  286.59
#Mann= 20 ,-1 , 0
       0     .12       0   249.4     .16       0   917.1     .16       0
  1147.1     .12       0  1741.4     .05       0  2120.9     .12       0
  3327.3     .05       0  3333.3     .05       0    3543     .12       0
  9402.1     .12       0 10916.6     .07       0 11914.4     .07       0
 12406.8     .05       0 12633.9     .07       0 13104.4     .07       0
 14045.6     .05       0   14689     .05       0 15521.6     .07       0
 16359.5     .12       0 16710.6     .05       0
Bank Sta=3119.55,3499.49
XS Rating Curve= 0 ,0
Exp/Cntr=0.3,0.1

Type RM Length L Ch R = 1 ,561635  ,1963.25,1963.25,1963.25
XS GIS Cut Line= 3
3629244.5955482110704514.18862683614573.0057969710704643.7224885
3611448.2144743810705673.2365056
#Sta/Elev= 30
       0  294.57   867.8266.3422 1809.03  269.48  2432.8251.8892  2560.4250.1612
 3618.07  257.39 3698.03  227.69  3742.2  227.69  3748.2  227.69 3817.96  228.97
  3847.5246.9302 3867.94  258.12  4918.2 255.472 11081.3 252.864 11198.6257.8609
 11445.4254.4435 12065.1254.6114 12351.8254.4792 12767.2 253.632 13422.3253.7551
 13605.2253.9255 15903.9255.517916028.08  239.44 16317.9249.7163 16431.7260.2789
 16640.5276.387516975.23  293.7117374.04  276.3917882.52  287.6417962.28  309.49
#Mann= 20 ,-1 , 0
       0     .05       0   867.8     .05       0  2432.8     .07       0
  2560.4     .12       0  3742.2     .05       0  3748.2     .05       0
  3847.5     .12       0  4918.2     .12       0 11081.3     .07       0
 11198.6     .05       0 11445.4     .07       0 12065.1     .05       0
 12351.8     .05       0 12767.2     .05       0 13422.3     .07       0
 13605.2     .05       0 15903.9     .07       0 16317.9     .07       0
 16431.7     .16       0 16640.5     .05       0
Bank Sta=3618.07,3867.94
XS Rating Curve= 0 ,0
Exp/Cntr=0.3,0.1

Type RM Length L Ch R = 1 ,559672  ,1386,1386,1386
XS GIS Cut Line= 5
3629611.5413366410704474.68083183626450.8186554810703195.6325369
3624177.7126373810704154.18672213614192.40255556 10704418.913883
3611479.1953835510705297.8632406
#Sta/Elev= 30
       0  297.45 1649.86  257.71 2680.73  269.49 2749.77  261.45  2795.3 237.775
 2839.76  227.36  2897.5  227.36  2903.5  227.36 2989.75  228.52  3046.5 251.109
 3089.74  258.97  8872.9252.4734  9033.6252.7025 11749.3 252.273 11973.9249.6097
12146.03  244.46 12288.4254.7171   12426  245.52 13264.5254.2328   14222253.8653
 14518.5253.6589 16494.4253.7506 16680.4241.9687 16852.5253.0597 17231.9  269.41
 18155.5276.9215 18297.4279.6137 18541.1286.8114 18654.7291.298618717.83   300.4
#Mann= 20 ,-1 , 0
       0     .05       0  2795.3     .05       0  2897.5     .05       0
  2903.5     .05       0  3046.5     .12       0  8872.9     .07       0
  9033.6     .12       0 11749.3     .07       0 11973.9     .05       0
 12288.4     .07       0 13264.5     .05       0   14222     .07       0
 14518.5     .05       0 16494.4     .07       0 16680.4     .05       0
 16852.5     .05       0 18155.5     .05       0 18297.4     .05       0
 18541.1     .08       0 18654.7     .05       0
Bank Sta=2749.77,3089.74
XS Rating Curve= 0 ,0
Exp/Cntr=0.3,0.1

Type RM Length L Ch R = 1 ,558286  ,3752,3752,3752
XS GIS Cut Line= 4
 3627002.685005810701480.35479953625761.3653099710702921.3269831
3624138.1014961310704015.07676423612940.1849156310704431.7435817
#Sta/Elev= 30
       0  267.52  726.91  269.91  756.78  265.29  766.74  258.38  806.57  235.38
   846.4  227.03   897.2  227.03   903.2  227.03   978.8227.0388 1075.43   253.6
 1184.96  257.49 2241.45   252.7  9562.5252.5737  9899.6252.902110226.83  254.49
 10309.9246.592210626.67  253.68 11248.5254.1711 12255.1254.2059 12437.2253.9189
 14294.4254.320414435.18  254.58 14478.4243.454114515.15  239.52 14577.5242.8635
14625.11  251.34 14775.9252.339114875.01  262.4315014.96   258.916798.84  292.45
#Mann= 14 ,-1 , 0
       0     .05       0   897.2     .05       0   903.2     .05       0
   978.8     .12       0  9562.5     .07       0  9899.6     .12       0
 10309.9     .07       0 11248.5     .05       0 12255.1     .07       0
 12437.2     .05       0 14294.4     .07       0 14478.4     .05       0
 14577.5     .07       0 14775.9     .05       0
Bank Sta=766.74,1184.96
XS Rating Curve= 0 ,0
Exp/Cntr=0.3,0.1

Type RM Length L Ch R = 1 ,554534  ,4320.81,4320.81,4320.81
XS GIS Cut Line= 3
3624799.9938731310701063.25392763623341.66050372 10703945.198295
3613035.6709451410704362.2991668
#Sta/Elev= 30
       0  270.38  739.98  272.78  969.97  260.07  2253.1253.9474 2599.93  257.89
  2653.1249.9142 2719.93  227.49  2767.4 226.383  2773.4226.3837 2849.93  226.72
  2897.5242.1379 2929.92  257.53 4319.32  250.17  8084.6253.0359    8415252.2676
 8796.87  253.87  8868.8245.7348  9871.7 253.629  9956.7254.1018 10235.6253.6322
 10768.8253.7045   10970253.7795 12729.6254.4109 12852.2254.9854 12940.3255.2254
 13050.6241.5922 13149.8244.5852 13348.2253.250213414.47  262.5115390.14  290.61
#Mann= 20 ,-1 , 0
       0     .05       0  2253.1     .12       0  2653.1     .05       0
  2767.4     .05       0  2773.4     .05       0  2897.5     .12       0
  8084.6     .07       0    8415     .12       0  8868.8     .07       0
  9871.7     .05       0  9956.7     .07       0 10235.6     .05       0
 10768.8     .12       0   10970     .05       0 12729.6     .07       0
 12852.2     .05       0 12940.3     .07       0 13050.6     .05       0
 13149.8     .07       0 13348.2     .05       0
Bank Sta=2599.93,2929.92
XS Rating Curve= 0 ,0
Exp/Cntr=0.3,0.1

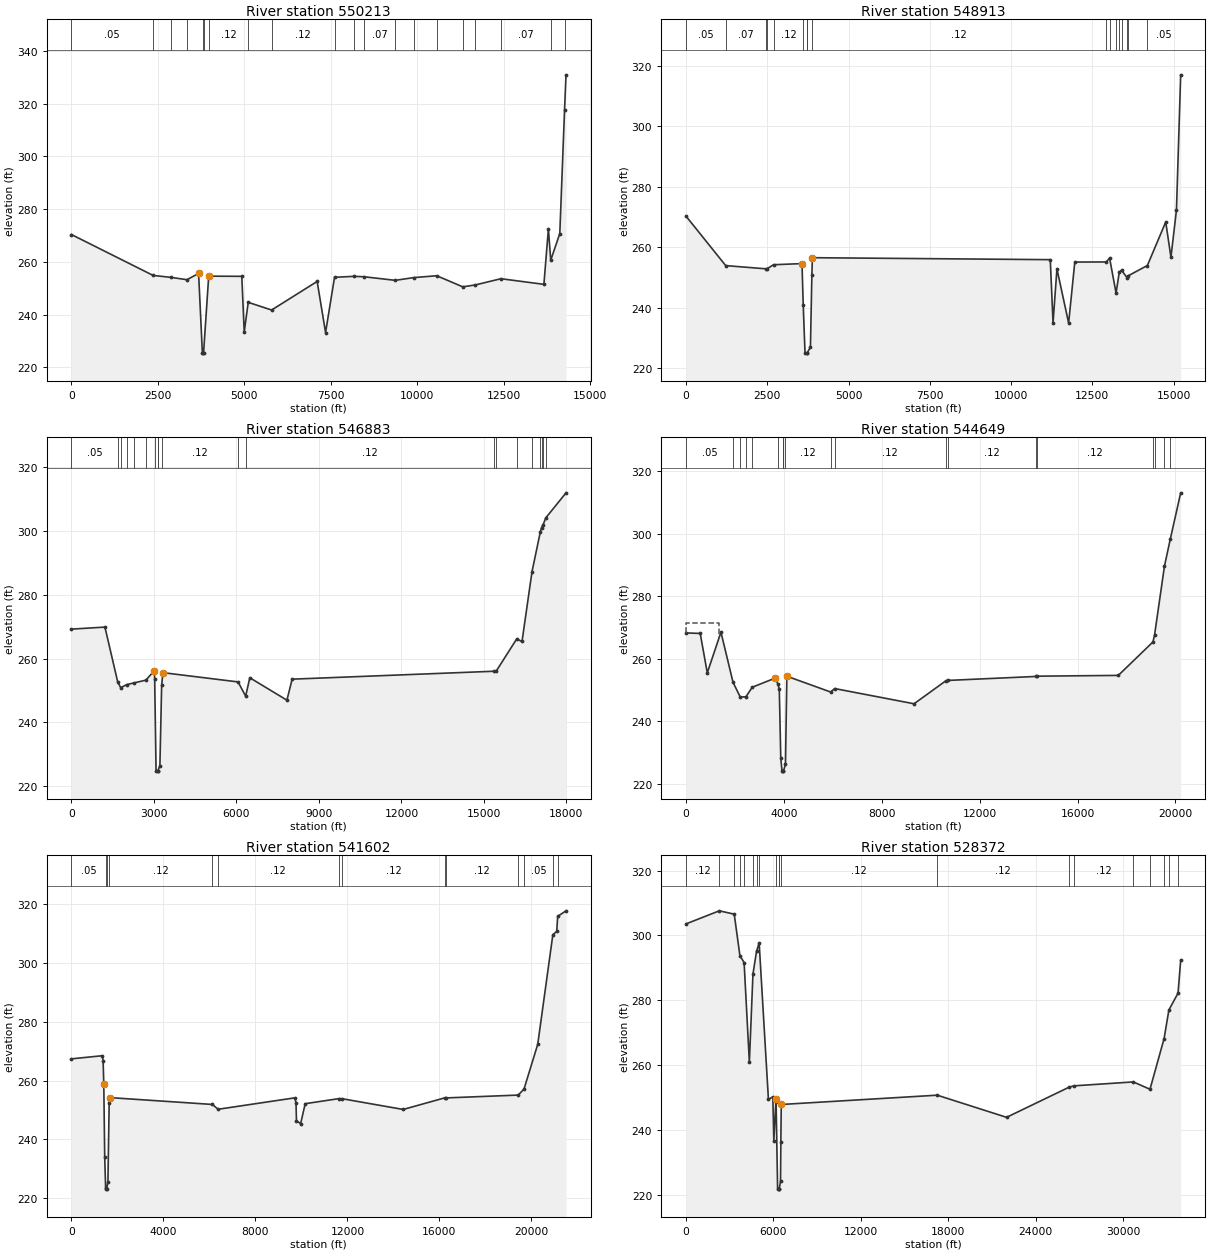
Type RM Length L Ch R = 1 ,550213  ,1300.22,1300.22,1300.22
XS GIS Cut Line= 2
3624819.6575477110700944.46249863610591.8447960510702454.2544265
#Sta/Elev= 30
       0  270.38  2364.2254.8592  2872.4254.1351  3342.3253.2441 3679.39   255.6
 3788.93  225.39  3816.9  225.39  3822.9  225.39  3971.7254.5867  4929.2  254.52
 4999.19   233.4  5115.2244.6504  5791.7241.7403 7108.88  252.58 7352.08   233.2
  7611.4254.1409  8169.1254.5156  8468.9254.3549  9368.4252.9968  9900.9254.0374
 10567.7254.7401 11319.6250.5385 11681.7251.2436 12423.7253.614413667.66  251.48
13797.63  272.48 13865.6260.633314127.57  270.75 14265.4317.770114307.53  330.95
#Mann= 20 ,-1 , 0
       0     .05       0  2364.2     .07       0  2872.4     .07       0
  3342.3     .12       0  3816.9     .05       0  3822.9     .05       0
  3971.7     .12       0  5115.2     .12       0  5791.7     .12       0
  7611.4     .05       0  8169.1     .05       0  8468.9     .07       0
  9368.4     .07       0  9900.9     .12       0 10567.7     .05       0
 11319.6     .07       0 11681.7     .05       0 12423.7     .07       0
 13865.6     .05       0 14265.4     .15       0
Bank Sta=3679.39,3971.7
XS Rating Curve= 0 ,0
Exp/Cntr=0.3,0.1

Type RM Length L Ch R = 1 ,548913  ,2030.05,2030.05,2030.05
XS GIS Cut Line= 3
3624940.7590115510700692.12113973615774.0923055610699233.7877703
 3609853.953555310699667.8154456
#Sta/Elev= 30
       0  270.34  1219.4254.0093  2468.5252.9333  2475.6252.8586  2691.6254.2964
  3566.9  254.67  3605.1240.8788 3659.95  225.07    3718  225.07    3724  225.07
 3826.68  227.08  3870.8250.9054 3886.63  256.6211205.86  255.9711290.59  235.04
11410.51  252.9211770.26  235.0311960.13  255.18 12930.9255.2108 13030.4256.5097
 13229.5 244.939   13329 251.846 13397.8252.4677 13572.4249.9665 13585.1250.5358
 14192.9254.037814758.22  268.4314918.11  256.7715087.99  272.37 15217.9  317.08
#Mann= 17 ,-1 , 0
       0     .05       0  1219.4     .07       0  2468.5     .05       0
  2475.6     .07       0  2691.6     .12       0  3605.1     .05       0
    3718     .05       0    3724     .05       0  3870.8     .12       0
 12930.9     .07       0 13030.4     .05       0 13229.5     .12       0
   13329     .07       0 13397.8     .12       0 13572.4     .07       0
 13585.1     .12       0 14192.9     .05       0
Bank Sta=3566.9,3886.63
XS Rating Curve= 0 ,0
Exp/Cntr=0.3,0.1

Type RM Length L Ch R = 1 ,546883  ,2234,2234,2234
XS GIS Cut Line= 3
 3625636.650336310700874.41276993621262.2128909710698296.4399075
 3608711.430249810695279.4593929
#Sta/Elev= 30
       0  269.21 1219.42  269.85    1681252.7844  1793.2250.8722  2010.1251.8236
  2276.9252.3708  2705.9253.2277 3018.56  256.22  3028.4   253.6 3078.53  224.88
  3133.8  224.74  3139.8  224.74 3218.46  226.44  3282.3251.7366 3328.41  255.58
  6060.8252.6788  6337.1248.2243 6487.36  253.98 7837.16  246.96 8027.13  253.54
 15364.4256.0211 15448.6256.0727 16188.9266.089216386.28  265.36 16749.1287.2108
   17052299.6827 17095.9300.9315 17152.9301.9151 17253.7304.090217985.96   311.9
#Mann= 20 ,-1 , 0
       0     .05       0    1681     .07       0  1793.2     .05       0
  2010.1     .05       0  2276.9     .07       0  2705.9     .12       0
  3028.4     .05       0  3133.8     .05       0  3139.8     .05       0
  3282.3     .12       0  6060.8     .05       0  6337.1     .12       0
 15364.4     .07       0 15448.6     .12       0 16188.9     .16       0
 16749.1     .05       0   17052     .16       0 17095.9     .05       0
 17152.9     .16       0 17253.7     .05       0
Bank Sta=3018.56,3328.41
XS Rating Curve= 0 ,0
Exp/Cntr=0.3,0.1

Type RM Length L Ch R = 1 ,544649  ,3047.1,3047.1,3047.1
XS GIS Cut Line= 4
3626399.52643523 10700592.7286223624231.7955344610698694.4108963
3623954.0178748110696888.85545233608636.0714766410694491.6000762
#Sta/Elev= 30
       0   268.3  578.28  268.14  867.42  255.53 1425.76  268.54  1919.9252.4923
  2215.3247.7817  2447.6247.8815    2704250.9206 3650.09  253.87  3757.7251.8771
 3809.81  250.25  3869.7  228.43 3919.61  224.08    3974224.0982    3980224.1002
  4062.5226.3073 4119.27  254.45  5908.7249.3915  6072.8 250.502 9316.54  245.63
 10621.6253.0106 10721.2253.1104 14310.9254.3798 14356.8 254.46517663.27  254.71
 19079.7265.4216 19144.8267.6332 19549.8289.6812 19791.5298.461920212.28  313.13
#Mann= 19 ,-1 , 0
       0     .05       0  1919.9     .07       0  2215.3     .12       0
  2447.6     .07       0    2704     .12       0  3757.7     .05       0
    3974     .05       0    3980     .05       0  4062.5     .12       0
  5908.7     .07       0  6072.8     .12       0 10621.6     .08       0
 10721.2     .12       0 14310.9     .07       0 14356.8     .12       0
 19079.7     .16       0 19144.8     .05       0 19549.8     .16       0
 19791.5     .05       0
#XS Ineff= 2 , 0
         1349.77  271.35
Permanent Ineff=
       F       F
Bank Sta=3650.09,4119.27
XS Rating Curve= 0 ,0
Exp/Cntr=0.3,0.1

Type RM Length L Ch R = 1 ,541602  ,13230,13230,13230
XS GIS Cut Line= 3
3627087.0263725510700405.22866893625134.5732564610696680.5222076
3608156.47105789 10693365.298195
#Sta/Elev= 30
       0  267.41 1348.53  268.48  1378.5  266.81 1408.46  258.84 1448.42   233.9
 1488.38  223.33  1525.8223.1039  1531.8223.1048 1588.17  225.57  1642.4252.4288
 1668.18  254.23  6131.7251.9007  6378.2250.2645 9715.05  254.15 9765.04   252.5
 9785.04   246.4 9965.02  245.35   10165  252.16   11616253.8659 11778.4253.8375
14424.59   250.2   16242254.1678   16273254.1181 19428.6  255.09 19678.2 257.147
20274.34  272.34 20931.9309.637621101.46  310.77 21141.3315.863721504.32  317.75
#Mann= 14 ,-1 , 0
       0     .05       0  1525.8     .05       0  1531.8     .05       0
  1642.4     .12       0  6131.7     .07       0  6378.2     .12       0
   11616     .05       0 11778.4     .12       0   16242     .07       0
   16273     .12       0 19428.6     .16       0 19678.2     .05       0
 20931.9     .08       0 21141.3     .05       0
Bank Sta=1408.46,1668.18
XS Rating Curve= 0 ,0
Exp/Cntr=0.3,0.1

Type RM Length L Ch R = 1 ,528372  ,1618.6,1618.6,1618.6
XS GIS Cut Line= 3
3636835.9622552210706506.91101933628572.07327122  10696263.85539
3608156.4710578910692280.2285147
#Sta/Elev= 30
       0  303.57  2281.2307.5924  3307.4306.5678    3697293.7889  3985.5 291.644
 4347.02  260.91  4593.2288.1108  4837.8295.0701  5018.7297.7079 5656.12  249.43
 5958.06  250.23 6025.87  236.72 6175.77  249.64    6183248.7082 6285.69  221.78
  6387.1  221.78  6393.1  221.78 6485.56  224.16  6508.4236.2711 6536.29  247.88
 17245.9250.747822007.35  243.92 26311.7253.2396 26651.3253.6326 30712.2254.8343
 31854.7 252.573 32823.4268.2065 33153.6277.0262 33780.7282.207633962.67  292.34
#Mann= 20 ,-1 , 0
       0     .12       0  2281.2     .12       0  3307.4     .16       0
    3697     .05       0  3985.5     .12       0  4593.2     .05       0
  4837.8     .16       0  5018.7     .12       0    6183     .05       0
  6387.1     .05       0  6393.1     .05       0  6508.4     .12       0
 17245.9     .12       0 26311.7     .05       0 26651.3     .12       0
 30712.2     .12       0 31854.7     .05       0 32823.4     .05       0
 33153.6     .16       0 33780.7     .05       0
Bank Sta=6175.77,6536.29
XS Rating Curve= 0 ,0
Exp/Cntr=0.3,0.1

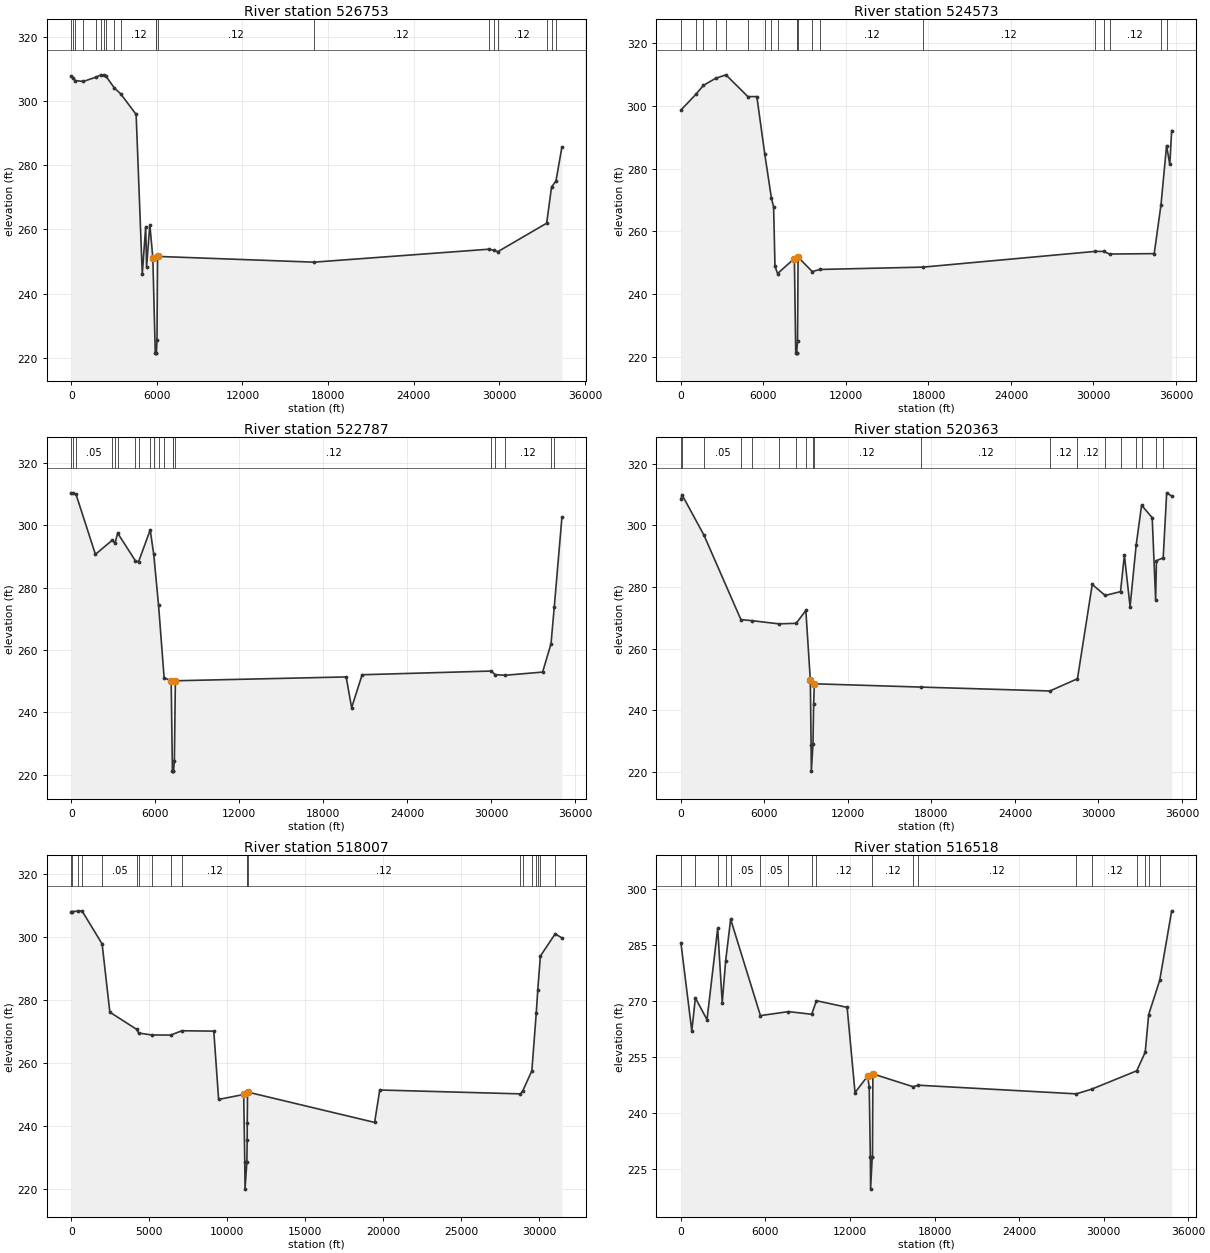
Type RM Length L Ch R = 1 ,526753  ,2180.25,2180.25,2180.25
XS GIS Cut Line= 3
3638537.3509128110704840.24440523628537.3508997310695847.1889005
3608199.8738582110690891.3398883
#Sta/Elev= 30
       0  307.72   132.3307.1727   285.5306.3598   845.9306.0856  1711.5307.3867
  2095.4308.1495  2299.9308.1004  2428.5 307.743  3027.6304.0423  3457.3302.2798
 4549.65  295.81 4979.62  246.12  5219.6  260.87  5279.6  248.42 5509.59  261.46
 5719.57  251.13 5889.56  221.46  5959.3  221.46  5965.3  221.46 6009.55   225.4
 6049.55  251.77  6053.8251.5883 17005.3249.7978 29252.8253.8332 29622.7253.5185
 29882.8253.0466 33310.8261.9314 33654.8273.2437 33961.2275.038234380.73  285.68
#Mann= 20 ,-1 , 0
       0     .05       0   132.3     .16       0   285.5     .12       0
   845.9     .12       0  1711.5     .08       0  2095.4     .08       0
  2299.9     .05       0  2428.5     .12       0  3027.6     .16       0
  3457.3     .12       0  5959.3     .05       0  5965.3     .05       0
  6053.8     .12       0 17005.3     .12       0 29252.8     .05       0
 29622.7     .08       0 29882.8     .12       0 33310.8     .16       0
 33654.8     .05       0 33961.2     .12       0
Bank Sta=5719.57,6049.55
XS Rating Curve= 0 ,0
Exp/Cntr=0.3,0.1

Type RM Length L Ch R = 1 ,524573  ,1785.62,1785.62,1785.62
XS GIS Cut Line= 3
 3640593.067273810704174.09842773628988.0675179710694769.0982089
3608894.3180073810689589.2565345
#Sta/Elev= 30
       0  298.71  1089.5303.7561  1629.9306.5763  2518.5308.8318  3272.1309.9549
  4864.7303.0019  5519.1  303.01  6100.2 284.539  6578.3270.6148  6738.9  267.82
 6838.89  248.85  7027.4246.5243 8248.67  251.33 8348.65  221.13  8408.5  221.13
  8414.5  221.13 8478.62     225 8518.62  251.75  8547.2251.6309  9551.5247.1586
 10101.6247.8342 17611.3 248.584 30102.2253.5927 30747.6253.5999 31169.3252.7551
34419.67  252.89 34912.8268.5219 35317.5287.366635549.23  281.3935689.17  292.15
#Mann= 20 ,-1 , 0
       0     .05       0  1089.5     .08       0  1629.9     .16       0
  2518.5     .16       0  3272.1     .05       0  4864.7     .05       0
  6100.2     .16       0  6578.3     .12       0  7027.4     .12       0
  8408.5     .05       0  8414.5     .05       0  8547.2     .12       0
  9551.5     .07       0 10101.6     .12       0 17611.3     .12       0
 30102.2     .05       0 30747.6     .05       0 31169.3     .12       0
 34912.8     .16       0 35317.5     .12       0
Bank Sta=8248.67,8518.62
XS Rating Curve= 0 ,0
Exp/Cntr=0.3,0.1

Type RM Length L Ch R = 1 ,522787  ,2424.15,2424.15,2424.15
XS GIS Cut Line= 3
3641592.9064814710702513.85535713629752.6289809610694076.3554999
3609979.3876876410688634.3952552
#Sta/Elev= 30
       0  310.41    99.7310.3226     340309.9868 1729.89  290.67  2933.8295.2218
  3127.9294.2453    3320297.4812  4580.5288.6503  4810.6 288.292  5643.2298.5186
  5893.4290.7127  6240.3274.2879  6635.8251.1456 7139.52  250.06 7229.51  221.13
  7299.2221.1416  7305.2221.1426 7369.51  224.42  7439.5  250.07  7446.2250.1191
19638.85  251.3520028.85  241.4720778.85  252.05 30005.5253.2375 30274.8252.0921
 30991.9251.877533668.84  252.91 34268.9261.9911 34500.7273.735435048.84  302.59
#Mann= 20 ,-1 , 0
       0     .05       0    99.7     .08       0     340     .05       0
  2933.8     .16       0  3127.9     .12       0    3320     .16       0
  4580.5     .05       0  4810.6     .16       0  5643.2     .16       0
  5893.4     .12       0  6240.3     .16       0  6635.8     .12       0
  7299.2     .05       0  7305.2     .05       0  7446.2     .12       0
 30005.5     .05       0 30274.8     .05       0 30991.9     .12       0
 34268.9     .16       0 34500.7     .12       0
Bank Sta=7139.52,7439.5
XS Rating Curve= 0 ,0
Exp/Cntr=0.3,0.1

Type RM Length L Ch R = 1 ,520363  ,2355.9,2355.9,2355.9
XS GIS Cut Line= 5
3642808.1842346310701472.18880533635898.4621617210696020.7997737
3634683.1844085510696159.68893163629960.9622257210693486.0778091
3611019.2684818810687662.1609792
#Sta/Elev= 30
       0  308.69    87.2  309.86  1654.7  296.83    4309  269.43    5126  269.08
  7032.8  268.06    8281  268.23  8975.9  272.41 9298.48  249.77 9353.06  228.74
    9370  220.27 9487.38  228.96  9536.1  241.92 9586.87  248.61 17249.7  247.54
 26516.6  246.28 28496.7  250.2529558.38  280.85 30488.4  277.27 31589.6  278.51
31867.93  290.3232277.85  273.67   32715   293.6 33104.9  306.5333867.76  302.53
34114.38  275.82   34173  288.55 34658.7  289.4934907.76  310.5735267.76  309.54
#Mann= 20 ,-1 , 0
       0      .1       0    87.2     .05       0  1654.7     .05       0
    4309     .16       0    5126     .05       0  7032.8     .12       0
    8281     .16       0  8975.9     .05       0 9353.06               0
 9487.38     .05       0  9536.1     .12       0 17249.7     .12       0
 26516.6     .12       0 28496.7     .12       0 30488.4     .05       0
 31589.6     .05       0   32715     .16       0 33104.9     .05       0
   34173     .05       0 34658.7     .05       0
Bank Sta=9298.48,9586.87
XS Rating Curve= 0 ,0
Exp/Cntr=0.3,0.1

Type RM Length L Ch R = 1 ,518007  ,1489,1489,1489
XS GIS Cut Line= 3
3643120.6842658110701124.96673073632252.6289022110692826.3553752
3615016.2798448110688371.8085101
#Sta/Elev= 30
       0  307.82    56.3  307.94     462  308.07   693.4  308.17  1983.4  297.67
 2478.94  276.04    4200  270.59    4321  269.43  5167.4  268.82  6376.6  268.78
  7102.1  270.15 9146.06  270.03 9455.93  248.3811065.27  249.9411132.74  228.57
   11150  219.9411267.26  228.57 11287.8   235.6 11291.8  240.8411311.57  250.72
19461.93  241.09 19791.8  251.37 28817.2  250.14 28971.5  251.18 29547.8  257.45
 29829.1  275.68 29930.3  283.21 30094.2  293.82 31043.4  300.8731477.23  299.58
#Mann= 22 ,-1 , 0
       0     .05       0    56.3     .16       0     462     .12       0
   693.4     .05       0  1983.4     .05       0    4200     .08       0
    4321     .16       0  5167.4     .05       0  6376.6     .05       0
  7102.1     .12       011132.74               011267.26     .05       0
 11287.8     .12       0 11291.8               011311.57     .12       0
 28817.2     .07       0 28971.5     .12       0 29547.8     .16       0
 29829.1     .12       0 29930.3     .16       0 30094.2     .05       0
 31043.4     .05       0
Bank Sta=11065.27,11311.57
XS Rating Curve= 0 ,0
Exp/Cntr=0.3,0.1

Type RM Length L Ch R = 1 ,516518  ,4093.61,4093.61,4093.61
XS GIS Cut Line= 4
3646940.1287266310700465.24429693635829.0177468110693729.1330972
3633259.5734106310691888.85560983615016.2798448110687903.0584633
#Sta/Elev= 30
       0   285.4  769.62  261.97    1024  270.79 1849.08  264.97  2608.1  289.39
 2928.55  269.46  3173.5  280.72  3527.3  291.78    5640  266.06  7629.8  267.13
  9278.7  266.42  9617.9  270.0411794.17  268.2612353.89  245.5113252.79  249.93
13362.46  246.94 13440.8  228.33   13458  219.73 13575.2  228.3313591.76  228.34
13621.67   250.5 16482.1  247.07   16841  247.48 28063.8  245.17 29179.6  246.47
   32348  251.33 32948.9   256.3 33193.7  266.34 33977.1  275.48 34826.7  294.04
#Mann= 19 ,-1 , 0
       0     .12       0    1024     .12       0  2608.1     .16       0
  3173.5     .16       0  3527.3     .05       0    5640     .05       0
  7629.8     .05       0  9278.7     .16       0  9617.9     .12       0
 13440.8               0 13575.2     .12       0 16482.1     .07       0
   16841     .12       0 28063.8     .12       0 29179.6     .12       0
   32348     .12       0 32948.9     .16       0 33193.7     .05       0
 33977.1     .05       0
Bank Sta=13252.79,13621.67
XS Rating Curve= 0 ,0
Exp/Cntr=0.3,0.1

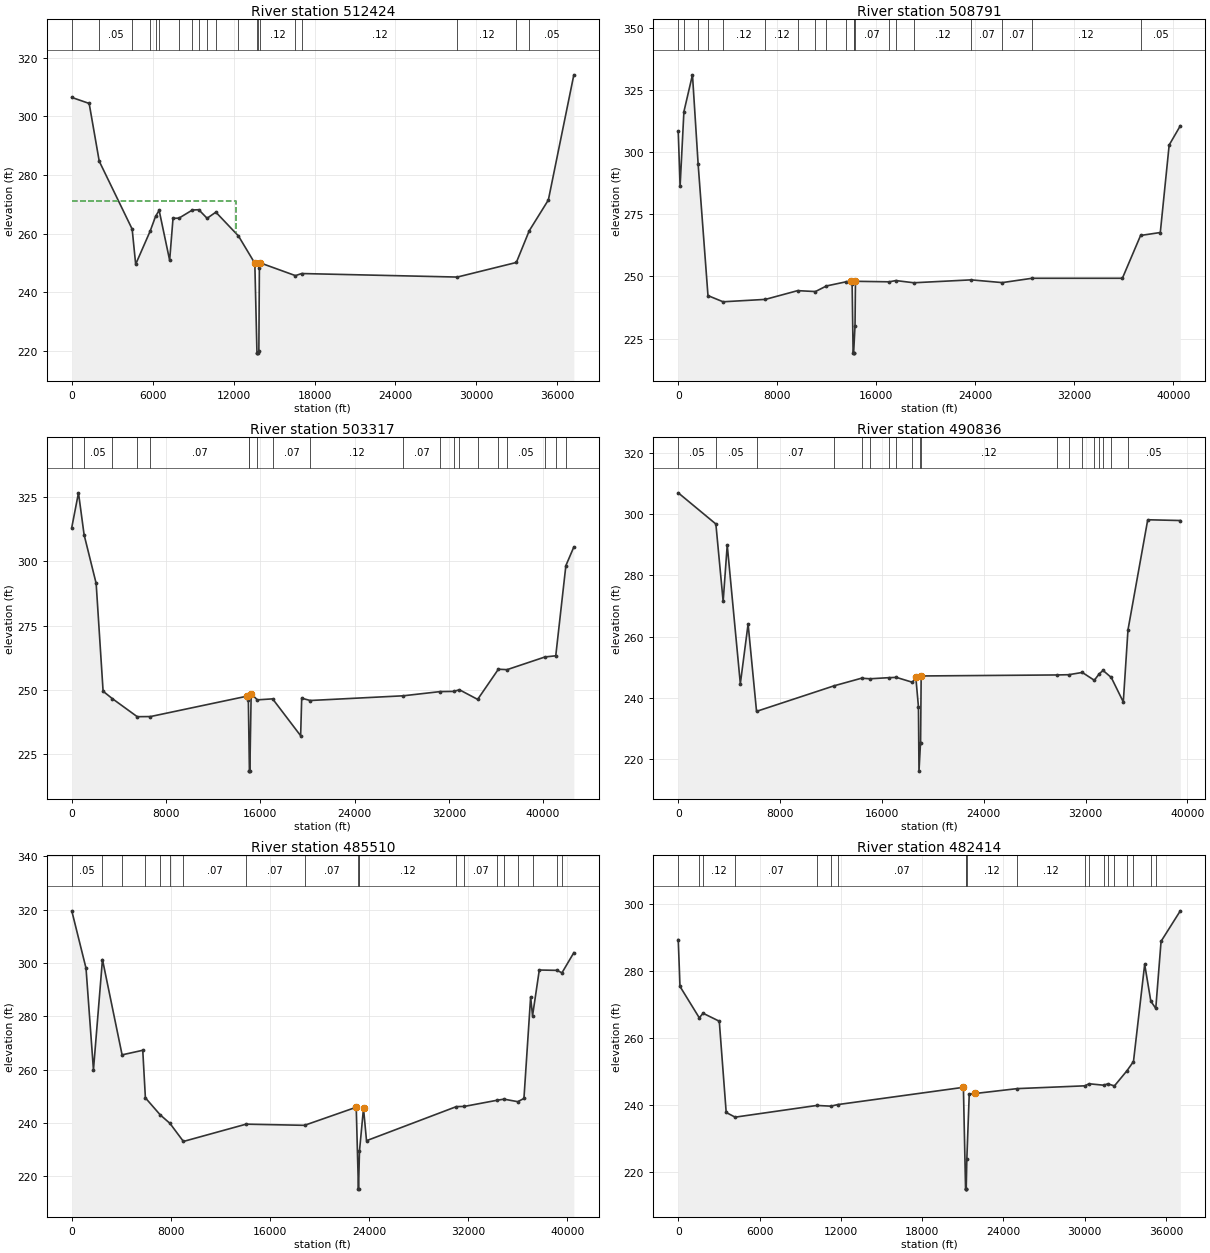
Type RM Length L Ch R = 1 ,512424  ,3633.25,3633.25,3633.25
XS GIS Cut Line= 4
3647886.3190914710699385.08307143637148.4622863810691923.5776532
3635829.0177468110691124.96671763613532.1873405610687379.7868721
#Sta/Elev= 30
       0  306.49 1289.58  304.44  2036.7284.7011  4477.8261.5181 4738.45  249.51
  5815.7260.8729  6210.6265.8317  6477.3267.9405 7257.62  250.87 7507.53   265.2
  7949.1265.2669  8941.3268.0312  9418.1268.1386 10033.8265.2153 10683.2267.3018
 12361.7259.161313573.39  249.8513732.59  219.16 13770.6  219.16 13776.6  219.16
 13871.9  219.81 13911.7  248.36 13934.5250.0474 16584.9 245.629 17048.9246.3437
 28586.7  245.14 32964.6 250.124 33920.4260.951135338.15  271.4637228.15  314.21
#Mann= 20 ,-1 , 0
       0     .05       0  2036.7     .05       0  4477.8     .12       0
  5815.7     .16       0  6210.6     .05       0  6477.3     .12       0
  7949.1     .12       0  8941.3     .12       0  9418.1     .12       0
 10033.8     .12       0 10683.2     .05       0 12361.7     .12       0
 13770.6     .05       0 13776.6     .05       0 13934.5     .12       0
 16584.9     .07       0 17048.9     .12       0 28586.7     .12       0
 32964.6     .12       0 33920.4     .05       0
#XS Ineff= 2 , 0
        12206.57  271.14
Permanent Ineff=
       F       F
Bank Sta=13573.39,13934.5
XS Rating Curve= 0 ,0
Exp/Cntr=0.3,0.1

Type RM Length L Ch R = 1 ,508791  ,5474.27,5474.27,5474.27
XS GIS Cut Line= 4
3652668.3256035610691903.26634213636696.1036110510688821.6691589
3627928.7422088110685132.43309913613220.5206410610686581.2635347
#Sta/Elev= 30
       0   308.4  149.97  286.25   458.4316.3103 1149.77  331.13  1608.1295.1649
  2402.9242.2988  3621.6239.8196  7039.9240.7841  9645.3244.2982   11083243.9366
   11976246.1871 13562.9247.863813937.28   248.114047.26  247.0314127.24  219.16
 14162.3219.1722 14168.3219.1743 14281.4230.161414317.21  248.06 17054.1247.8538
   17577 248.356 19030.3247.4708 23657.7248.6362 26175.7247.5341 28587.6249.2819
35879.38  249.28 37350.1266.500538942.87  267.6939659.38   302.940559.38  310.63
#Mann= 20 ,-1 , 0
       0     .16       0   458.4     .05       0  1608.1     .12       0
  2402.9     .07       0  3621.6     .12       0  7039.9     .12       0
  9645.3     .12       0   11083     .07       0   11976     .05       0
 13562.9     .07       0 14162.3     .05       0 14168.3     .05       0
 14281.4     .07       0 17054.1     .12       0   17577     .07       0
 19030.3     .12       0 23657.7     .07       0 26175.7     .07       0
 28587.6     .12       0 37350.1     .05       0
Bank Sta=13937.28,14317.21
XS Rating Curve= 0 ,0
Exp/Cntr=0.3,0.1

Type RM Length L Ch R = 1 ,503317  ,12480.91,12480.91,12480.91
XS GIS Cut Line= 3
3654496.0706357210689397.50330913624362.8612172210682601.4703132
3613142.3954692210685990.9858439
#Sta/Elev= 30
       0  313.02  569.82  326.48  1047.7310.1841 2069.33  291.33 2659.14  249.49
  3433.7246.6622  5556.6 239.621  6680.7239.672814887.35   247.614985.35  246.28
 15076.3218.5097 15082.3218.508115113.36   218.515225.28  248.54 15746.8 246.155
 17045.4246.539719423.74  232.2419513.71   246.8 20234.2245.9025 28141.8247.7325
 31260.6 249.358 32410.9249.4305   32899250.0696 34446.1246.3349 36204.9258.0397
 36945.6257.8738 40168.2262.8065 41075.2263.2509 41933.4 298.235 42610.1  305.48
#Mann= 20 ,-1 , 0
       0     .05       0  1047.7     .05       0  3433.7     .12       0
  5556.6     .07       0  6680.7     .07       0 15076.3     .05       0
 15082.3     .05       0 15746.8     .07       0 17045.4     .07       0
 20234.2     .12       0 28141.8     .07       0 31260.6     .07       0
 32410.9     .07       0   32899     .12       0 34446.1     .12       0
 36204.9     .05       0 36945.6     .05       0 40168.2     .05       0
 41075.2     .16       0 41933.4     .05       0
Bank Sta=14887.35,15225.28
XS Rating Curve= 0 ,0
Exp/Cntr=0.3,0.1

Type RM Length L Ch R = 1 ,490836  ,5326,5326,5326
XS GIS Cut Line= 4
 3654965.312151310683612.51356673638350.7289107110682362.5137701
3632113.9244552310682500.4485336 3616493.0898833 10677076.055183
#Sta/Elev= 30
       0  307.01  2956.6  296.81 3528.22  271.49 3848.06  289.92 4877.54  244.55
 5487.23   264.1  6150.2  235.52   12264  243.91   14400  246.37 15057.6  246.18
   16536  246.54 17131.4  246.64 18400.3  245.0318661.32  246.6618867.94     237
   18910  215.9719028.24  225.09 19035.5  225.0919081.24   247.1 29713.7  247.43
 30669.2  247.51 31737.6  248.25 32681.1  245.69 33058.4  247.75 33364.1  248.92
 34013.9   246.634957.71   238.6   35325  262.1636876.96   298.239435.96  297.95
#Mann= 20 ,-1 , 0
       0     .05       0  2956.6     .05       0  6150.2     .07       0
   12264     .07       0   14400     .05       0 15057.6     .07       0
   16536     .07       0 17131.4     .07       0 18400.3     .12       0
18867.94               019028.24     .05       0 19035.5     .12       0
 29713.7     .12       0 30669.2     .12       0 31737.6     .07       0
 32681.1     .07       0 33058.4     .12       0 33364.1     .07       0
 34013.9     .12       0   35325     .05       0
Bank Sta=18661.32,19081.24
XS Rating Curve= 0 ,0
Exp/Cntr=0.3,0.1

Type RM Length L Ch R = 1 ,485510  ,3096.08,3096.08,3096.08
XS GIS Cut Line= 3
3656897.4861084710680978.8318262 3627386.325970810678513.6694337
3616623.2982843110676772.2359087
#Sta/Elev= 30
       0  319.51 1149.76  298.01 1749.64  259.92  2476.8301.2687  4060.5265.5404
 5728.85  267.25  5941.1249.4256  7141.7243.0286  7920.6239.8725  9009.4 233.089
 14067.7239.5656   18782239.131422955.49  245.91 23133.8  215.22 23139.8  215.22
 23217.3229.498523542.55  245.5223785.32  233.37 31040.1246.1466 31668.1246.2042
 34280.5248.4887 34876.1248.9379 35992.1 247.99236489.43   249.2   37029  287.23
   37184280.178637728.46  297.33 39144.7297.2034 39557.9296.289340516.28  303.83
#Mann= 20 ,-1 , 0
       0     .05       0  2476.8     .05       0  4060.5     .05       0
  5941.1     .12       0  7141.7     .07       0  7920.6     .05       0
  9009.4     .07       0 14067.7     .07       0   18782     .07       0
 23133.8     .05       0 23139.8     .05       0 23217.3     .12       0
 31040.1     .12       0 31668.1     .07       0 34280.5     .07       0
 34876.1     .07       0 35992.1     .05       0   37184     .05       0
 39144.7     .16       0 39557.9     .05       0
Bank Sta=22955.49,23542.55
XS Rating Curve= 0 ,0
Exp/Cntr=0.3,0.1

Type RM Length L Ch R = 1 ,482414  ,3808.41,3808.41,3808.41
XS GIS Cut Line= 3
3654296.9092886310678247.93013583638832.3106247210676545.8528313
3617408.6996006410674740.2973873
#Sta/Elev= 30
       0  289.29  129.98  275.33  1554.5265.9663  1831.4267.3348 3029.61  264.96
 3539.54  237.75  4200.6236.3574 10233.8239.8485 11267.7239.6331 11763.4240.0983
21048.18  245.2521208.18   214.9 21248.1   214.9 21254.1   214.9 21302.1223.9014
21478.18  243.1621918.18  243.41 25026.6244.8681 30003.3 245.696 30326.7246.3104
 31413.6245.8762 31702.2246.2963 32194.2 245.669 33116.3250.1694 33601.2252.9429
34428.18  281.93 34880.6270.9542 35246.7268.773635638.18  288.7837058.18  297.87
#Mann= 20 ,-1 , 0
       0     .12       0  1554.5     .16       0  1831.4     .12       0
  4200.6     .07       0 10233.8     .07       0 11267.7     .07       0
 11763.4     .07       0 21248.1     .05       0 21254.1     .05       0
 21302.1     .12       0 25026.6     .12       0 30003.3     .07       0
 30326.7     .12       0 31413.6     .07       0 31702.2     .12       0
 32194.2     .05       0 33116.3     .16       0 33601.2     .05       0
 34880.6     .16       0 35246.7     .05       0
Bank Sta=21048.18,21918.18
XS Rating Curve= 0 ,0
Exp/Cntr=0.3,0.1