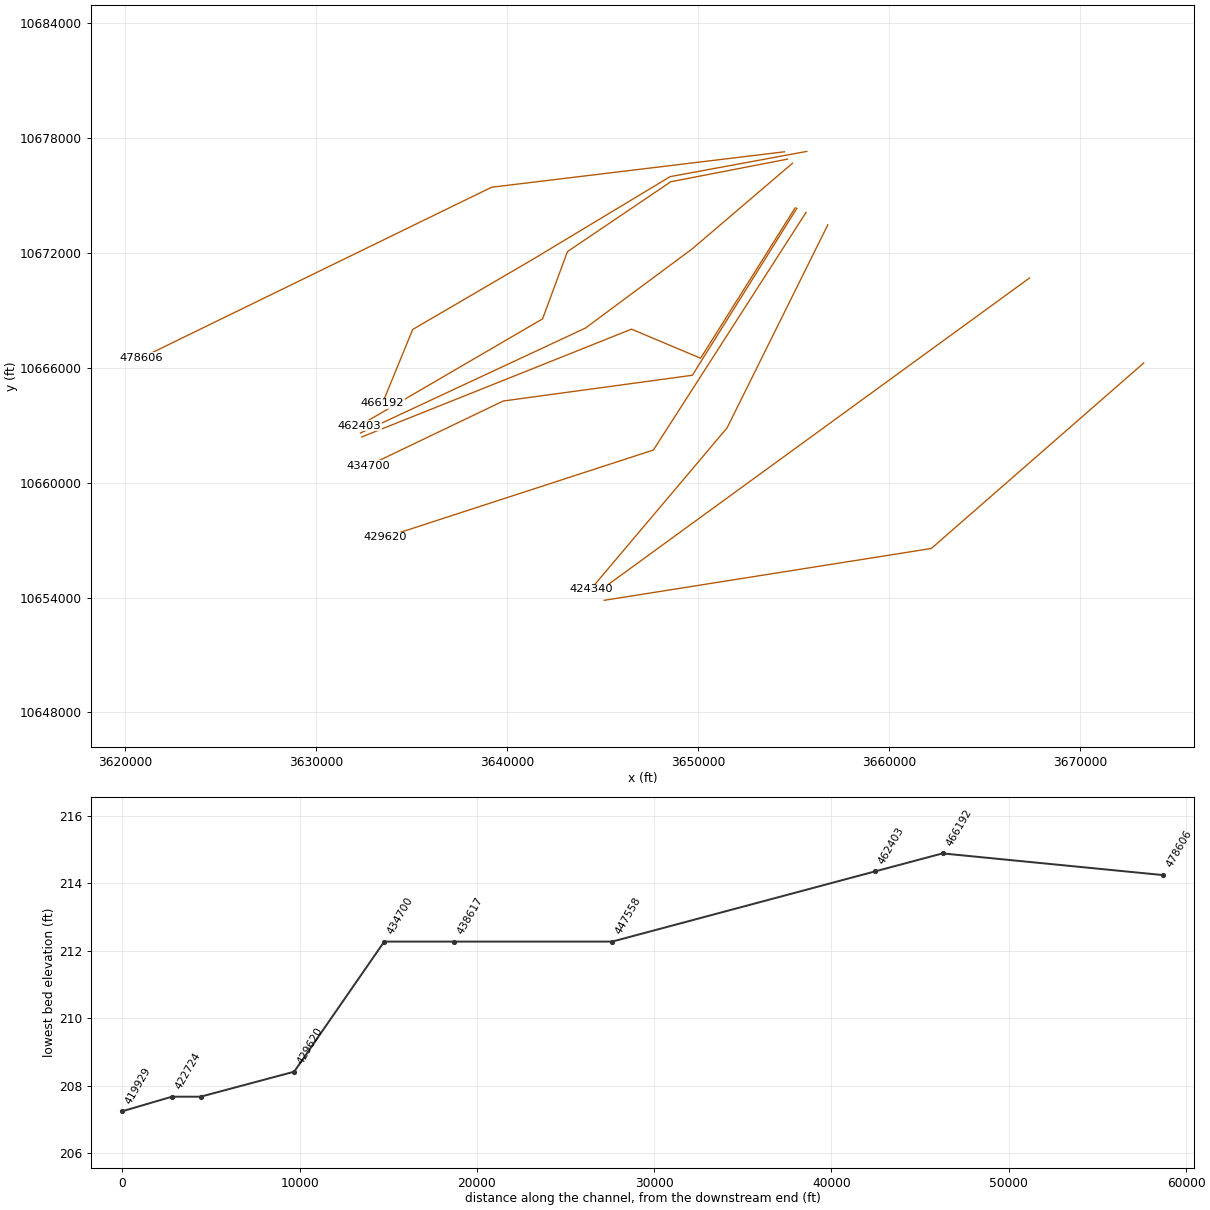
HEC-RAS study TRINITY RIVER.prj: TRINITY RIVER Base Level Engineering

--- TRINITY RIVER.g06 (geometry) --- (continued)

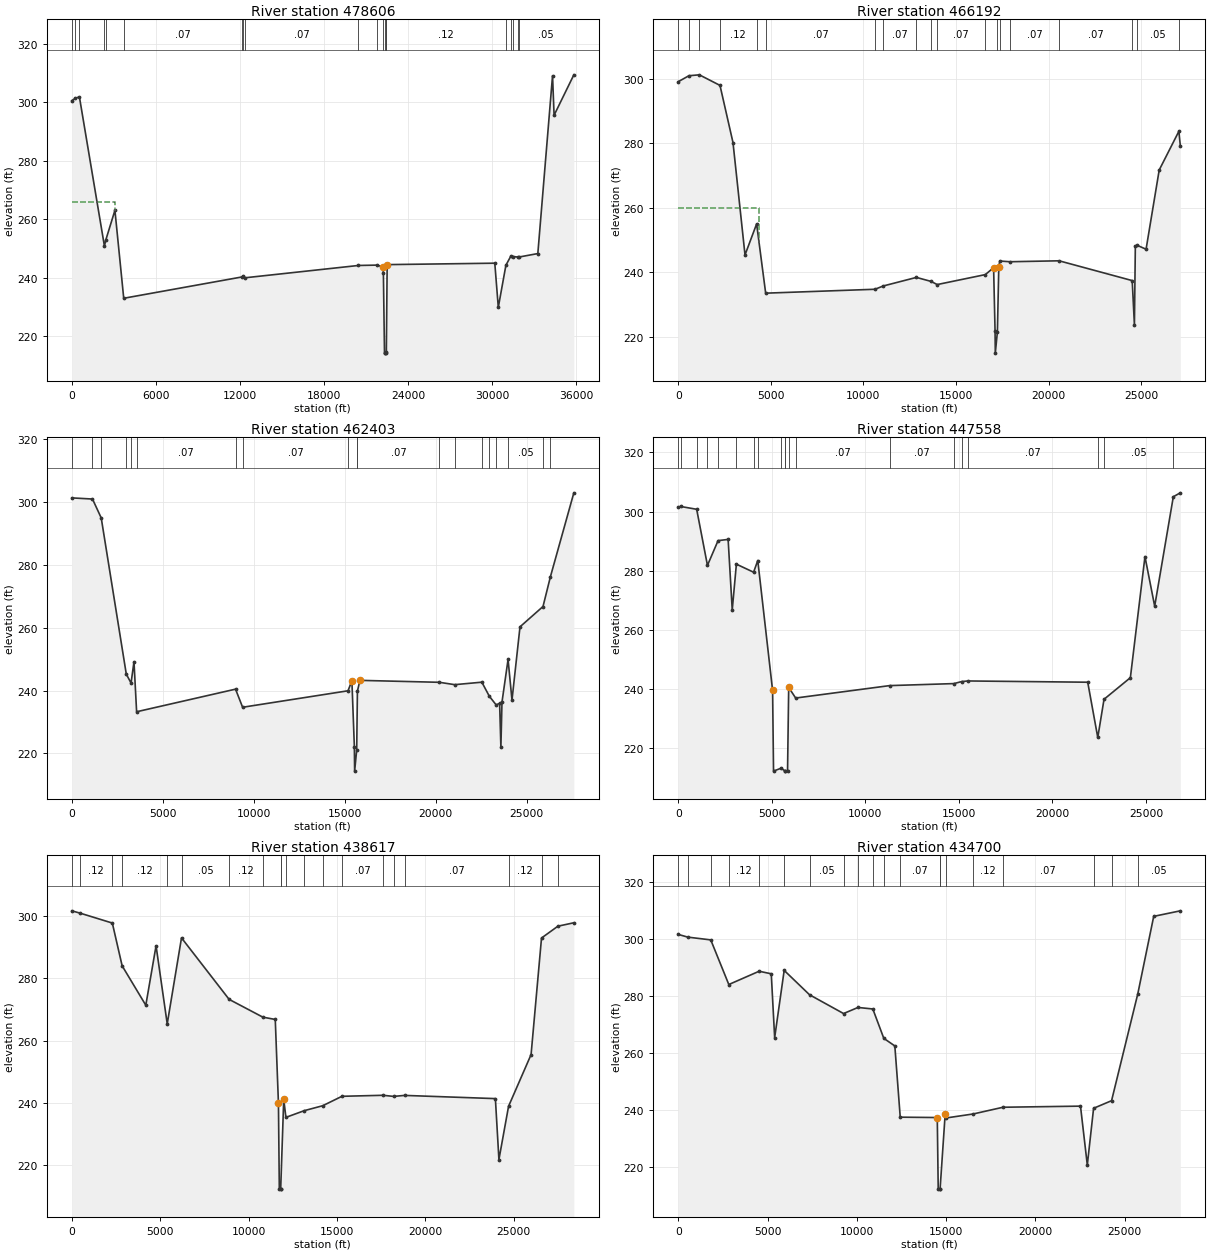
Type RM Length L Ch R = 1 ,478606  ,12413.91,12413.91,12413.91
XS GIS Cut Line= 3
 3654513.923290310677293.06918463639191.9303123110675441.8258399
3620858.4968348910666522.7048986
#Sta/Elev= 30
       0  300.58   246.8301.3748   544.4301.8875  2330.2250.8511  2429.4 252.946
 3078.68  263.08  3707.1233.0006 12151.6240.2982 12250.8 240.526   12350240.0016
 20456.9244.2221 21785.9244.341222203.11   243.7 22233.3241.6487 22313.1  214.24
 22379.3  214.24 22385.3  214.24 22444.2214.650122503.08  244.5130182.51     245
30432.49   229.9 30975.3244.3027 31319.8247.3563 31460.3247.2861 31835.7247.0983
 31878.1247.077133252.32  248.2934302.32  309.1234412.32   295.635822.32  309.42
#Mann= 20 ,-1 , 0
       0     .12       0   246.8     .16       0   544.4     .12       0
  2330.2     .16       0  2429.4     .12       0  3707.1     .07       0
 12151.6     .08       0 12250.8     .05       0   12350     .07       0
 20456.9     .07       0 21785.9     .12       0 22233.3     .05       0
 22379.3     .05       0 22385.3     .05       0 22444.2     .12       0
 30975.3     .07       0 31319.8     .07       0 31460.3     .05       0
 31835.7     .07       0 31878.1     .05       0
#XS Ineff= 2 , 0
         3067.29  265.95
Permanent Ineff=
       F       F
Bank Sta=22203.11,22503.08
XS Rating Curve= 0 ,0
Exp/Cntr=0.3,0.1

Type RM Length L Ch R = 1 ,466192  ,3789,3789,3789
XS GIS Cut Line= 5
3655683.1365030610677313.44676863648532.5287570510675994.7256527
3641283.8441074610671635.55195643635060.3066858110668008.6146565
3633474.7731114610664144.6453503
#Sta/Elev= 30
       0  299.08   576.6  300.93  1139.6  301.21  2254.4  297.93 2956.42  280.21
 3605.63  245.34  4232.7  254.97  4721.1  233.48 10624.2  234.69 11069.3  235.71
 12859.5  238.37 13649.3  237.13 13982.8  236.15 16580.5  239.2417028.34  241.38
17105.98  221.89   17120  214.8817233.32  221.5417308.07  241.61 17360.2  243.45
 17910.2  243.23   20564  243.52 24511.7  237.3824631.24  223.6424681.21  248.08
 24795.2  248.2925260.75  247.11 25970.2  271.69 27033.2  283.7127109.31  279.18
#Mann= 20 ,-1 , 0
       0     .12       0   576.6     .16       0  1139.6     .12       0
  2254.4     .12       0  4232.7     .12       0  4721.1     .07       0
 10624.2     .05       0 11069.3     .07       0 12859.5     .07       0
 13649.3     .05       0 13982.8     .07       0 16580.5     .12       0
17105.98               017233.32     .05       0 17360.2     .07       0
 17910.2     .07       0   20564     .07       0 24511.7     .12       0
 24795.2     .05       0 27033.2     .05       0
#XS Ineff= 2 , 0
          4366.2  259.89
Permanent Ineff=
       F       F
Bank Sta=17028.34,17308.07
XS Rating Curve= 0 ,0
Exp/Cntr=0.3,0.1

Type RM Length L Ch R = 1 ,462403  ,14844.7,14844.7,14844.7
XS GIS Cut Line= 5
3654674.4767749810676908.96660643648568.7275035510675728.8321556
3643158.8439663810672078.26038863641856.76094064 10668562.635202
3632264.0717927210662980.5617205
#Sta/Elev= 30
       0  301.38  1138.9  301.01  1618.5     295  2996.9  245.23  3258.2  242.41
 3419.33   249.2  3563.6  233.26  9000.1  240.46  9388.6  234.69 15182.2  239.94
15394.25  243.1615529.33  222.19   15545  214.3515658.47  221.09 15698.1  239.82
15835.83  243.26 20204.5  242.64 21044.7  241.89 22536.5  242.68 22946.1  238.21
 23323.8  235.4323512.58  235.9723582.57  221.9623642.56  236.33 23976.8  249.93
24192.24  236.9824632.37  260.31 25897.1  266.78   26307  276.3327591.79  302.99
#Mann= 20 ,-1 , 0
       0     .12       0  1138.9     .12       0  1618.5     .12       0
  2996.9     .05       0  3258.2     .12       0  3563.6     .07       0
  9000.1     .05       0  9388.6     .07       0 15182.2     .12       0
15529.33               015658.47     .05       0 15698.1     .07       0
 20204.5     .12       0 21044.7     .07       0 22536.5     .12       0
 22946.1     .07       0 23323.8     .12       0 23976.8     .05       0
 25897.1     .16       0   26307     .05       0
Bank Sta=15394.25,15835.83
XS Rating Curve= 0 ,0
Exp/Cntr=0.3,0.1

Type RM Length L Ch R = 1 ,447558  ,8940.69,8940.69,8940.69
XS GIS Cut Line= 4
3654935.07697555 10676695.0520083649691.6826067110672224.4572746
3644101.7436553810668083.94094943632329.6418715610662601.9643806
#Sta/Elev= 30
       0  301.55   127.3301.7461   985.3300.7942  1561.4281.8256  2128.2 290.195
 2666.34  290.61 2886.03  266.78  3107.6282.2447  4026.7279.5222    4251283.4773
 5043.07  239.54    5093  212.27  5495.7213.2579  5723.5  212.27  5729.5  212.27
 5841.98  212.27  5903.1240.5555  6276.1236.9813 11297.1241.1842 14735.2241.8644
 15143.6 242.545 15481.3242.755321884.22  242.33 22421.1223.6462 22755.5236.5607
24163.34  243.8624943.04   284.825462.84  268.03 26458.4305.0383 26832.3  306.36
#Mann= 20 ,-1 , 0
       0     .16       0   127.3     .12       0   985.3     .12       0
  1561.4     .12       0  2128.2     .12       0  3107.6     .12       0
  4026.7     .16       0    4251     .12       0  5495.7     .05       0
  5723.5     .05       0  5729.5     .05       0  5903.1     .12       0
  6276.1     .07       0 11297.1     .07       0 14735.2     .12       0
 15143.6     .07       0 15481.3     .07       0 22421.1     .12       0
 22755.5     .05       0 26458.4     .05       0
Bank Sta=5043.07,5903.1
XS Rating Curve= 0 ,0
Exp/Cntr=0.3,0.1

Type RM Length L Ch R = 1 ,438617  ,3917.3,3917.3,3917.3
XS GIS Cut Line= 4
3655073.8549132210674364.87655023650125.0701913810666507.0930532
3646509.9927758910668026.23502813632398.0134539810662394.8512777
#Sta/Elev= 30
       0  301.71   471.1300.9657  2294.2297.7798  2849.7284.0268 4188.34  271.37
 4768.11  290.48  5399.8265.3887  6207.5293.0195  8901.6273.2527 10809.9267.5378
11511.34   266.811690.94  239.8811740.83  212.27 11811.8  212.27 11817.8  212.27
11990.27  241.16 12112.9235.3286 13156.1237.4953 14195.6239.0748 15282.5242.1013
 17608.2242.4275 18203.4242.0709 18828.9242.390423963.33  241.3624163.25  221.78
 24708.7238.897325982.54  255.51 26572.8292.9707 27500.5296.772228401.59  297.87
#Mann= 20 ,-1 , 0
       0     .16       0   471.1     .12       0  2294.2     .16       0
  2849.7     .12       0  5399.8     .16       0  6207.5     .05       0
  8901.6     .12       0 10809.9     .12       0 11811.8     .05       0
 11817.8     .05       0 12112.9     .07       0 13156.1     .07       0
 14195.6     .12       0 15282.5     .07       0 17608.2     .07       0
 18203.4     .05       0 18828.9     .07       0 24708.7     .12       0
 26572.8     .05       0 27500.5     .05       0
Bank Sta=11690.94,11990.27
XS Rating Curve= 0 ,0
Exp/Cntr=0.3,0.1

Type RM Length L Ch R = 1 ,434700  ,5080.39,5080.39,5080.39
XS GIS Cut Line= 4
3655164.9649672210674341.68040243649696.2150779710665617.7218005
3639800.3815232210664272.23597443632741.1823870510660894.2141871
#Sta/Elev= 30
       0  301.61   537.2300.6528  1820.9299.6857  2831.2284.0346  4529.4288.6897
 5208.16  287.79  5398.1  265.38  5931.1288.9878    7351280.4397  9255.8273.8544
 10064.7275.9894 10893.6275.4539   11509265.154512125.83  262.49 12428.3237.5066
14502.33  237.3814555.11  212.27 14653.1  212.27 14659.1  212.27   14945  238.66
 14979.9237.2113 16516.1238.6358 18181.8240.988322520.38  241.3822901.52  220.73
 23253.4240.6219 24259.7243.2893 25726.6280.723226619.34  307.9428108.46  309.88
#Mann= 20 ,-1 , 0
       0     .05       0   537.2     .12       0  1820.9     .12       0
  2831.2     .12       0  4529.4     .16       0  5931.1     .05       0
    7351     .05       0  9255.8     .05       0 10064.7     .12       0
 10893.6     .16       0   11509     .05       0 12428.3     .07       0
 14653.1     .05       0 14659.1     .05       0 14979.9     .07       0
 16516.1     .12       0 18181.8     .07       0 23253.4     .12       0
 24259.7     .05       0 25726.6     .05       0
Bank Sta=14502.33,14945
XS Rating Curve= 0 ,0
Exp/Cntr=0.3,0.1

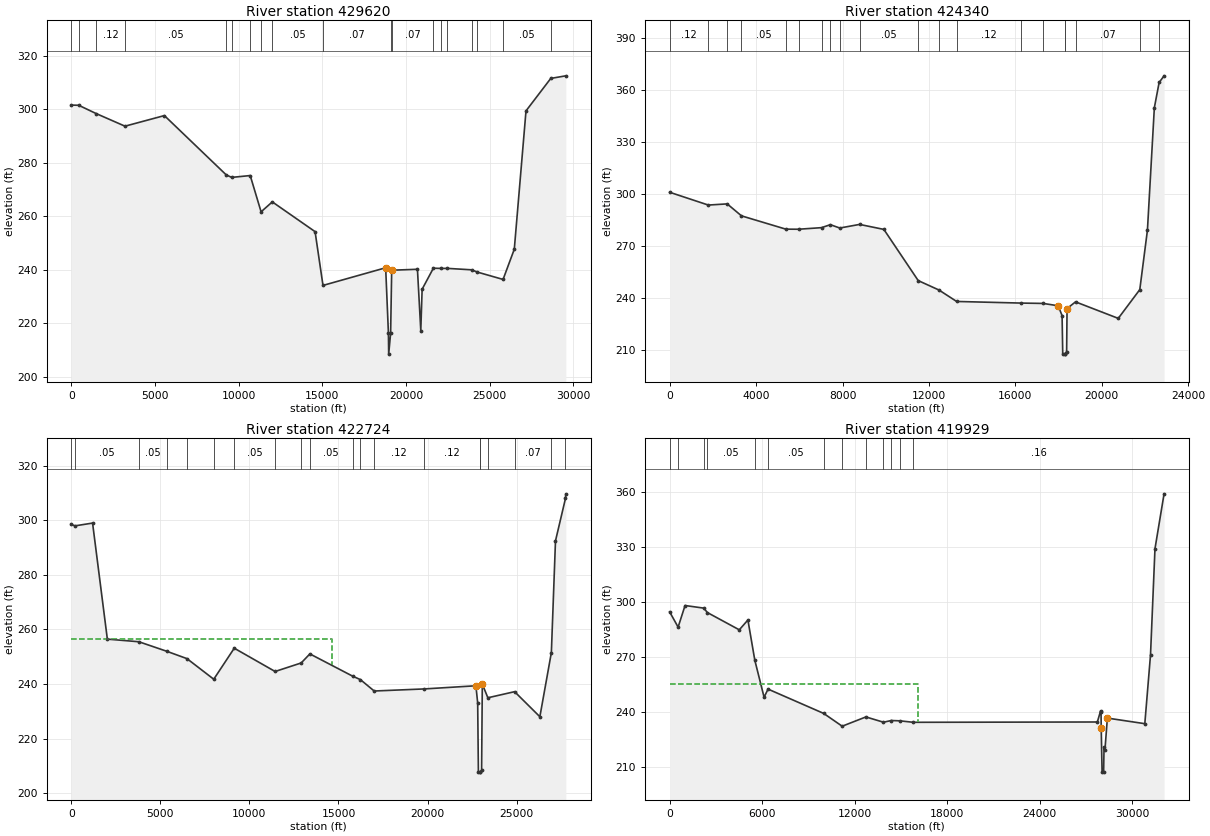
Type RM Length L Ch R = 1 ,429620  ,5280,5280,5280
XS GIS Cut Line= 3
 3655642.395442810674124.66640073647656.2844465510661711.4720671
3633598.40836288  10657145.66591
#Sta/Elev= 30
       0  301.64   437.2  301.58    1474  298.49  3202.6  293.75 5556.33  297.72
  9251.4  275.52  9578.2  274.58 10684.7  275.27 11334.4  261.69 12005.2  265.41
14560.23  254.27 15032.9  234.1418777.67  240.7518942.36  216.24   18958  208.42
 19073.6  216.22 19137.7  239.8320676.56  240.1820876.44  217.26 20956.4  232.72
 21628.4  240.59 22094.6   240.5 22470.8  240.52 23916.4  239.98 24239.5  239.16
 25792.7  236.3826463.17  247.6927162.76  299.48 28641.9  311.6329541.36   312.6
#Mann= 20 ,-1 , 0
       0     .12       0   437.2     .16       0    1474     .12       0
  3202.6     .05       0  9251.4     .05       0  9578.2     .16       0
 10684.7     .05       0 11334.4     .16       0 12005.2     .05       0
 15032.9     .07       018942.36               0 19073.6     .05       0
 19137.7     .07       0 21628.4     .05       0 22094.6     .05       0
 22470.8     .05       0 23916.4     .05       0 24239.5     .07       0
 25792.7     .05       0 28641.9     .05       0
Bank Sta=18777.67,19137.7
XS Rating Curve= 0 ,0
Exp/Cntr=0.3,0.1

Type RM Length L Ch R = 1 ,424340  ,1616.17,1616.17,1616.17
XS GIS Cut Line= 3
 3656782.528989310673477.36454573651513.8728599710662872.5055061
3644386.8611953910654444.7375848
#Sta/Elev= 30
       0  300.89  1790.4293.5203  2663.5294.1934  3324.5287.3037  5377.1 279.649
  5966.5279.6004  7028.6280.5114  7437.1282.2238  7872.9280.2928  8789.4282.3755
 9912.92   279.5 11502.7250.0211 12463.1244.5968 13279.4238.0137 16264.2237.0794
 17283.6236.871417980.29  235.5318160.26  229.8518190.25  207.68   18273  207.68
   18279  207.6818370.21  209.1918390.21  233.94 18782.7237.775320759.75  228.27
 21755.8244.831222109.48  279.0722429.42  349.57 22650.7364.099222879.33  367.94
#Mann= 20 ,-1 , 0
       0     .12       0  1790.4     .05       0  2663.5     .05       0
  3324.5     .05       0  5377.1     .05       0  5966.5     .05       0
  7028.6     .12       0  7437.1     .05       0  7872.9     .05       0
  8789.4     .05       0 11502.7     .12       0 12463.1     .05       0
 13279.4     .12       0 16264.2     .07       0 17283.6     .12       0
   18273     .05       0   18279     .05       0 18782.7     .07       0
 21755.8     .12       0 22650.7     .05       0
Bank Sta=17980.29,18390.21
XS Rating Curve= 0 ,0
Exp/Cntr=0.3,0.1

Type RM Length L Ch R = 1 ,422724  ,2794.83,2794.83,2794.83
XS GIS Cut Line= 2
3667338.0843217210670699.5866367 3644872.806745810654380.1422416
#Sta/Elev= 30
       0  298.43   207.7 297.938 1189.88  298.95 2019.79  256.42  3787.6 255.462
  5345.3251.9948    6491249.2747  7995.2 241.726  9146.6253.0956 11440.5244.5629
 12904.9247.6843 13394.6251.0055 15791.6242.8645 16235.1 241.569 17005.1 237.408
 19807.1238.164822717.94  239.3322817.94  233.0222857.93  207.68 22937.4  207.68
 22943.4  207.6823037.92   208.323077.92  239.95 23389.5234.9284 24891.5237.1655
26310.35  227.98 26955.9251.482627187.64  292.43 27748.3307.9636 27767.6  309.67
#Mann= 20 ,-1 , 0
       0     .08       0   207.7     .05       0  3787.6     .05       0
  5345.3     .12       0    6491     .05       0  7995.2     .05       0
  9146.6     .05       0 11440.5     .12       0 12904.9     .12       0
 13394.6     .05       0 15791.6     .12       0 16235.1     .05       0
 17005.1     .12       0 19807.1     .12       0 22937.4     .05       0
 22943.4     .05       0 23389.5     .07       0 24891.5     .07       0
 26955.9     .12       0 27748.3     .16       0
#XS Ineff= 2 , 0
        14624.41  256.43
Permanent Ineff=
       F       F
Bank Sta=22717.94,23077.92
XS Rating Curve= 0 ,0
Exp/Cntr=0.3,0.1

Type RM Length L Ch R = 1 ,419929  ,4761.14,4761.14,4761.14
XS GIS Cut Line= 3
3673310.3066292310666255.14244163662199.1956493910656567.6421316
3645081.1399905510653859.3089656
#Sta/Elev= 30
       0  294.69   549.4  286.35  999.41  298.14  2206.1  296.73  2451.3  294.29
 4517.31  284.88 5076.98  290.24  5524.8  268.29 6126.35  248.09  6382.7  252.54
  9991.6  239.28 11191.3   232.3 12730.2  237.36 13870.1  234.48 14384.2  235.41
 14941.6  235.23 15806.1  234.4327743.81   234.627953.69  240.6527983.67  240.15
27993.66  231.41   28050  207.25   28150  207.2528177.23  220.8628233.52   219.1
28393.43  236.7330822.01  233.6831191.79  271.1931481.62  329.1232071.27  359.07
#Mann= 13 ,-1 , 0
       0     .16       0   549.4     .05       0  2206.1     .12       0
  2451.3     .05       0  5524.8     .05       0  6382.7     .05       0
  9991.6     .05       0 11191.3     .05       0 12730.2     .12       0
 13870.1     .05       0 14384.2     .16       0 14941.6     .12       0
 15806.1     .16       0
#XS Ineff= 2 , 0
        16130.67  255.06
Permanent Ineff=
       F       F
Bank Sta=27993.66,28393.43
XS Rating Curve= 0 ,0
Exp/Cntr=0.3,0.1