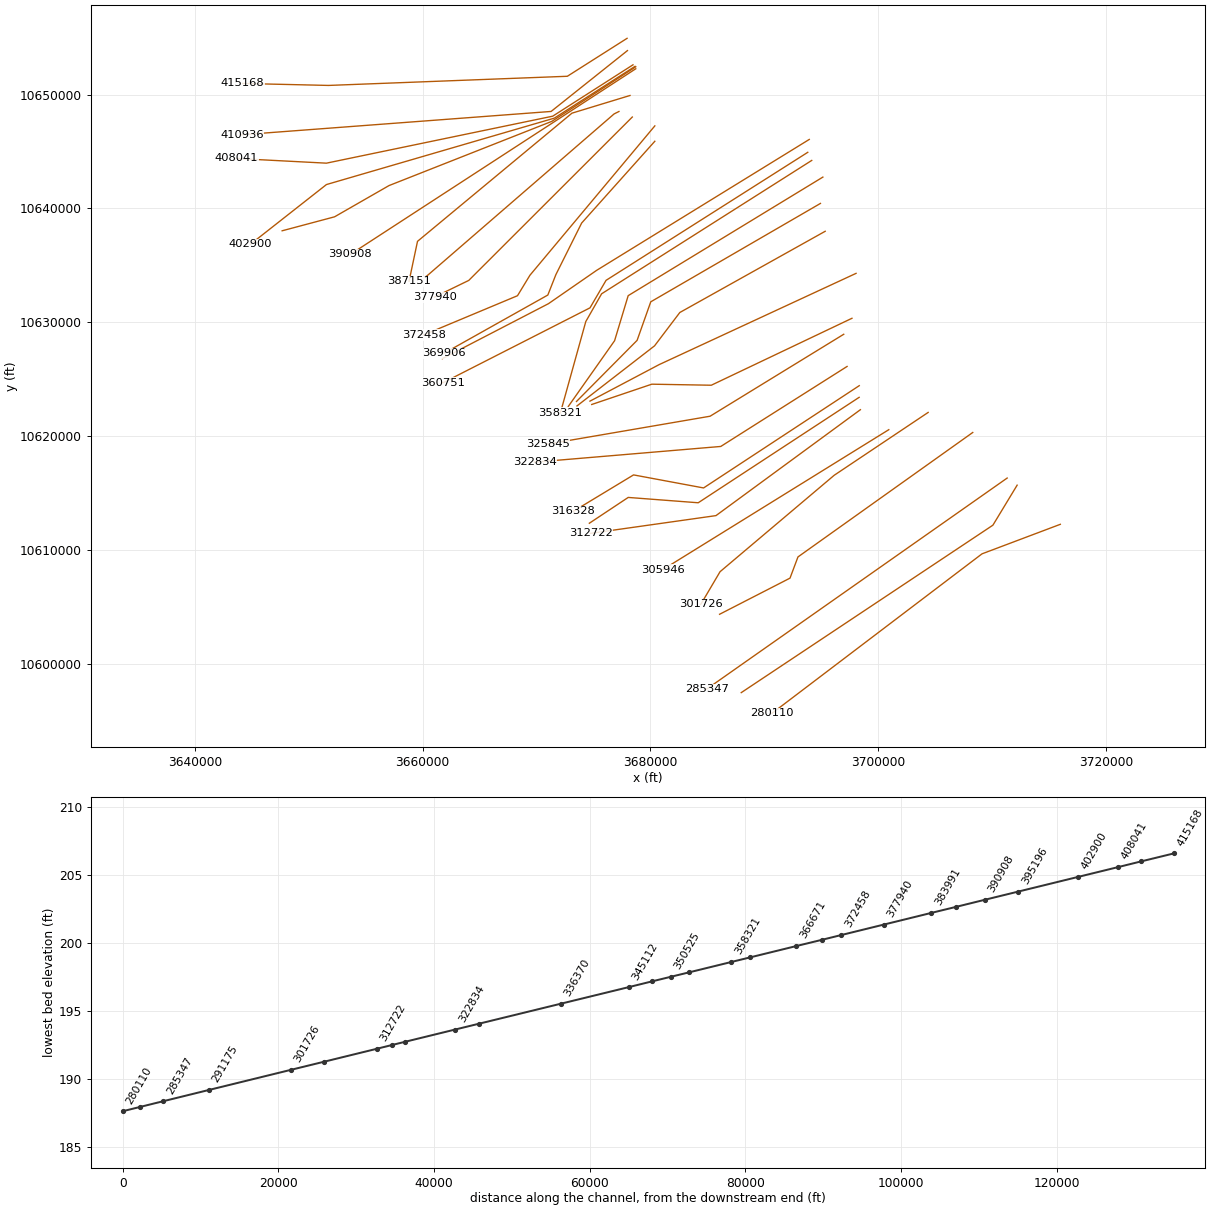
HEC-RAS study TRINITY RIVER.prj: TRINITY RIVER Base Level Engineering

--- TRINITY RIVER.g06 (geometry) --- (continued)

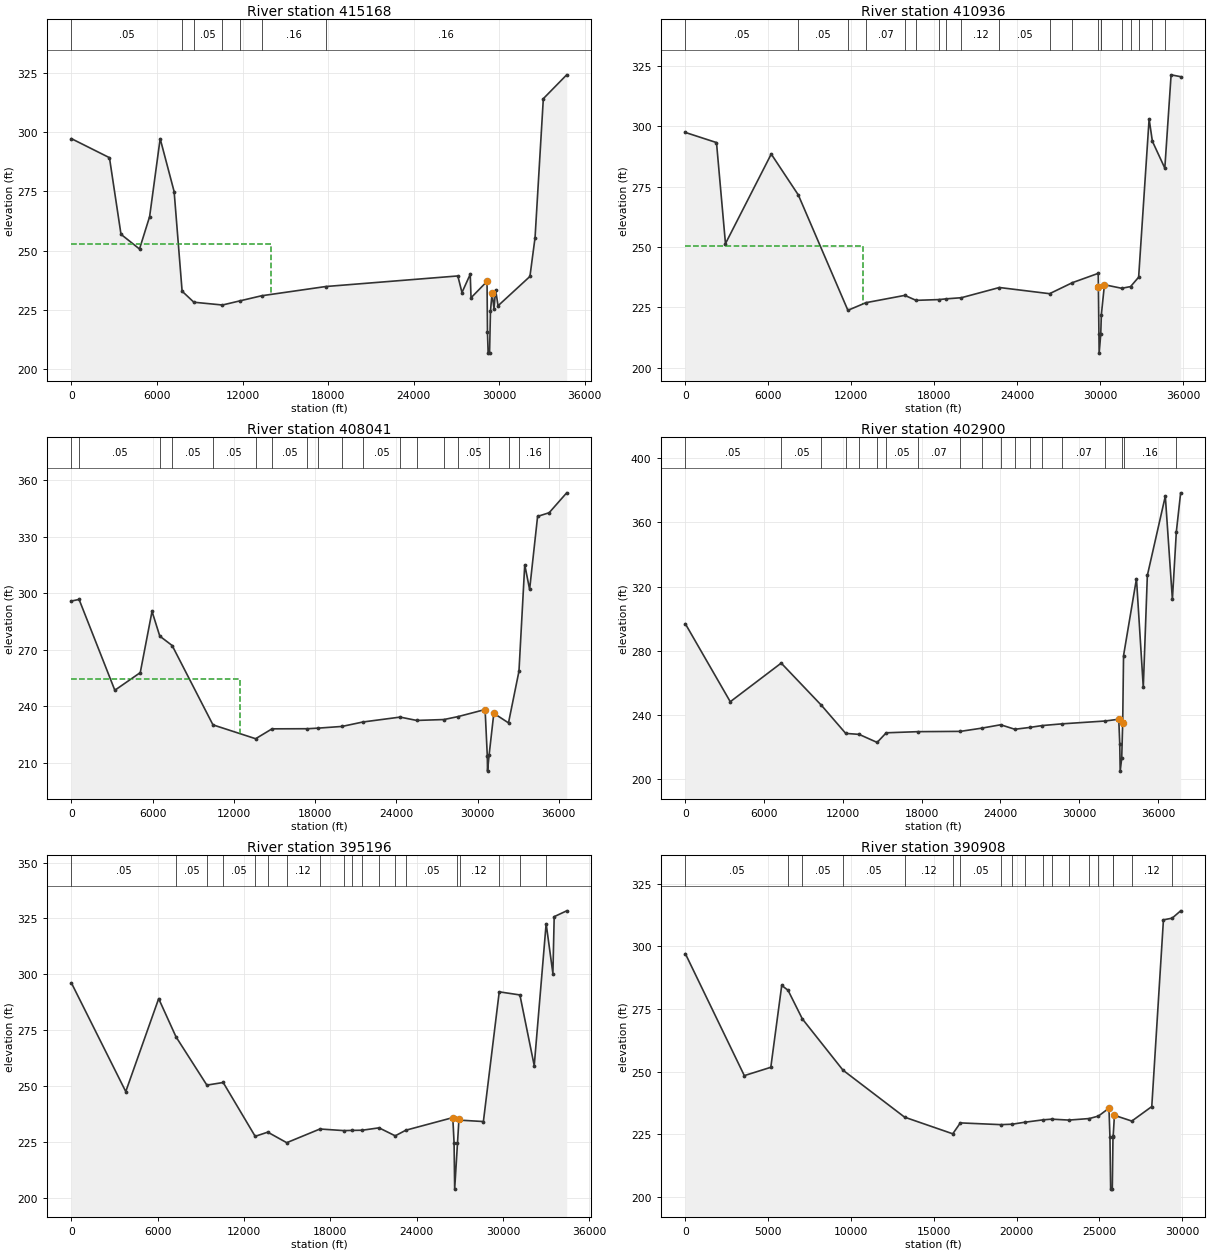
Type RM Length L Ch R = 1 ,415168  ,4231.92,4231.92,4231.92
XS GIS Cut Line= 4
3677950.9315343110654947.85075183672707.8760755510651614.5171954
 3651756.210301810650809.8537785 3644204.126980810650983.4646517
#Sta/Elev= 30
       0  297.33 2666.97  289.28 3476.05  256.86 4774.58  250.64 5483.78  264.35
 6222.95  297.33 7202.83  274.94  7762.4  232.78  8586.1  228.12 10590.6  226.94
 11847.2  228.74 13334.8  230.85 17835.4  234.7627099.34  239.2427389.16  232.21
27968.71  239.9528023.63  229.9929147.79  236.9429177.76  215.45   29224  206.58
   29324  206.58 29387.6  224.2429497.51  231.99 29637.4  225.4529747.32  233.37
29920.15  226.6232155.43  239.0332515.15  255.47 33094.7  314.2534733.42  324.34
#Mann= 7 ,-1 , 0
       0     .05       0  7762.4     .12       0  8586.1     .05       0
 10590.6     .05       0 11847.2     .05       0 13334.8     .16       0
 17835.4     .16       0
#XS Ineff= 2 , 0
        14021.91  252.72
Permanent Ineff=
       F       F
Bank Sta=29147.79,29497.51
XS Rating Curve= 0 ,0
Exp/Cntr=0.3,0.1

Type RM Length L Ch R = 1 ,410936  ,2895.19,2895.19,2895.19
XS GIS Cut Line= 3
3677985.6539058110653871.46182853671284.2650776410648524.2395833
3644131.4870342210646475.6285231
#Sta/Elev= 30
       0  297.39 2248.25   293.2 2897.74  251.36 6205.14  288.45  8161.8  271.52
 11747.8  223.73 13057.5  226.89 15862.3  229.91 16672.9  227.85 18335.5  228.17
 18863.5  228.48 19950.4  228.94 22700.1  233.17 26327.6  230.61 27981.9  235.19
29844.91  239.0329855.99   233.529895.36  213.81   29911  205.9930026.62   213.8
   30072  221.9730293.28  234.32 31541.1  232.85 32182.3  233.55   32766  237.44
33523.28  302.98 33759.5  293.75 34658.8  282.6135113.28  321.2635803.28  320.49
#Mann= 22 ,-1 , 0
       0     .05       0  8161.8     .05       0 11747.8     .05       0
 13057.5     .07       0 15862.3     .07       0 16672.9     .07       0
 18335.5     .05       0 18863.5     .07       0 19950.4     .12       0
 22700.1     .05       0 26327.6     .05       0 27981.9     .05       0
29844.91               029855.99     .05       029895.36               0
30026.62     .05       0   30072     .12       0 31541.1     .07       0
 32182.3     .12       0   32766     .16       0 33759.5     .16       0
 34658.8     .16       0
#XS Ineff= 2 , 0
        12832.55   250.2
Permanent Ineff=
       F       F
Bank Sta=29855.99,30293.28
XS Rating Curve= 0 ,0
Exp/Cntr=0.3,0.1

Type RM Length L Ch R = 1 ,408041  ,5140.85,5140.85,5140.85
XS GIS Cut Line= 4
3678471.7648102210652621.46170383671423.1539074610648107.5727657
3651559.87243989 10643980.1135013643645.3761298110644392.2950913
#Sta/Elev= 30
       0   295.8   565.3  296.65  3206.2  248.48 5083.96  257.83 5952.92  290.32
  6526.5   277.2  7441.2   272.2 10454.5  230.12 13606.7  222.77 14816.8  228.01
 17428.5  228.07 18196.1  228.37 19989.9  229.29 21526.7  231.64 24279.7  234.24
 25503.1  232.47 27511.1  232.94 28572.8  234.5330555.83  238.2530719.26  213.45
   30735  205.5830852.17  214.1731199.05  236.25 32284.1  231.18 33057.1  258.57
 33484.1  315.0633843.89  301.9634433.54   340.7   35287  342.6436582.25   353.2
#Mann= 20 ,-1 , 0
       0     .05       0   565.3     .05       0  6526.5     .05       0
  7441.2     .05       0 10454.5     .05       0 13606.7     .07       0
 14816.8     .05       0 17428.5     .07       0 18196.1     .07       0
 19989.9     .12       0 21526.7     .05       0 24279.7     .05       0
 25503.1     .05       0 27511.1     .12       0 28572.8     .05       0
30719.26               030852.17     .05       0 32284.1     .12       0
 33057.1     .16       0   35287     .16       0
#XS Ineff= 2 , 0
        12456.96  254.49
Permanent Ineff=
       F       F
Bank Sta=30555.83,31199.05
XS Rating Curve= 0 ,0
Exp/Cntr=0.3,0.1

Type RM Length L Ch R = 1 ,402900  ,7704.29,7704.29,7704.29
XS GIS Cut Line= 4
3678645.37601155 10652482.5728743671562.0427373110647933.9618925
3651562.0427111410642100.62841483644895.3759263910636857.5729561
#Sta/Elev= 30
       0  296.73  3419.2  248.15    7300  272.25 10362.9  245.92 12214.5  228.39
 13233.5  227.79 14606.9  222.77 15302.1  228.77 17717.3  229.48 20953.1  229.66
 22585.5  231.68 24018.6  233.78 25098.7  230.97 26231.6  232.11 27175.2  233.28
 28722.8  234.37 31984.1  236.1333016.83  237.2333090.63  222.05   33125  204.86
 33241.1  212.9133316.48  235.13 33380.8  276.8934365.25  324.9134884.65  257.09
35194.29  326.9436562.69  376.3937102.06  311.99 37402.8  354.1737731.32  378.46
#Mann= 20 ,-1 , 0
       0     .05       0    7300     .05       0 10362.9     .05       0
 12214.5     .12       0 13233.5     .07       0 14606.9     .07       0
 15302.1     .05       0 17717.3     .07       0 20953.1     .05       0
 22585.5     .05       0 24018.6     .05       0 25098.7     .05       0
 26231.6     .05       0 27175.2     .05       0 28722.8     .07       0
 31984.1     .05       033090.63               0 33241.1     .05       0
 33380.8     .16       0 37402.8     .16       0
Bank Sta=33016.83,33316.48
XS Rating Curve= 0 ,0
Exp/Cntr=0.3,0.1

Type RM Length L Ch R = 1 ,395196  ,4287.94,4287.94,4287.94
XS GIS Cut Line= 5
3678714.8204264610652447.85050253671353.7094925510647656.1839047
3657054.1855982210642010.91009033652274.8778996310639265.7334941
3647673.1538353910638038.1283377
#Sta/Elev= 30
       0  296.08 3777.12  247.45 6065.36  289.07  7270.5  271.96    9416  250.35
   10551  251.52 12774.5  227.42 13647.8  229.29 14968.4  224.57 17277.7   230.7
 18949.2  229.98 19478.6  230.07 20214.5  230.15   21385  231.22   22511  227.64
 23244.3  230.15 26513.4   235.8 26602.2  224.43 26643.5  203.7826839.78  224.42
26942.73   235.2 26979.1  234.6728640.07  234.04 29742.1  292.11 31178.6  290.72
32174.54  259.06 33002.8  322.6333472.51  300.2833562.37  325.7734431.01  328.38
#Mann= 20 ,-1 , 0
       0     .05       0  7270.5     .05       0    9416     .05       0
   10551     .05       0 12774.5     .12       0 13647.8     .12       0
 14968.4     .12       0 17277.7     .07       0 18949.2     .07       0
 19478.6     .05       0 20214.5     .05       0   21385     .05       0
   22511     .05       0 23244.3     .05       0 26602.2               0
26839.78     .05       0 26979.1     .12       0 29742.1     .05       0
 31178.6     .16       0 33002.8     .16       0
Bank Sta=26513.4,26942.73
XS Rating Curve= 0 ,0
Exp/Cntr=0.3,0.1

Type RM Length L Ch R = 1 ,390908  ,3756.97,3756.97,3756.97
XS GIS Cut Line= 2
3678714.8204264610652274.23962923653645.37614289 10635954.794906
#Sta/Elev= 30
       0  297.04 3559.19  248.44 5158.84  251.76  5818.7   284.4  6198.7  282.48
  7063.9  271.06  9517.8  250.62 13242.1  231.87 16149.1  225.24 16606.9  229.59
 19055.6  228.89   19747  229.07 20483.2  229.84 21622.1  230.82 22123.8  231.08
 23168.3  230.71 24403.4  231.33 24948.1  232.3225584.56  235.4625643.77  223.79
   25685  203.18   25785  203.18 25826.2  223.78 25839.5  224.48 25914.5  232.61
 26963.4  230.3228169.79   236.128873.92  310.56 29398.7  311.2229913.72  314.15
#Mann= 20 ,-1 , 0
       0     .05       0  6198.7     .05       0  7063.9     .05       0
  9517.8     .05       0 13242.1     .12       0 16149.1     .05       0
 16606.9     .05       0 19055.6     .07       0   19747     .07       0
 20483.2     .05       0 21622.1     .07       0 22123.8     .05       0
 23168.3     .07       0 24403.4     .05       0 24948.1     .05       0
25643.77               0 25826.2     .05       0 25839.5     .12       0
 26963.4     .12       0 29398.7     .12       0
Bank Sta=25584.56,25914.5
XS Rating Curve= 0 ,0
Exp/Cntr=0.3,0.1

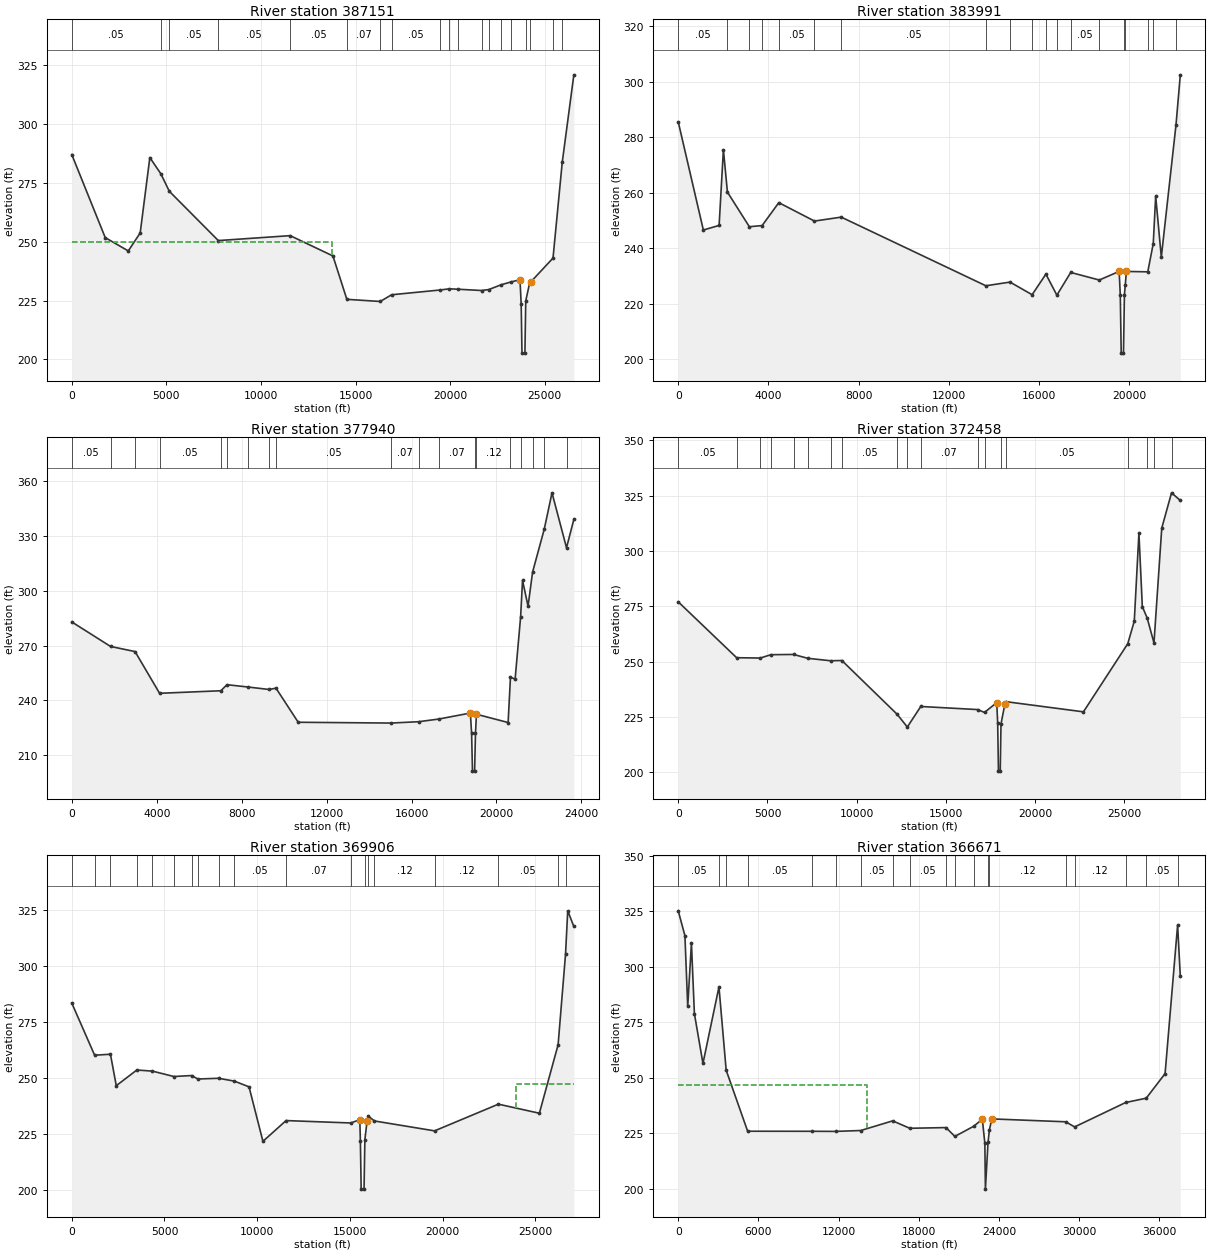
Type RM Length L Ch R = 1 ,387151  ,3159.98,3159.98,3159.98
XS GIS Cut Line= 4
3678209.1780650510649926.29386583673115.0786732110648374.1752509
3659555.1172761310637111.00092693658813.8120002210633602.1946243
#Sta/Elev= 30
       0  287.01 1768.44  251.72 2987.37  246.06 3616.82   253.7 4126.37  285.71
    4703   278.9  5156.8  271.39  7744.9  250.46   11546  252.5513804.28  243.93
 14540.9   225.5 16305.2  224.59 16906.1  227.44 19476.1  229.47 19953.7  229.97
   20421  229.79 21662.5  229.25 22042.4  229.65 22694.5  231.68   23198  232.84
23691.98  233.8423755.86  223.47 23797.5  202.65 23952.5  202.6523996.91  224.86
 24218.9  233.0524278.22  233.03 25438.1  243.02 25927.1  283.77 26539.2  320.86
#Mann= 20 ,-1 , 0
       0     .05       0    4703     .08       0  5156.8     .05       0
  7744.9     .05       0   11546     .05       0 14540.9     .07       0
 16305.2     .05       0 16906.1     .05       0 19476.1     .07       0
 19953.7     .05       0   20421     .05       0 21662.5     .05       0
 22042.4     .07       0 22694.5     .05       0   23198     .05       0
23755.86               023996.91     .05       0 24218.9     .05       0
 25438.1     .16       0 25927.1     .16       0
#XS Ineff= 2 , 0
        13755.87  249.95
Permanent Ineff=
       F       F
Bank Sta=23691.98,24278.22
XS Rating Curve= 0 ,0
Exp/Cntr=0.3,0.1

Type RM Length L Ch R = 1 ,383991  ,6050.57,6050.57,6050.57
XS GIS Cut Line= 4
 3677238.291227310648519.72909363676814.4449621310648307.9995302
 3660369.4450438 10634062.9994773660332.4894090610634041.0877754
#Sta/Elev= 30
       0  285.59 1113.69   246.6 1813.59  248.24 2003.57  275.53    2182  260.26
    3155  247.78  3722.4   248.2  4461.5  256.46  6042.8  249.82  7231.7  251.24
 13648.2  226.49 14718.7  227.82 15699.2  223.27 16310.1  230.69 16796.9  223.11
 17412.2   231.3 18678.6  228.56 19560.9  231.6819610.22   223.1   19652  202.21
   19752  202.21   19794  223.21 19831.2  226.7419880.84  231.66 20829.8  231.52
 21073.4  241.7221180.58  258.7921430.53  236.82 22081.9  284.4722273.34  302.54
#Mann= 20 ,-1 , 0
       0     .05       0    2182     .05       0    3155     .05       0
  3722.4     .05       0  4461.5     .05       0  6042.8     .08       0
  7231.7     .05       0 13648.2     .07       0 14718.7     .12       0
 15699.2     .05       0 16310.1     .05       0 16796.9     .05       0
 17412.2     .05       0 18678.6     .12       019610.22               0
   19794     .05       0 19831.2     .12       0 20829.8     .05       0
 21073.4     .12       0 22081.9     .16       0
Bank Sta=19560.9,19880.84
XS Rating Curve= 0 ,0
Exp/Cntr=0.3,0.1

Type RM Length L Ch R = 1 ,377940  ,5482.37,5482.37,5482.37
XS GIS Cut Line= 3
3678409.4450529710648032.99942413664054.4448916310633677.9992627
3661047.2012342210632213.9464166
#Sta/Elev= 30
       0   282.9  1827.1  269.49  2981.3  266.69  4135.6  243.89  7021.1  245.28
  7309.7  248.59  8319.7   247.3  9289.4  245.98  9618.2  246.6910665.26  228.06
 15036.9  227.63 16342.1  228.37 17294.1  229.8418771.62   233.1 18830.5  222.11
   18872  201.36   18972  201.3619013.71  222.22 19058.3  232.4520550.63  227.92
   20661  252.6720880.11  251.66 21139.2   285.721229.57  305.5621489.16  291.48
 21702.4  310.13 22250.4   333.522617.39  353.44 23300.1  323.4423645.79   338.9
#Mann= 21 ,-1 , 0
       0     .05       0  1827.1     .05       0  2981.3     .05       0
  4135.6     .05       0  7021.1     .08       0  7309.7     .05       0
  8319.7      .1       0  9289.4     .08       0  9618.2     .05       0
 15036.9     .07       0 16342.1     .07       0 17294.1     .07       0
 18830.5               0   18878               019013.71     .05       0
 19058.3     .12       0   20661     .05       0 21139.2     .12       0
 21702.4     .16       0 22250.4     .05       0 23300.1     .05       0
Bank Sta=18771.62,19058.3
XS Rating Curve= 0 ,0
Exp/Cntr=0.3,0.1

Type RM Length L Ch R = 1 ,372458  ,2551.82,2551.82,2551.82
XS GIS Cut Line= 4
 3680387.997526310647254.70832973669422.3278566310634129.2910111
3668333.3392209710632333.90713463660086.8114227210628883.3861486
#Sta/Elev= 30
       0  277.03  3273.1   251.8  4600.2  251.65  5190.1  253.16  6463.5  253.27
  7255.9  251.54  8544.9  250.42  9171.5  250.54 12268.1  226.28 12841.2   220.5
 13595.1  229.78 16787.5  228.38 17167.4  227.0917853.27  231.5417905.43  222.38
   17949  200.59   18049  200.5918091.53  221.8518313.25  231.09 18355.5  231.97
22713.07  227.36 25197.8  258.1325562.95  268.3225822.94  308.0926012.93  274.92
 26286.6  269.68 26666.7  258.4727102.89  310.31 27650.5  326.2528142.85  322.81
#Mann= 20 ,-1 , 0
       0     .05       0  3273.1     .05       0  4600.2     .05       0
  5190.1     .05       0  6463.5     .08       0  7255.9     .08       0
  8544.9     .08       0  9171.5     .05       0 12268.1     .05       0
 12841.2     .05       0 13595.1     .07       0 16787.5     .07       0
 17167.4     .12       017905.43               018091.53     .05       0
 18355.5     .05       0 25197.8     .05       0 26286.6     .16       0
 26666.7     .12       0 27650.5     .12       0
Bank Sta=17853.27,18313.25
XS Rating Curve= 0 ,0
Exp/Cntr=0.3,0.1

Type RM Length L Ch R = 1 ,369906  ,3235,3235,3235
XS GIS Cut Line= 5
3680387.0910320610645904.69429753673963.4798635510638717.1945649
3671700.9735618110634183.54451153670995.67838447 10632393.179982
3661888.0266523110627277.4835205
#Sta/Elev= 30
       0  283.44  1231.9  260.11  2085.6  260.54 2399.92  246.48  3508.5  253.48
  4346.1     253  5504.2  250.58  6464.5  251.01  6798.6  249.47  7919.5  249.79
  8773.3  248.51 9559.68  245.9610309.26   221.6 11557.9  230.88 15047.3  229.81
15534.07  231.2815564.53  221.71 15607.5  200.23 15762.5  200.2315806.61  222.28
15922.92  230.49 16000.3  232.84 16321.4  230.71 19565.8  226.28 23008.1  238.22
25217.48  234.16 26228.3  264.79 26627.5  305.1526746.88  324.6627076.75  317.66
#Mann= 20 ,-1 , 0
       0     .05       0  1231.9     .05       0  2085.6     .05       0
  3508.5     .08       0  4346.1     .05       0  5504.2     .05       0
  6464.5     .08       0  6798.6     .05       0  7919.5     .08       0
  8773.3     .05       0 11557.9     .07       0 15047.3     .12       0
15564.53               015806.61     .05       0 16000.3     .07       0
 16321.4     .12       0 19565.8     .12       0 23008.1     .05       0
 26228.3     .12       0 26627.5     .12       0
#XS Ineff= 2 , 0
                        23967.14          247.42
Permanent Ineff=
       F       F
Bank Sta=15534.07,15922.92
XS Rating Curve= 0 ,0
Exp/Cntr=0.3,0.1

Type RM Length L Ch R = 1 ,366671  ,5920.13,5920.13,5920.13
XS GIS Cut Line= 4
3693944.8972497110646065.0548691 3675281.702620810634563.3186863
3671049.9318848810631633.63130423661731.7526866310626801.0461531
#Sta/Elev= 30
       0  325.13  499.83  313.93  709.76  282.11  987.68  310.59  1209.6   278.8
 1849.38  256.39  3047.2  290.86  3586.7  253.34  5193.5  225.86 10003.1  225.83
 11767.7  225.78   13653  226.18 16046.6  230.53 17321.4  227.19   20036   227.5
 20696.8  223.52 22110.9  228.1122751.88  231.2922941.17  220.45 22982.5  199.78
23179.74   220.9 23282.7   226.523461.47  231.41 28990.6  230.11 29656.6   227.8
   33480   238.8 35013.5  240.7336425.84   251.8 37363.5  318.71 37565.4   295.6
#Mann= 20 ,-1 , 0
       0     .05       0  3047.2     .16       0  3586.7     .05       0
  5193.5     .05       0 10003.1     .05       0 11767.7      .1       0
   13653     .05       0 16046.6     .05       0 17321.4     .05       0
   20036     .07       0 20696.8     .05       0 22110.9     .05       0
22941.17               023179.74     .05       0 23282.7     .12       0
 28990.6     .05       0 29656.6     .12       0   33480     .05       0
 35013.5     .05       0 37363.5     .12       0
#XS Ineff= 2 , 0
         14147.1  246.88
Permanent Ineff=
       F       F
Bank Sta=22751.88,23461.47
XS Rating Curve= 0 ,0
Exp/Cntr=0.3,0.1

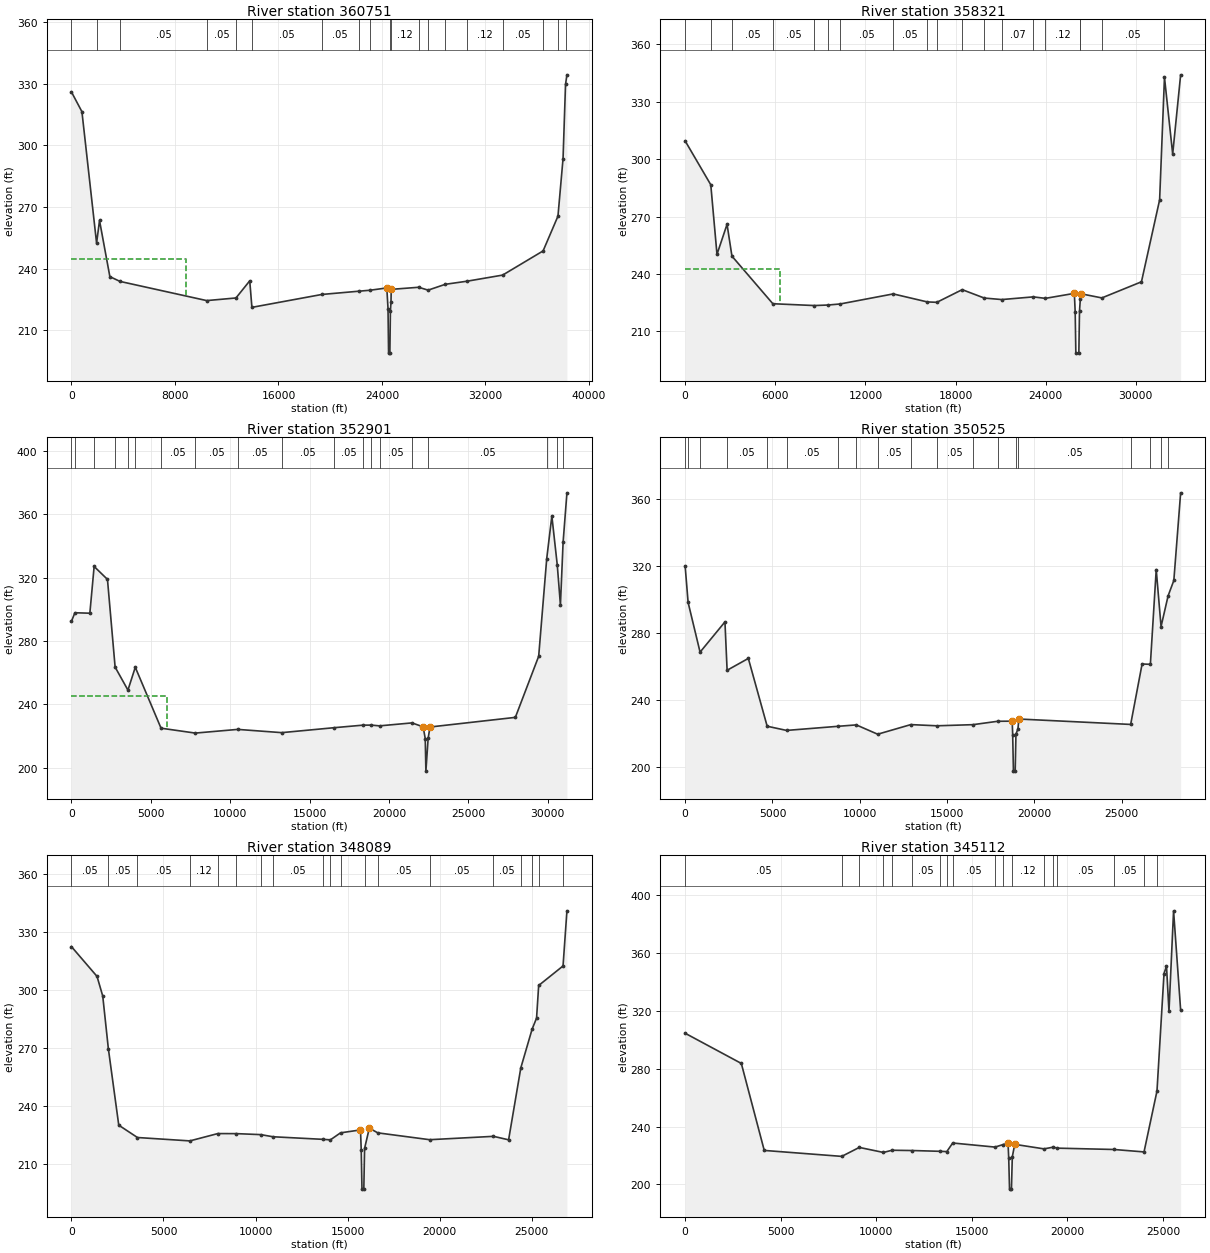
Type RM Length L Ch R = 1 ,360751  ,2429.97,2429.97,2429.97
XS GIS Cut Line= 4
3693813.9526297210644933.08239563676105.6192800610633683.0825859
3674697.9222923110631268.80296563661763.8946827210624671.5805958
#Sta/Elev= 30
       0  326.04  809.99  316.43  1943.6  252.46 2169.97   263.5 2969.95  236.16
  3755.3  233.84 10454.4  224.51 12715.6  225.7913779.91  234.13 13947.5  221.22
 19357.7   227.5 22193.1  229.07 23092.7  229.5624374.44  230.6724466.63  220.63
   24510  198.95   24610  198.9524651.09  219.49 24696.9  223.7324714.44  229.98
 26835.1  230.99 27566.5   229.6 28896.4  232.44   30571  233.94 33325.7  236.92
 36451.3  248.68 37601.1  265.5937994.44  293.63   38186  329.7438294.44  334.36
#Mann= 20 ,-1 , 0
       0     .05       0  1943.6     .05       0  3755.3     .05       0
 10454.4     .05       0 12715.6      .1       0 13947.5     .05       0
 19357.7     .05       0 22193.1     .05       0 23092.7     .05       0
24466.63               024651.09     .05       0 24696.9     .12       0
 26835.1     .05       0 27566.5     .12       0 28896.4     .05       0
   30571     .12       0 33325.7     .05       0 36451.3     .12       0
 37601.1     .12       0   38186     .16       0
#XS Ineff= 2 , 0
         8857.59  244.86
Permanent Ineff=
       F       F
Bank Sta=24374.44,24714.44
XS Rating Curve= 0 ,0
Exp/Cntr=0.3,0.1

Type RM Length L Ch R = 1 ,358321  ,5420,5420,5420
XS GIS Cut Line= 4
 3694161.910923310644220.43683923675715.7306241410632501.6869828
3674327.9712605510630063.45957583672099.5426465610622042.4575732
#Sta/Elev= 30
       0  309.54  1706.6  286.61  2119.4  250.24 2789.22  265.93  3114.8  249.31
  5837.5  224.43  8605.8  223.48  9520.9  223.76 10323.1  224.31 13851.2  229.56
 16116.2  225.38 16754.4  225.17 18443.4  231.79 19912.4   227.4 21079.4  226.61
 23173.3  228.01 23981.6  227.24 25908.9  229.8525965.18  220.02   26008  198.61
   26208  198.61   26252  220.61   26309  227.0826348.64  229.63 27739.9  227.47
30376.28  235.8931585.57  278.73 31908.3  342.7732455.06  302.6532984.71  344.08
#Mann= 20 ,-1 , 0
       0     .16       0  1706.6     .12       0  3114.8     .05       0
  5837.5     .05       0  8605.8     .12       0  9520.9     .05       0
 10323.1     .05       0 13851.2     .05       0 16116.2     .05       0
 16754.4     .05       0 18443.4     .05       0 19912.4     .07       0
 21079.4     .07       0 23173.3     .05       0 23981.6     .12       0
25965.18               0   26252     .05       0   26309     .05       0
 27739.9     .05       0 31908.3     .16       0
#XS Ineff= 2 , 0
         6326.29  242.59
Permanent Ineff=
       F       F
Bank Sta=25908.9,26348.64
XS Rating Curve= 0 ,0
Exp/Cntr=0.3,0.1

Type RM Length L Ch R = 1 ,352901  ,2376.32,2376.32,2376.32
XS GIS Cut Line= 4
3695138.4736027110642755.59298413678048.6298297210632338.9264816
3676855.0534767210628378.4229196 3672793.987123810622606.6936495
#Sta/Elev= 30
       0  292.41   217.4  297.85 1159.67  297.56  1429.4  327.07 2269.34  318.91
  2750.7  263.54  3558.2  249.01  4021.2  263.43  5643.5  224.96    7801  221.87
   10473   224.2 13244.8  222.15 16564.4  225.29 18359.8  226.88 18889.7  226.91
 19404.7  226.43 21450.4   228.322152.71  225.8122283.98  218.36   22325  197.85
 22466.3   218.522582.35  225.7127959.56  231.7929428.99  270.38 29935.8  332.08
30258.67  358.92 30599.2  328.0330798.46   302.8 30966.6  342.3731208.29  373.57
#Mann= 20 ,-1 , 0
       0     .05       0   217.4     .16       0  1429.4     .12       0
  2750.7     .12       0  3558.2     .12       0  4021.2     .05       0
  5643.5     .05       0    7801     .05       0   10473     .05       0
 13244.8     .05       0 16564.4     .05       0 18359.8     .07       0
 18889.7     .07       0 19404.7     .05       0 21450.4     .12       0
22283.98               0 22466.3     .05       0 29935.8     .16       0
 30599.2     .12       0 30966.6     .16       0
#XS Ineff= 2 , 0
         6025.04  245.05
Permanent Ineff=
       F       F
Bank Sta=22152.71,22582.35
XS Rating Curve= 0 ,0
Exp/Cntr=0.3,0.1

Type RM Length L Ch R = 1 ,350525  ,2436.41,2436.41,2436.41
XS GIS Cut Line= 4
3694926.49699256 10640443.093016 3680030.6635953 10631797.259914
3678832.7470278910628411.84312843673510.1330012210623040.7213247
#Sta/Elev= 30
       0  319.76   169.8  298.08   854.5  268.46 2279.09   286.5    2403  257.65
 3618.55  264.72  4697.1  224.29    5807  221.79  8735.7  224.23  9799.9  225.08
 11025.7  219.53 12922.4  225.26 14420.3  224.55 16481.2  225.22 17904.1  227.25
 18729.4  227.3118756.36  219.34   18800  197.52   18900  197.5218944.09  219.57
 19060.1  222.8219108.44  228.59 25513.3  225.3626167.91  261.39 26641.9  261.21
26976.97   317.7   27254  283.72 27657.7  302.0427985.79  311.2128375.34  363.45
#Mann= 22 ,-1 , 0
       0     .05       0   169.8     .05       0   854.5     .12       0
    2403     .05       0  4697.1     .05       0    5807     .05       0
  8735.7     .12       0  9799.9     .12       0 11025.7     .05       0
 12922.4     .05       0 14420.3     .05       0 16481.2     .07       0
 17904.1     .12       018756.36               018756.36               0
   18878               018944.09     .05       0 19060.1     .05       0
 25513.3     .05       0 26641.9     .16       0   27254     .12       0
 27657.7     .16       0
Bank Sta=18729.4,19108.44
XS Rating Curve= 0 ,0
Exp/Cntr=0.3,0.1

Type RM Length L Ch R = 1 ,348089  ,2977.19,2977.19,2977.19
XS GIS Cut Line= 4
3695343.1638101310637995.1763239 3682582.747073810630859.7598205
3680362.2685751310627928.62526283673553.5358015610622650.0964498
#Sta/Elev= 30
       0  322.54 1389.99  307.14 1699.99  296.99  2004.9   269.8 2569.99  230.24
  3584.8  223.86  6431.4  222.11  7948.2  225.89  8949.9  225.87 10288.2  225.35
 10946.7  224.25 13683.9   222.9 14065.5  222.66 14614.9  226.2715699.17  227.79
15739.32  217.52   15780  197.18   15880  197.1815922.12  218.2416178.81  228.71
 16637.2  226.27 19455.5  222.73   22923  224.4723743.96  222.67 24407.3  259.87
 25019.4  279.8325263.07  285.61   25377  302.45 26700.8  312.5426912.11  341.04
#Mann= 20 ,-1 , 0
       0     .05       0  2004.9     .05       0  3584.8     .05       0
  6431.4     .12       0  7948.2     .12       0  8949.9     .12       0
 10288.2     .05       0 10946.7     .05       0 13683.9     .07       0
 14065.5     .05       0 14614.9     .05       015739.32               0
15922.12     .05       0 16637.2     .05       0 19455.5     .05       0
   22923     .05       0 24407.3     .05       0 25019.4     .05       0
   25377     .16       0 26700.8     .16       0
Bank Sta=15699.17,16178.81
XS Rating Curve= 0 ,0
Exp/Cntr=0.3,0.1

Type RM Length L Ch R = 1 ,345112  ,8742,8742,8742
XS GIS Cut Line= 3
3698051.4969761410634297.25983523680759.8304440510626276.4264675
3674694.9295161410623071.5624704
#Sta/Elev= 30
       0  304.39 2938.67  283.55 4138.13  223.48    8192  219.37  9110.2  225.56
 10373.3  222.09 10822.5   223.6 11889.7  223.41 13333.8  222.87 13687.7  222.67
 13997.7  228.61 16209.1  225.79 16610.5  227.4416892.09  228.4716927.49  218.02
   16970  196.76   17070  196.7617114.63  219.0817241.96  227.68 18772.2  224.56
 19258.5  225.74 19470.5  225.05 22430.8  224.13 24005.9  222.45 24683.5   264.5
25051.24   345.625181.24  350.8125311.24  319.4525551.24  388.9225921.24  320.43
#Mann= 19 ,-1 , 0
       0     .05       0    8192     .05       0  9110.2     .05       0
 10373.3     .07       0 10822.5     .05       0 11889.7     .05       0
 13333.8     .05       0 13687.7     .07       0 13997.7     .05       0
 16209.1     .12       0 16610.5     .05       016927.49               0
17114.63     .12       0 18772.2     .12       0 19258.5     .07       0
 19470.5     .05       0 22430.8     .05       0 24005.9     .12       0
 24683.5     .16       0
Bank Sta=16892.09,17241.96
XS Rating Curve= 0 ,0
Exp/Cntr=0.3,0.1

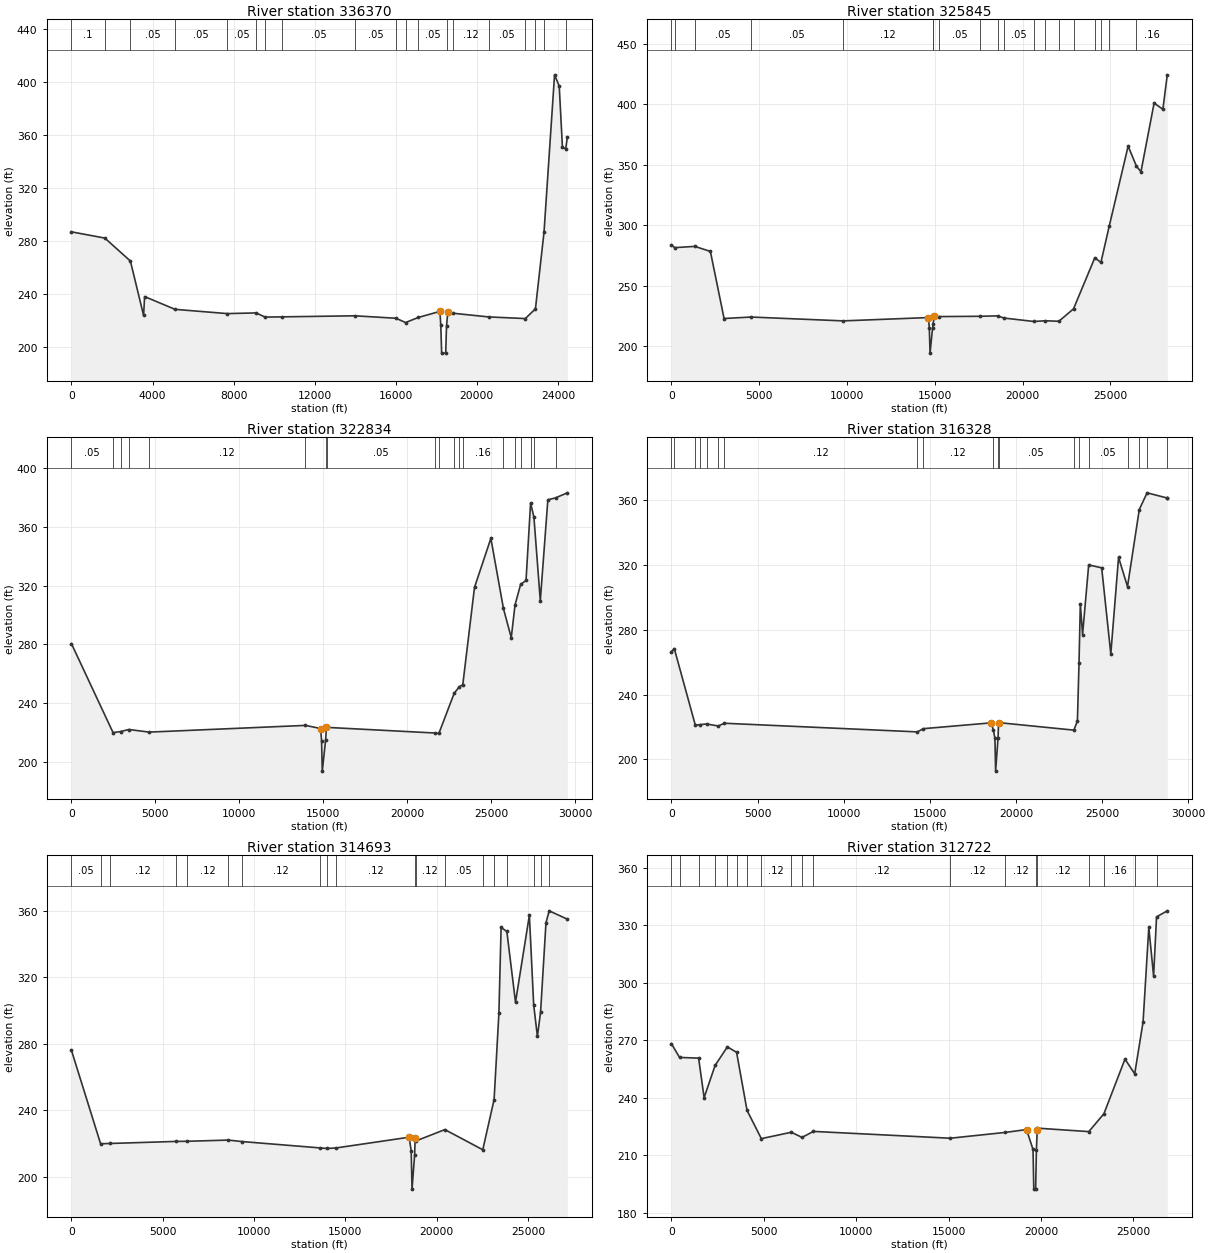
Type RM Length L Ch R = 1 ,336370  ,10525.34,10525.34,10525.34
XS GIS Cut Line= 4
3697692.1837183810630349.81759893685344.0305932210624468.6728651
3680122.6765346410624559.8186802 3674849.238918810622775.9643083
#Sta/Elev= 30
       0  286.91  1644.8  282.23  2908.2  264.93 3559.26   223.9 3609.25  238.14
  5113.9  228.52  7691.3  225.32  9114.7  225.84  9557.4  222.67 10389.1  222.87
 13982.3  223.66   16013  221.82 16485.3  218.58 17117.3  222.4418180.33  226.99
18223.24  216.42   18265  195.54   18465  195.5418505.68  215.8818569.72  226.61
 18846.1  225.57 20579.4  222.82 22391.3  221.58 22892.7  228.89 23315.8  286.58
23836.31  405.2224066.17  396.7624226.08  350.51 24387.7  349.4624465.94   358.3
#Mann= 20 ,-1 , 0
       0      .1       0  1644.8     .08       0  2908.2     .05       0
  5113.9     .05       0  7691.3     .05       0  9114.7     .05       0
  9557.4     .05       0 10389.1     .05       0 13982.3     .05       0
   16013     .07       0 16485.3     .07       0 17117.3     .05       0
18223.24               018505.68     .05       0 18846.1     .12       0
 20579.4     .05       0 22391.3     .12       0 22892.7     .12       0
 23315.8     .16       0 24387.7     .05       0
Bank Sta=18180.33,18569.72
XS Rating Curve= 0 ,0
Exp/Cntr=0.3,0.1

Type RM Length L Ch R = 1 ,325845  ,3011.26,3011.26,3011.26
XS GIS Cut Line= 3
3696970.9312238810628946.15669233685238.9970106310621745.1763436
3670977.6242867310619295.0614932
#Sta/Elev= 30
       0  283.63   186.7  281.36  1337.8  282.39  2219.3   278.2 2999.05  222.72
  4539.4  223.93  9780.7  220.7514635.08   223.514685.93  215.11   14728  194.07
14869.04  214.59 14903.6  218.5814964.86  224.48 15215.9  224.31 17577.9  224.55
   18575  224.92 18935.6   223.1 20636.3  220.27 21288.4  220.84 22064.8  220.44
 22897.1  230.71 24109.5  272.94 24457.7  269.13 24932.6  299.2426007.97  365.37
   26480  348.7726737.53  344.1427487.06  400.9827986.76  395.85 28236.6  424.35
#Mann= 20 ,-1 , 0
       0      .1       0   186.7     .05       0  1337.8     .05       0
  4539.4     .05       0  9780.7     .12       014685.93               0
14869.04     .05       0 14903.6     .12       0 15215.9     .05       0
 17577.9     .05       0   18575     .05       0 18935.6     .05       0
 20636.3     .05       0 21288.4     .05       0 22064.8     .05       0
 22897.1      .1       0 24109.5     .05       0 24457.7     .12       0
 24932.6     .16       0   26480     .16       0
Bank Sta=14635.08,14964.86
XS Rating Curve= 0 ,0
Exp/Cntr=0.3,0.1

Type RM Length L Ch R = 1 ,322834  ,6506.2,6506.2,6506.2
XS GIS Cut Line= 3
3697264.3781435510626118.16333263686176.4971041410619088.9264068
3669831.7909484710617706.5200509
#Sta/Elev= 30
       0  280.42  2475.7  219.91  2926.1  220.59  3419.4  221.99  4630.7  220.22
 13936.7  224.7914837.66  222.6714896.23  214.28 14937.5  193.6515134.34  214.57
15187.51  223.59 15195.2  223.45 21625.7  219.62 21881.3   219.3 22792.9  246.63
 23089.7  250.98 23307.4  252.6124004.04  318.7824979.08  352.14 25726.8  304.39
26193.19  284.53 26417.3  306.82 26750.9  320.8327072.85  323.48 27344.6  376.22
 27542.5  366.5727922.51  309.6228372.34  378.38 28828.8   379.729531.88  383.15
#Mann= 20 ,-1 , 0
       0     .05       0  2475.7     .07       0  2926.1     .05       0
  3419.4     .05       0  4630.7     .12       0 13936.7     .12       0
14896.23               015134.34     .05       0 15195.2     .05       0
 21625.7     .05       0 21881.3     .12       0 22792.9     .05       0
 23089.7      .1       0 23307.4     .16       0 25726.8     .16       0
 26417.3     .05       0 26750.9     .16       0 27344.6     .05       0
 27542.5     .16       0 28828.8     .05       0
Bank Sta=14837.66,15187.51
XS Rating Curve= 0 ,0
Exp/Cntr=0.3,0.1

Type RM Length L Ch R = 1 ,316328  ,1634.53,1634.53,1634.53
XS GIS Cut Line= 4
3698333.0160981410624429.57123733684666.0805055510615443.0931473
3678520.2469967210616588.92648563673236.4639291310613390.8472518
#Sta/Elev= 30
       0  266.35   165.8  268.37  1388.4  221.09  1656.7   221.4  2037.7  221.83
  2715.7   220.6  3076.8  222.28 14275.5  216.95 14621.9  218.9318553.74  222.52
 18685.2  218.3618779.51  212.99   18820  192.74 18961.1  213.29 18989.3  221.89
18993.14  222.67 23362.4  218.0323567.62  223.65 23660.7   259.223737.53     296
23867.45  276.98 24222.9  319.99 24976.8  318.1525506.49  265.0925956.22  324.59
 26475.9  306.59 27160.5  354.14 27612.5  364.43 28755.5   361.328784.57  361.45
#Mann= 22 ,-1 , 0
       0     .05       0   165.8     .05       0  1388.4     .07       0
  1656.7     .05       0  2037.7     .05       0  2715.7     .07       0
  3076.8     .12       0 14275.5     .07       0 14621.9     .12       0
 18685.2     .05       018779.51               018779.51               0
   18878               0 18961.1     .05       0 18989.3     .05       0
 23362.4     .16       0 23660.7     .16       0 24222.9     .05       0
 26475.9     .05       0 27160.5     .12       0 27612.5     .05       0
 28755.5     .08       0
Bank Sta=18553.74,18993.14
XS Rating Curve= 0 ,0
Exp/Cntr=0.3,0.1

Type RM Length L Ch R = 1 ,314693  ,1970.89,1970.89,1970.89
XS GIS Cut Line= 4
3698324.2182154710623405.12479543684197.3304588110614141.0097935
3678051.4969499710614609.75984023674640.1573159710612343.0143737
#Sta/Elev= 30
       0  275.96  1595.1   219.8    2123  219.97  5701.8  221.19  6328.1  221.28
    8588  222.01  9327.2  221.13 13631.7  217.28 13998.1  216.95 14507.3   217.3
18491.91  223.7318603.86  215.58   18650  192.51 18790.9  212.9618821.59  223.13
 18856.2  221.46 20448.2  228.32 22522.9  216.19 23143.7  246.3523407.11  298.34
23526.99  349.87 23842.1  347.4824316.22  304.8825075.48  357.23 25311.6  303.34
25515.05  284.38   25688  298.8725984.59  352.63 26158.8  359.8827153.45  354.88
#Mann= 20 ,-1 , 0
       0     .05       0  1595.1     .05       0    2123     .12       0
  5701.8     .05       0  6328.1     .12       0    8588     .07       0
  9327.2     .12       0 13631.7     .05       0 13998.1     .05       0
 14507.3     .12       018603.86               0 18790.9     .05       0
 18856.2     .12       0 20448.2     .05       0 22522.9     .12       0
 23143.7     .12       0 23842.1      .1       0 25311.6     .16       0
   25688     .16       0 26158.8     .05       0
Bank Sta=18491.91,18821.59
XS Rating Curve= 0 ,0
Exp/Cntr=0.3,0.1

Type RM Length L Ch R = 1 ,312722  ,6775.84,6775.84,6775.84
XS GIS Cut Line= 3
3698431.7911630610622317.63090743685755.2863323810613012.2492557
3674760.7502506410611454.5584735
#Sta/Elev= 30
       0  268.24   440.5  261.04  1471.9  260.68 1769.47  240.04  2365.2  256.88
  3026.6  266.56  3525.7  263.72  4091.3  233.39  4865.4  218.61  6487.5  221.95
  7068.5  219.25  7680.1  222.39 15084.6  218.83 18061.5  221.8619213.45  223.35
19565.59  212.94   19607  192.23   19707  192.2319747.76  212.6119793.12  223.37
 19802.3  224.09 22584.4  222.28 23403.4  231.6624540.47  260.16 25066.8  252.49
25519.92  279.5925829.75  328.96 26089.6  303.56 26248.5  334.4826829.19  337.64
#Mann= 20 ,-1 , 0
       0     .08       0   440.5     .05       0  1471.9     .16       0
  2365.2     .12       0  3026.6     .05       0  3525.7     .12       0
  4091.3     .12       0  4865.4     .12       0  6487.5     .07       0
  7068.5     .07       0  7680.1     .12       0 15084.6     .12       0
 18061.5     .12       019565.59               019747.76     .05       0
 19802.3     .12       0 22584.4     .12       0 23403.4     .16       0
 25066.8     .16       0 26248.5     .05       0
Bank Sta=19213.45,19793.12
XS Rating Curve= 0 ,0
Exp/Cntr=0.3,0.1

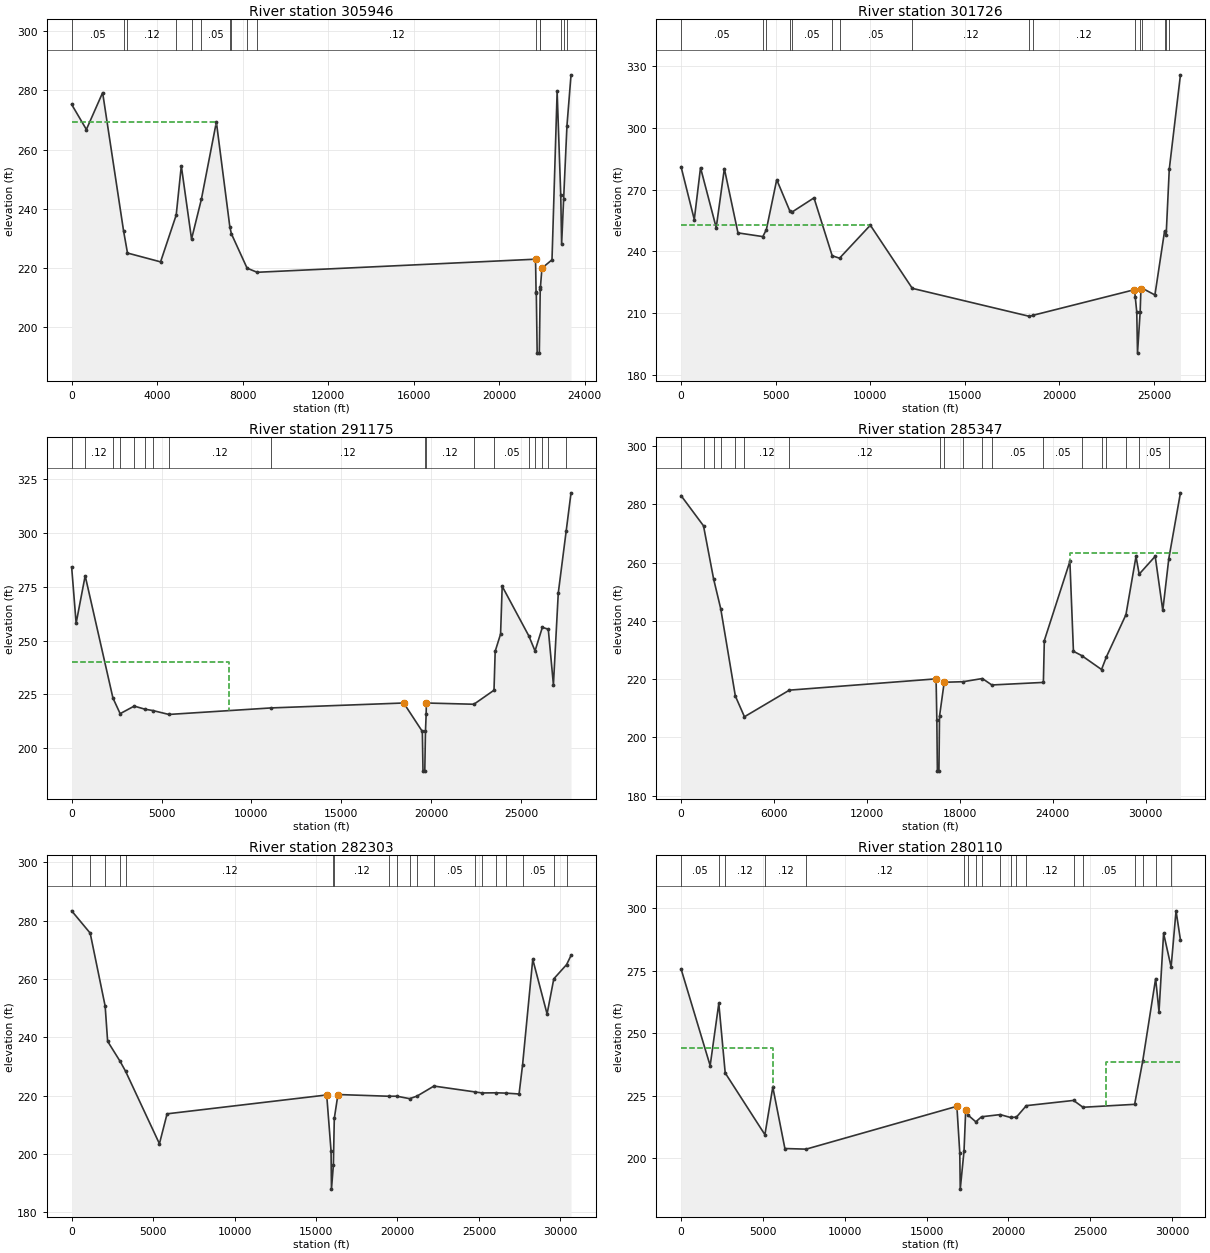
Type RM Length L Ch R = 1 ,305946  ,4220,4220,4220
XS GIS Cut Line= 2
3700925.6352567210620562.42838113681072.3304752310608255.5930866
#Sta/Elev= 30
       0   275.3  689.95  266.82  1449.9  279.27  2429.4  232.56  2612.7  225.09
 4159.72  222.11    4891  237.92 5129.65  254.55  5608.6  229.81  6068.5  243.25
 6769.53  269.35  7397.7  234.05  7472.1   231.6  8206.7  219.98  8675.4  218.59
21698.58  223.01 21723.2     21221734.11  211.72   21775  191.28   21875  191.28
21918.38  212.97 21925.5  213.4621998.58  219.9822468.57  222.8122708.57  279.67
 22877.6  244.6622918.57  228.09 23011.6   243.2   23168  268.1223358.57  285.29
#Mann= 17 ,-1 , 0
       0     .05       0  2429.4     .16       0  2612.7     .12       0
    4891     .05       0  5608.6     .12       0  6068.5     .05       0
  7397.7     .16       0  7472.1     .12       0  8206.7     .05       0
  8675.4     .12       0 21723.2     .05       021734.11               0
21918.38     .05       0 21925.5     .12       0 22877.6     .16       0
 23011.6     .12       0   23168     .16       0
#XS Ineff= 2 , 0
         6729.26   269.3
Permanent Ineff=
       F       F
Bank Sta=21698.58,21998.58
XS Rating Curve= 0 ,0
Exp/Cntr=0.3,0.1

Type RM Length L Ch R = 1 ,301726  ,10550.75,10550.75,10550.75
XS GIS Cut Line= 5
3704379.8776920610622077.64811963696133.3374266310616556.1296351
3686112.8397511410608083.42873283684439.9277426310605242.1729324
3684395.8530276410605217.9813797
#Sta/Elev= 30
       0  281.06   699.6  255.46 1029.41   280.6 1858.94  251.53  2288.7  280.14
 3008.29  248.99    4322  247.19    4509  250.57 5057.12  274.77  5756.7  259.45
  5885.4  259.21 7025.98  265.96  7988.4   237.9  8376.2  236.7210004.25  252.72
 12221.6   222.1 18415.5  208.52   18578  208.9823965.88  221.45 24006.8  217.88
24085.12  210.63   24125  190.6924264.88  210.6324305.61  221.78 24347.8  222.28
25045.03  218.89 25553.9  249.79 25640.5  248.17 25803.5  279.8326394.28  325.62
#Mann= 17 ,-1 , 0
       0     .05       0    4322     .16       0    4509     .05       0
  5756.7     .12       0  5885.4     .05       0  7988.4     .16       0
  8376.2     .05       0 12221.6     .12       0 18415.5     .05       0
   18578     .12       0 24006.8     .07       024085.12               0
24264.88     .05       0 24347.8     .12       0 25553.9     .16       0
 25640.5     .12       0 25803.5     .05       0
#XS Ineff= 2 , 0
         9929.58  252.65
Permanent Ineff=
       F       F
Bank Sta=23965.88,24305.61
XS Rating Curve= 0 ,0
Exp/Cntr=0.3,0.1

Type RM Length L Ch R = 1 ,291175  ,5828.21,5828.21,5828.21
XS GIS Cut Line= 4
3708295.3869213910620316.07388693692952.3264002210609381.5816483
3692254.3327174610607519.19265663686073.1649617310604343.8518944
#Sta/Elev= 30
       0  284.32  249.88  258.08   753.3  280.17  2296.6  223.27  2698.6  215.97
  3479.9  219.49  4082.8  218.03  4516.9  217.42  5408.4   215.6   11100  218.64
18470.88  220.9319507.06  207.68   19544  189.21   19644  189.2119681.03  207.73
 19719.8  215.6219730.17  220.93 22374.9  220.35 23493.7  226.8823558.99  245.01
23858.93  253.0323948.91  275.28 25431.4  252.16 25776.1  245.17 26183.7  256.18
   26513  255.2626798.36  229.41 27068.3  272.12 27506.7   300.927778.16  318.79
#Mann= 19 ,-1 , 0
       0     .05       0   753.3     .12       0  2296.6     .05       0
  2698.6     .07       0  3479.9     .12       0  4082.8     .12       0
  4516.9     .07       0  5408.4     .12       0   11100     .12       0
19507.06               019681.03     .05       0 19719.8     .12       0
 22374.9     .12       0 23493.7     .05       0 25431.4     .12       0
 25776.1     .16       0 26183.7     .05       0   26513     .12       0
 27506.7     .16       0
#XS Ineff= 2 , 0
         8748.56   240.1
Permanent Ineff=
       F       F
Bank Sta=18470.88,19730.17
XS Rating Curve= 0 ,0
Exp/Cntr=0.3,0.1

Type RM Length L Ch R = 1 ,285347  ,3043.72,3043.72,3043.72
XS GIS Cut Line= 2
3711317.4248405510616312.59632963684937.2164462210597766.5894584
#Sta/Elev= 30
       0  283.05  1449.7  272.67  2103.9  254.37  2562.6  244.18    3507  214.17
  4094.1  207.07  6994.9  216.2116468.43  220.0916516.68  206.05   16552  188.39
   16652  188.3916689.67  207.22   16992  218.92   18215  219.11 19454.9   220.2
   20068  217.99 23396.4  218.8723457.76  233.2525107.61  260.4625337.59  229.56
   25866   228.1 27151.8   223.3 27467.2  227.67 28726.9  242.12 29377.2  262.13
 29582.7  256.0730617.08   262.231107.04   243.6 31496.3  261.4232246.93     284
#Mann= 20 ,-1 , 0
       0     .16       0  1449.7     .16       0  2103.9     .05       0
  2562.6     .12       0    3507     .07       0  4094.1     .12       0
  6994.9     .12       016516.68               016689.67     .05       0
   16992     .07       0   18215     .12       0 19454.9     .07       0
   20068     .05       0 23396.4     .05       0   25866     .05       0
 27151.8     .12       0 27467.2     .05       0 28726.9     .12       0
 29582.7     .05       0 31496.3     .16       0
#XS Ineff= 2 , 0
                        25114.81           263.2
Permanent Ineff=
       F       F
Bank Sta=16468.43,16992
XS Rating Curve= 0 ,0
Exp/Cntr=0.3,0.1

Type RM Length L Ch R = 1 ,282303  ,2192.97,2192.97,2192.97
XS GIS Cut Line= 3
 3712192.365019810615688.07395663710065.6287877310612172.4490981
3687973.61490098 10597458.907331
#Sta/Elev= 30
       0  283.42  1138.5  275.77  2057.1  250.75 2209.38  238.66  2968.3  231.86
    3314  228.36 5388.52  203.53 5858.41  213.7915655.78  220.2615922.42  201.07
15948.64  187.9616064.92   196.1 16122.2  212.2116345.59  220.41 19456.6  219.82
 19955.3  219.84 20745.3  218.99 21197.5  219.86 22237.1  223.31 24747.1  221.31
 25187.4  220.95   26067     221 26639.6   220.927463.42  220.59 27679.8  230.65
28303.25  266.7829183.08  248.04 29593.9  260.09 30382.5  264.9930652.79  268.12
#Mann= 20 ,-1 , 0
       0     .05       0  1138.5     .16       0  2057.1     .05       0
  2968.3     .16       0    3314     .12       015922.42               0
16064.92     .05       0 16122.2     .12       0 19456.6     .05       0
 19955.3     .07       0 20745.3     .07       0 21197.5     .05       0
 22237.1     .05       0 24747.1     .12       0 25187.4     .12       0
   26067     .05       0 26639.6     .07       0 27679.8     .05       0
 29593.9     .16       0 30382.5     .16       0
Bank Sta=15655.78,16345.59
XS Rating Curve= 0 ,0
Exp/Cntr=0.3,0.1

Type RM Length L Ch R = 1 ,280110  ,2890.23,2890.23,2890.23
XS GIS Cut Line= 3
 3715982.544447310612248.10905173709110.7678365610609655.0879911
 3690664.587209310595635.9907012
#Sta/Elev= 30
       0   275.8 1778.72  237.07  2306.9  261.98  2698.2  234.14  5123.7  209.45
 5605.97  228.49 6345.43   203.9  7641.2  203.6516854.57   220.817030.94  202.18
   17060  187.6517290.51  202.9117394.57  219.41 17551.7   217.2 18010.2  214.59
 18361.8  216.61 19502.2  217.48 20131.9  216.32 20494.8  216.48 21097.1  221.06
 23983.5  223.15 24558.4  220.41 27715.1  221.59 28212.7  239.03   28999   271.9
29204.57  258.6429484.57  290.03 29944.5  276.5330244.57  299.0330514.57  287.39
#Mann= 20 ,-1 , 0
       0     .05       0  2306.9     .16       0  2698.2     .12       0
  5123.7     .12       0  7641.2     .12       017030.94               0
17290.51     .05       0 17551.7     .12       0 18010.2     .07       0
 18361.8     .12       0 19502.2     .07       0 20131.9     .07       0
 20494.8     .12       0 21097.1     .12       0 23983.5     .05       0
 24558.4     .05       0 27715.1     .05       0 28212.7     .16       0
   28999     .12       0 29944.5     .05       0
#XS Ineff= 2 , 0
         5605.63  244.1325958.67          238.72
Permanent Ineff=
       F       F
Bank Sta=16854.57,17394.57
XS Rating Curve= 0 ,0
Exp/Cntr=0.3,0.1