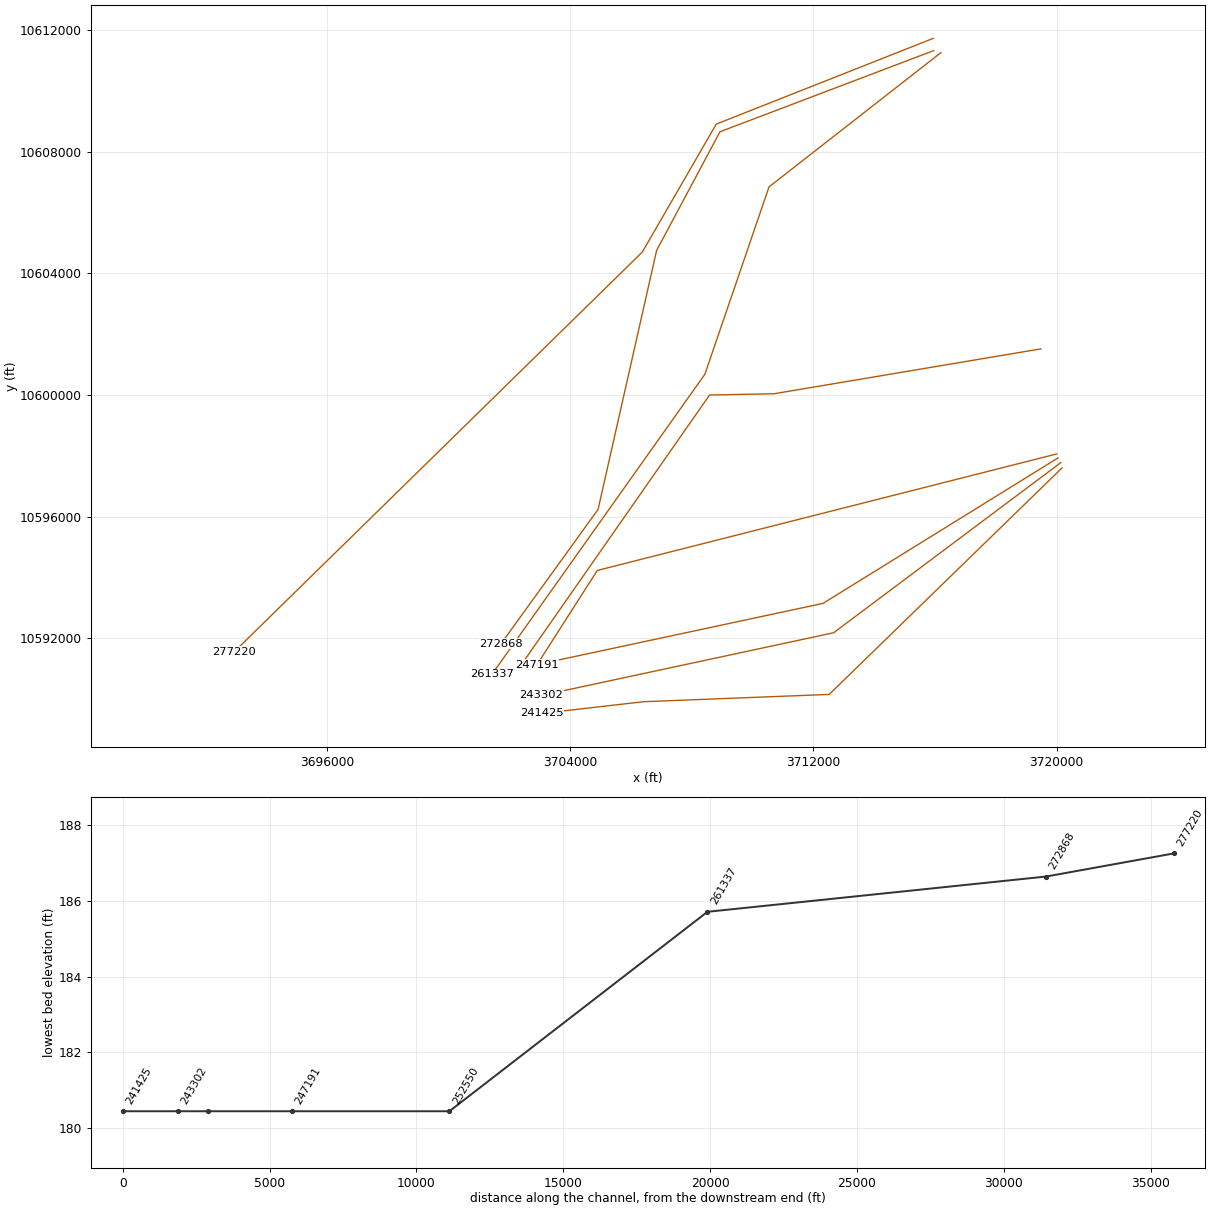
HEC-RAS study TRINITY RIVER.prj: TRINITY RIVER Base Level Engineering

--- TRINITY RIVER.g06 (geometry) --- (continued)

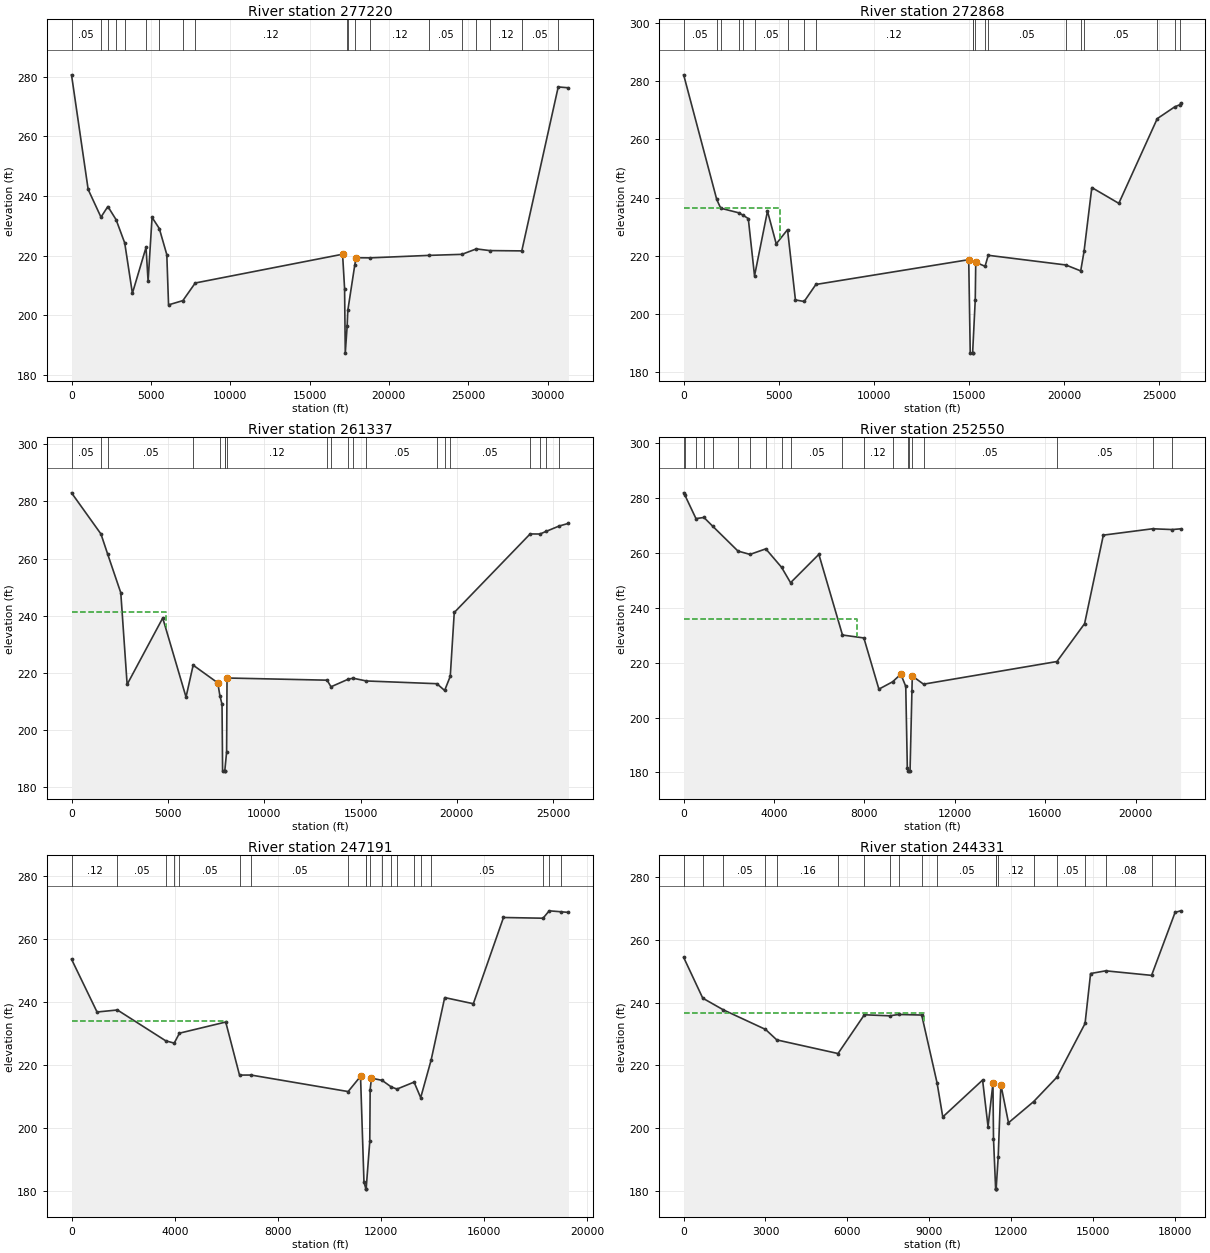
Type RM Length L Ch R = 1 ,277220  ,4351.8,4351.8,4351.8
XS GIS Cut Line= 4
3715943.4818613810611740.29641913708806.9482342210608917.2407135
3706376.3927278810604707.17137773692964.9346427210591556.1294384
#Sta/Elev= 30
       0  280.67 1049.26  242.19  1856.4   232.9    2292  236.47  2811.8  232.02
  3353.6  224.23  3837.3  207.34  4696.9  222.74 4826.62  211.37 5076.45  232.81
  5532.6  229.08 6005.82  220.31 6115.74  203.45  7018.7  204.88  7797.4  210.79
17084.34  220.45 17210.7   208.9   17254  187.2517372.21  196.35 17413.5  201.57
 17851.6   216.817934.01  219.27 18826.7  219.23 22515.8  220.06 24603.8  220.41
 25514.7  222.24 26360.2  221.67   28379  221.57   30675   276.631318.78  276.32
#Mann= 20 ,-1 , 0
       0     .05       0  1856.4     .12       0    2292     .16       0
  2811.8     .12       0  3353.6     .12       0  4696.9     .05       0
  5532.6     .12       0  7018.7     .12       0  7797.4     .12       0
 17210.7               017372.21     .05       0 17413.5     .12       0
 17851.6     .12       0 18826.7     .12       0 22515.8     .05       0
 24603.8     .05       0 25514.7     .12       0 26360.2     .12       0
   28379     .05       0   30675     .05       0
Bank Sta=17084.34,17934.01
XS Rating Curve= 0 ,0
Exp/Cntr=0.3,0.1

Type RM Length L Ch R = 1 ,272868  ,11531,11531,11531
XS GIS Cut Line= 5
3715956.5028327310611336.65057283708928.7577018910608665.1109684
3706845.4242701410604758.86090693704919.9530554710596232.7408201
3701732.2957168810591816.5462404
#Sta/Elev= 30
       0  282.11  1740.9239.3439  1949.5236.3522  2888.1234.7919  3110.2234.0104
 3399.27   232.8    3728213.1572 4409.06  235.35 4868.97  224.12  5463.1229.0005
 5878.76  204.89  6337.4204.3543  6954.8210.194914992.22   218.715072.14  186.64
   15191  186.64   15197  186.64 15336.1204.998215361.83  217.79 15851.4216.4243
 16018.8220.2004 20099.3216.8844 20881.4214.8476 21056.3221.507321466.09  243.44
22885.26  238.02 24906.9267.0778 25819.5271.0966 26116.7271.916226133.35  272.42
#Mann= 20 ,-1 , 0
       0     .05       0  1740.9     .16       0  1949.5     .12       0
  2888.1     .05       0  3110.2     .12       0    3728     .05       0
  5463.1     .12       0  6337.4     .12       0  6954.8     .12       0
   15191     .05       0   15197     .05       0 15336.1     .12       0
 15851.4     .07       0 16018.8     .05       0 20099.3     .05       0
 20881.4     .12       0 21056.3     .05       0 24906.9     .12       0
 25819.5     .16       0 26116.7     .16       0
#XS Ineff= 2 , 0
         5081.83  236.43
Permanent Ineff=
       F       F
Bank Sta=14992.22,15361.83
XS Rating Curve= 0 ,0
Exp/Cntr=0.3,0.1

Type RM Length L Ch R = 1 ,261337  ,8786.71,8786.71,8786.71
XS GIS Cut Line= 4
3716191.5568245510611268.32557823710541.1868917210606850.1378923
3708432.8367777210600683.19254913701434.2021529710590809.2293574
#Sta/Elev= 30
       0  283.01  1528.3268.6236  1874.7261.6197 2557.38  248.07 2887.05  216.02
 4735.16  239.25 5943.91   211.6  6314.2 222.759 7592.48  216.57  7700.3212.1279
 7812.39  209.04 7842.38  185.71  7948.9  185.71  7954.9  185.71  8050.2192.3704
 8072.28  218.27 13267.3217.5073 13467.6215.1929 14371.2217.8707 14616.8 218.192
   15304217.2328 18964.1216.2777 19367.1213.9039 19659.5218.874919866.46  241.17
 23804.9 268.636 24317.2268.6106 24624.3269.4967 25301.6271.382125792.99  272.33
#Mann= 20 ,-1 , 0
       0     .05       0  1528.3     .12       0  1874.7     .05       0
  6314.2     .12       0  7700.3     .05       0  7948.9     .05       0
  7954.9     .05       0  8050.2     .12       0 13267.3     .07       0
 13467.6     .05       0 14371.2     .07       0 14616.8     .05       0
   15304     .05       0 18964.1     .05       0 19367.1     .07       0
 19659.5     .05       0 23804.9     .12       0 24317.2     .12       0
 24624.3     .12       0 25301.6     .05       0
#XS Ineff= 2 , 0
         4885.43  241.41
Permanent Ineff=
       F       F
Bank Sta=7592.48,8072.28
XS Rating Curve= 0 ,0
Exp/Cntr=0.3,0.1

Type RM Length L Ch R = 1 ,252550  ,5359.05,5359.05,5359.05
XS GIS Cut Line= 4
3719479.7116655610601518.26207313710712.35059139 10600042.567518
3708585.6146873810599999.16471763702309.2020433810590996.7293105
#Sta/Elev= 30
       0  281.95    47.9281.2314   546.2272.5403   897.2272.9733    1286 269.773
  2405.7260.7022  2937.9259.4952  3635.5261.5123  4333.1254.7934  4731.7249.1667
 5983.74  259.51  7029.4230.0903  7975.6229.0202 8640.97  210.35  9249.7213.0398
 9609.74   215.8 9829.45  211.38 9899.35  181.58  9945.6180.5108  9951.6180.5058
10019.19  180.45 10103.3209.765310119.06  215.14 10616.9212.1615 16520.2 220.422
17744.44  234.2418573.96  266.52 20751.9268.8415 21623.9268.555621991.98  268.82
#Mann= 20 ,-1 , 0
       0     .05       0    47.9     .16       0   546.2     .05       0
   897.2     .16       0    1286     .16       0  2405.7     .05       0
  2937.9     .05       0  3635.5     .12       0  4333.1     .12       0
  4731.7     .05       0  7029.4     .05       0  7975.6     .12       0
  9249.7     .12       0  9945.6     .05       0  9951.6     .05       0
 10103.3     .05       0 10616.9     .05       0 16520.2     .05       0
 20751.9     .05       0 21623.9     .12       0
#XS Ineff= 2 , 0
         7677.96  235.87
Permanent Ineff=
       F       F
Bank Sta=9609.74,10119.06
XS Rating Curve= 0 ,0
Exp/Cntr=0.3,0.1

Type RM Length L Ch R = 1 ,247191  ,2860.24,2860.24,2860.24
XS GIS Cut Line= 3
3720000.7266996410598059.88710013704895.2037611310594224.7238387
3702915.3268153810591126.6132371
#Sta/Elev= 30
       0  253.59  989.67  236.79  1778.9 237.432  3651.5227.6304  3981.6226.8907
  4183.7230.0532 5977.97   233.6  6511.8216.7245  6959.3216.7382 10722.4211.4849
11203.08  216.3311336.25  182.67 11413.7  180.45 11419.7  180.45 11560.9195.6116
11576.17  212.1311626.16  215.76 12038.6215.0458 12390.4 212.972 12614.1212.2757
 13278.8214.4908 13534.9209.5421 13938.9221.500114465.29  241.3815574.95  239.42
16743.91  266.85   18277266.6227   18516268.9711 18988.8268.664619261.59  268.47
#Mann= 20 ,-1 , 0
       0     .12       0  1778.9     .05       0  3651.5     .12       0
  3981.6     .16       0  4183.7     .05       0  6511.8     .07       0
  6959.3     .05       0 10722.4     .05       0 11413.7     .05       0
 11419.7     .05       0 11560.9     .12       0 12038.6     .07       0
 12390.4     .12       0 12614.1     .07       0 13278.8     .05       0
 13534.9     .12       0 13938.9     .05       0   18277     .12       0
   18516     .05       0 18988.8     .12       0
#XS Ineff= 2 , 0
         5970.15  233.82
Permanent Ineff=
       F       F
Bank Sta=11203.08,11626.16
XS Rating Curve= 0 ,0
Exp/Cntr=0.3,0.1

Type RM Length L Ch R = 1 ,244331  ,1028.78,1028.78,1028.78
XS GIS Cut Line= 3
3720045.8430792210597929.80763593712318.2535475510593141.5258739
3703392.1874102210591228.7974159
#Sta/Elev= 30
       0  254.46   700.5241.4337  1454.8237.7023  3000.3 231.459  3415.1228.1015
  5659.8223.7496  6625.8236.1264  7548.7235.7931  7885.3236.2201    8728236.0411
  9292.9214.3167 9500.78   203.510960.53  215.2811160.49  200.4111340.46  214.23
11360.46   196.6 11439.1180.4597 11445.1180.456411456.76  180.45 11533.2 190.755
11630.41  213.8311910.36  201.64 12833.2208.4077 13686.3216.2055 14717.2 233.341
14919.85   249.3 15475.4250.1615 17156.6 248.709 18017.7268.805918219.23  269.32
#Mann= 20 ,-1 , 0
       0     .12       0   700.5     .07       0  1454.8     .05       0
  3000.3     .12       0  3415.1     .16       0  5659.8     .05       0
  6625.8     .12       0  7548.7     .16       0  7885.3     .05       0
    8728     .05       0  9292.9     .05       0 11439.1     .05       0
 11445.1     .05       0 11533.2     .12       0 12833.2     .05       0
 13686.3     .05       0 14717.2     .05       0 15475.4     .08       0
 17156.6     .12       0 18017.7     .12       0
#XS Ineff= 2 , 0
         8794.49   236.7
Permanent Ineff=
       F       F
Bank Sta=11340.46,11630.41
XS Rating Curve= 0 ,0
Exp/Cntr=0.3,0.1

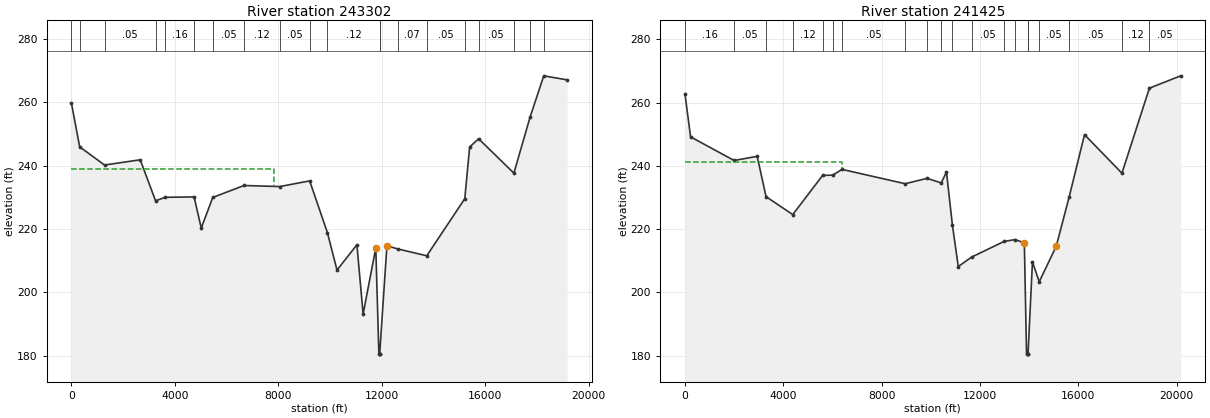
Type RM Length L Ch R = 1 ,243302  ,1877,1877,1877
XS GIS Cut Line= 3
3720134.8186230510597773.55762033712665.4326432210592174.0914571
3703058.9105177210590110.4682877
#Sta/Elev= 30
       0  259.68   317.6245.9266  1278.7240.1848 2658.62  241.83  3251.2228.8813
  3631.3229.9881  4740.5230.0985 5017.41  220.27  5463.4 229.944  6671.5233.7151
  8050.7233.3761  9207.9235.1736  9893.5218.840310264.78     20711034.41  214.99
 11274.3   193.111764.07  213.9711884.01  180.45 11908.5  180.45 11914.5  180.45
12193.86  214.69 12606.5213.6893 13734.9211.5118 15204.3229.548715392.33  245.86
 15738.1 248.482 17102.2 237.613   17729255.3284 18257.2268.354519160.78  267.08
#Mann= 20 ,-1 , 0
       0     .05       0   317.6     .12       0  1278.7     .05       0
  3251.2     .12       0  3631.3     .16       0  4740.5     .05       0
  5463.4     .05       0  6671.5     .12       0  8050.7     .05       0
  9207.9     .05       0  9893.5     .12       0 11908.5     .05       0
 11914.5     .05       0 12606.5     .07       0 13734.9     .05       0
 15204.3     .05       0 15738.1     .05       0 17102.2     .12       0
   17729     .12       0 18257.2     .05       0
#XS Ineff= 2 , 0
         7830.08  239.07
Permanent Ineff=
       F       F
Bank Sta=11764.07,12193.86
XS Rating Curve= 0 ,0
Exp/Cntr=0.3,0.1

Type RM Length L Ch R = 1 ,241425  ,2727.01,2727.01,2727.01
XS GIS Cut Line= 4
3720178.2197829610597602.01564063712520.4332613110590144.4216319
3706410.3431193110589904.02447493703071.8845731310589520.3021452
#Sta/Elev= 30
       0  262.81  229.08  249.17  1997.9241.6991 2939.76     243  3297.8230.2663
  4385.7224.5831  5600.5236.9756  6010.6237.0606  6388.9238.8832  8958.4234.3408
  9848.4236.0438 10425.8234.604310639.09  238.05 10877.4221.421811118.71  208.15
 11664.9211.1519   12987216.1017 13431.3216.670313806.34  215.6413896.26  180.45
 13950.7  180.45 13956.7  180.4514136.05  209.62 14413.3203.3376 15105.2  214.61
 15629.2 230.13216254.19  249.87 17776.4237.6661 18893.6264.568420164.17  268.47
#Mann= 20 ,-1 , 0
       0     .16       0  1997.9     .05       0  3297.8     .12       0
  4385.7     .12       0  5600.5     .05       0  6010.6     .16       0
  6388.9     .05       0  8958.4     .05       0  9848.4     .05       0
 10425.8     .16       0 10877.4     .12       0 11664.9     .05       0
   12987     .05       0 13431.3     .05       0 13950.7     .05       0
 13956.7     .05       0 14413.3     .05       0 15629.2     .05       0
 17776.4     .12       0 18893.6     .05       0
#XS Ineff= 2 , 0
         6386.34  241.08
Permanent Ineff=
       F       F
Bank Sta=13806.34,15105.2
XS Rating Curve= 0 ,0
Exp/Cntr=0.3,0.1