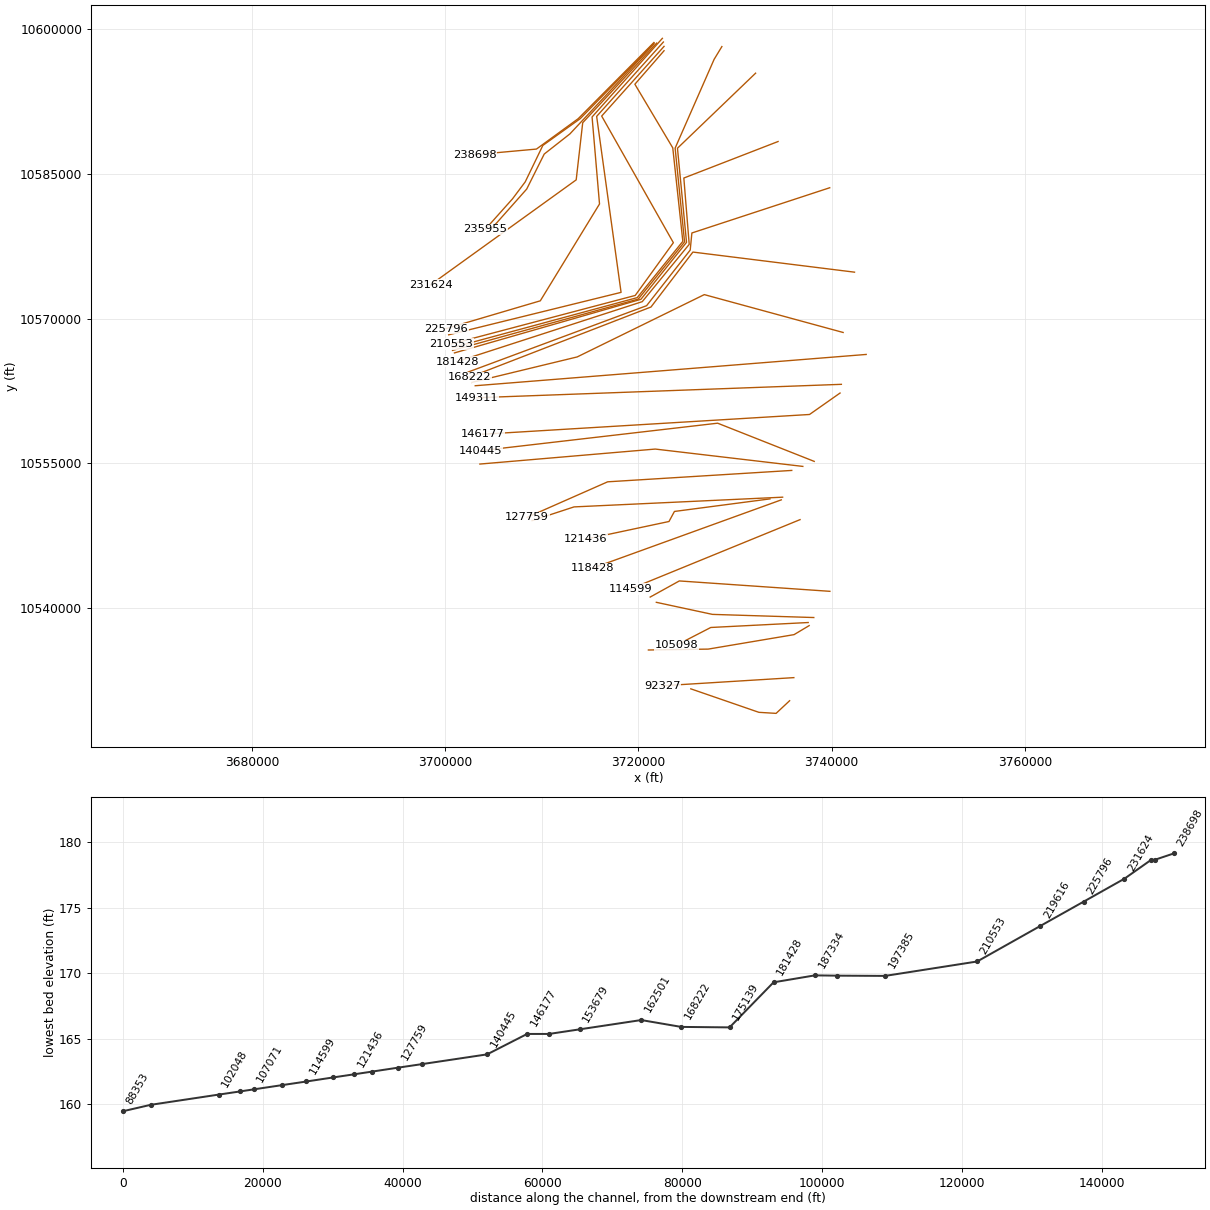
HEC-RAS study TRINITY RIVER.prj: TRINITY RIVER Base Level Engineering

--- TRINITY RIVER.g06 (geometry) --- (continued)

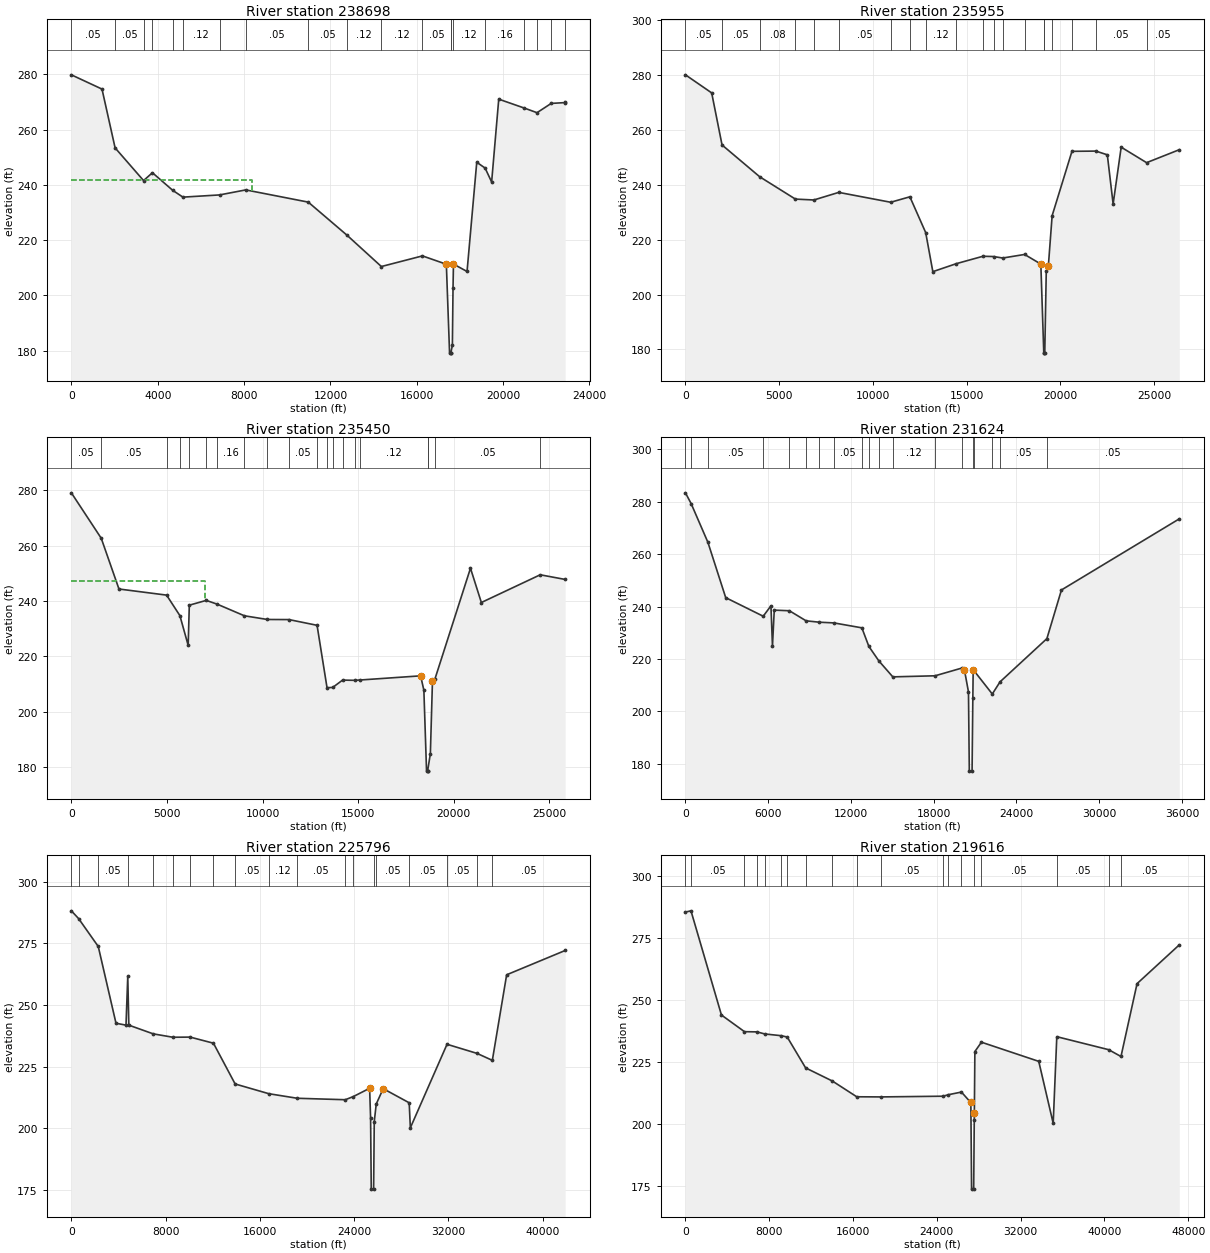
Type RM Length L Ch R = 1 ,238698  ,2743,2743,2743
XS GIS Cut Line= 4
3721601.0259924710598611.20751983713767.2998620610590722.2895706
3709439.2048437110587569.95040293703062.5056548910586989.0286645
#Sta/Elev= 30
       0  279.82  1419.7  274.66  2026.8 253.385  3344.9241.5599  3755.5244.3967
  4701.4237.9915    5169235.5659  6863.3236.3671  8079.3238.1841 10974.7233.7643
 12762.7221.8374 14360.8210.4624 16263.6214.307617371.05  211.2917520.89  179.13
 17570.4  179.13 17576.4  179.1317650.76  181.98 17680.5202.661417700.71  211.35
18330.06  208.6718779.59  248.19   19168246.076119468.88  241.0519798.54  271.02
 20984.8267.7864   21571266.1186 22228.7269.4774   22863269.771322875.36  270.06
#Mann= 20 ,-1 , 0
       0     .05       0  2026.8     .05       0  3344.9     .08       0
  3755.5     .08       0  4701.4     .16       0    5169     .12       0
  6863.3     .05       0  8079.3     .05       0 10974.7     .05       0
 12762.7     .12       0 14360.8     .12       0 16263.6     .05       0
 17570.4     .05       0 17576.4     .05       0 17680.5     .12       0
   19168     .16       0 20984.8     .12       0   21571     .16       0
 22228.7     .05       0   22863     .08       0
#XS Ineff= 2 , 0
         8352.47  241.85
Permanent Ineff=
       F       F
Bank Sta=17371.05,17700.71
XS Rating Curve= 0 ,0
Exp/Cntr=0.3,0.1

Type RM Length L Ch R = 1 ,235955  ,505.08,505.08,505.08
XS GIS Cut Line= 6
3721634.0118188910598548.70764483713978.5543608110590727.9749267
3710103.8829763110587949.09793863708276.6261321310584167.8479551
3706960.02476272 10582409.457115 3704147.524810310579256.6792998
#Sta/Elev= 30
       0  280.16 1399.23  273.57  1952.2254.5729    3959  242.98  5863.4234.8286
  6848.3 234.506    8176237.2768 10945.3233.6756 11968.6235.6653 12812.2222.6039
13193.04  208.36 14449.1 211.284 15867.1213.9763   16431213.8706 16921.2213.3347
 18086.5214.634918951.85  211.13 19109.5178.7316 19115.5178.721119161.84  178.64
19241.84  208.5419351.83  210.32 19555.2228.7832 20611.7252.2541 21886.7252.3417
22497.91  250.9822807.54  233.0523237.04  253.77 24591.8 248.11626333.41  252.84
#Mann= 20 ,-1 , 0
       0     .05       0  1952.2     .05       0    3959     .08       0
  5863.4     .08       0  6848.3     .05       0    8176     .05       0
 10945.3     .05       0 11968.6     .05       0 12812.2     .12       0
 14449.1     .12       0 15867.1     .05       0   16431     .05       0
 16921.2     .12       0 18086.5     .12       0 19109.5     .05       0
 19115.5     .05       0 19555.2     .05       0 20611.7     .05       0
 21886.7     .05       0 24591.8     .05       0
Bank Sta=18951.85,19351.83
XS Rating Curve= 0 ,0
Exp/Cntr=0.3,0.1

Type RM Length L Ch R = 1 ,235450  ,3826.17,3826.17,3826.17
XS GIS Cut Line= 6
3721568.4738922110598426.74594653712911.4114819810589148.6053821
3710245.66550113 10587054.1328653708431.4293002210583425.6604631
3705371.5335171410579975.13980513704633.6357147210579187.2348849
#Sta/Elev= 30
       0  279.02  1562.5262.6363 2489.94  244.33  4980.9242.1244  5676.7234.7266
 6109.87  224.01  6169.4238.4953  7053.6240.2193  7624.9 238.869  9051.7234.6673
 10255.8233.3349 11382.3233.3007 12851.6231.2338 13372.4208.7448 13666.9 208.814
 14184.6211.4675 14816.8 211.395 15078.3 211.49718268.22  213.0118438.09  207.81
18577.98  178.64 18629.2178.7368 18635.2178.748218777.82  184.9518887.73  211.17
   19021211.974920875.46  251.8221444.46  239.46 24523.8249.4574 25828.1  247.78
#Mann= 20 ,-1 , 0
       0     .05       0  1562.5     .05       0  4980.9     .08       0
  5676.7     .05       0  6169.4     .16       0  7053.6     .05       0
  7624.9     .16       0  9051.7     .05       0 10255.8     .12       0
 11382.3     .05       0 12851.6     .12       0 13372.4     .07       0
 13666.9     .12       0 14184.6     .12       0 14816.8     .07       0
 15078.3     .12       0 18629.2     .05       0 18635.2     .05       0
   19021     .05       0 24523.8     .05       0
#XS Ineff= 2 , 0
         6991.96  247.08
Permanent Ineff=
       F       F
Bank Sta=18268.22,18887.73
XS Rating Curve= 0 ,0
Exp/Cntr=0.3,0.1

Type RM Length L Ch R = 1 ,231624  ,5828,5828,5828
XS GIS Cut Line= 4
3721887.4840809710598554.0606525 3714230.2448023  10590300.72086
3713555.2123597310584377.31013463698485.76776114 10573509.254443
#Sta/Elev= 30
       0   283.4   411.5   279.3    1629  264.51 2919.57   243.4  5638.8  236.31
  6199.1  240.29 6309.09  224.86 6438.71  238.64  7537.6   238.4  8749.4  234.55
  9708.6  234.03 10764.5  233.76   12790  231.88 13297.9  224.79   14018  219.29
 15033.3  213.17 18096.5  213.58 20046.3  216.5420230.28  215.7320519.57  207.42
   20580   177.2   20780   177.220835.44  204.9220860.28  215.73   20885  215.76
 22246.2  206.63 22808.2  211.27 26204.3  227.7627260.28  246.3335800.28  273.46
#Mann= 20 ,-1 , 0
       0     .05       0   411.5     .05       0    1629     .05       0
  5638.8     .05       0  7537.6     .05       0  8749.4     .12       0
  9708.6     .05       0 10764.5     .05       0   12790     .12       0
 13297.9     .05       0   14018     .05       0 15033.3     .12       0
 18096.5     .12       0 20046.3     .12       020519.57               0
20835.44     .05       0   20885     .05       0 22246.2     .12       0
 22808.2     .05       0 26204.3     .05       0
Bank Sta=20230.28,20860.28
XS Rating Curve= 0 ,0
Exp/Cntr=0.3,0.1

Type RM Length L Ch R = 1 ,225796  ,6180,6180,6180
XS GIS Cut Line= 5
3722478.8234494610599047.44910143715199.5791497210590898.8577871
3715969.5789220510581878.85778253709839.9343572310571842.5878288
3700082.9899603910568960.6434615
#Sta/Elev= 30
       0  288.14   615.4     285  2283.4   273.7 3788.78  242.62  4638.5  241.85
  4787.8  261.61 4878.42  241.85  6950.7  238.32  8617.7  236.95 10081.7  237.01
 12059.6  234.54 13900.7  218.03 16769.1  214.08 19174.6  212.24 23250.2  211.65
 23935.8  212.9425315.21  216.2825397.41  204.24   25455  175.45   25655  175.45
 25709.7   202.8 25877.6  209.9226468.39  216.13 28674.5  210.41 28772.5  200.28
 31885.2   234.1 34434.1  230.41 35731.3  227.5936946.31  262.2441912.43  272.08
#Mann= 20 ,-1 , 0
       0     .12       0   615.4     .05       0  2283.4     .05       0
  4787.8     .05       0  6950.7     .12       0  8617.7     .05       0
 10081.7     .05       0 12059.6     .16       0 13900.7     .05       0
 16769.1     .12       0 19174.6     .05       0 23250.2     .05       0
 23935.8     .12       025397.41               0 25709.7     .07       0
 25877.6     .05       0 28674.5     .05       0 31885.2     .05       0
 34434.1     .05       0 35731.3     .05       0
Bank Sta=25315.21,26468.39
XS Rating Curve= 0 ,0
Exp/Cntr=0.3,0.1

Type RM Length L Ch R = 1 ,219616  ,9063,9063,9063
XS GIS Cut Line= 4
 3722582.989907810598665.50465533715673.2678348910590957.1713187
3718201.4881721310572718.28850523700352.0871912210568318.2822134
#Sta/Elev= 30
       0  285.32   528.2  285.82 3437.31  243.81  5635.8  237.09    6829  237.01
  7576.6  236.17  9164.4  235.46    9718  234.92 11474.6  222.48 14026.9  217.19
 16355.7  210.84 18629.2  210.78 24608.7  211.07 25109.5  211.68 26351.5  212.74
27234.81  208.5627250.11  208.54   27320   173.6   27520   173.627576.08  201.64
27585.17  204.2427634.16  229.08 28260.9  232.8533732.77  225.1235112.23  200.14
 35456.7  235.07 40406.8  229.83 41584.2  227.08 43119.1  256.4647147.52  272.08
#Mann= 20 ,-1 , 0
       0     .05       0   528.2     .05       0  5635.8     .05       0
    6829     .12       0  7576.6     .05       0  9164.4     .12       0
    9718     .05       0 11474.6     .12       0 14026.9     .05       0
 16355.7     .12       0 18629.2     .05       0 24608.7     .05       0
 25109.5     .07       0 26351.5     .07       027250.11               0
27576.08     .05       0 28260.9     .05       0 35456.7     .05       0
 40406.8     .05       0 41584.2     .05       0
Bank Sta=27234.81,27585.17
XS Rating Curve= 0 ,0
Exp/Cntr=0.3,0.1

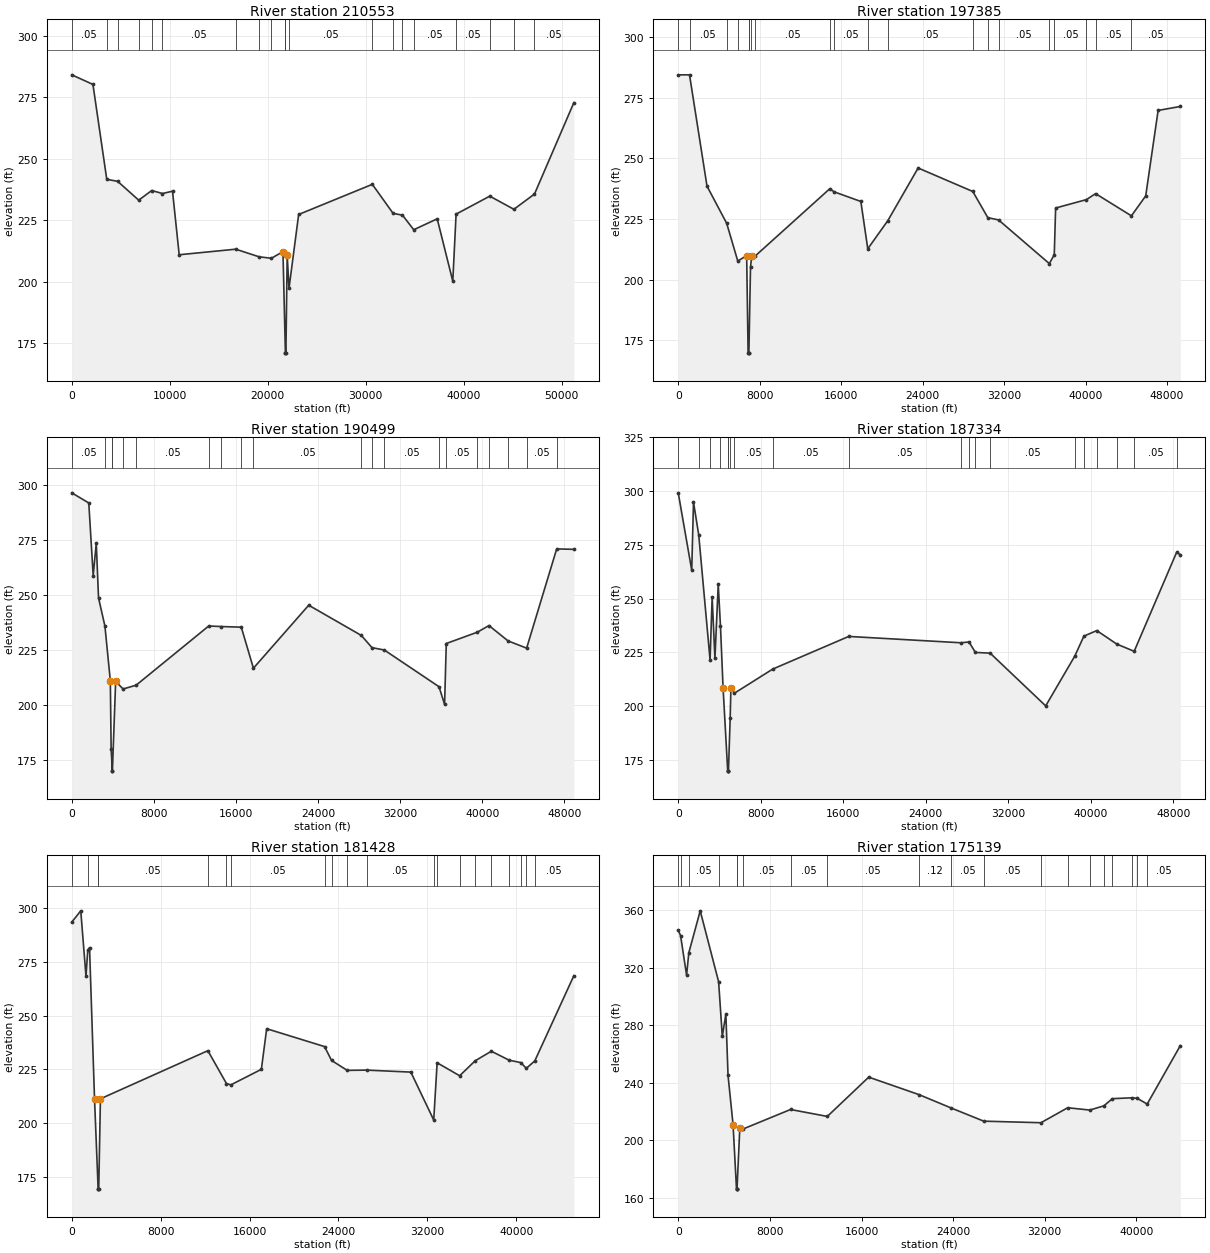
Type RM Length L Ch R = 1 ,210553  ,13168.14,13168.14,13168.14
XS GIS Cut Line= 5
3722652.4343227110598214.1157943 3716194.101110810590991.8933621
 3723615.976030810577866.89336553719666.3234970610572398.1434762
3700612.5039932110567363.4212622
#Sta/Elev= 30
       0  284.04 2159.71  280.14  3570.3241.5517  4685.1240.7231  6830.1233.0722
  8155.3236.9944  9252.5235.781210278.58  236.7210958.52  210.88   16727 213.143
 19106.3210.0525 20363.6209.444421546.98  212.16 21793.2170.9391 21799.2170.9325
21846.92  170.8821976.89  210.78 22162.7197.251823146.67  227.25 30662.5239.5152
 32783.7227.6984 33741.1226.9796 34888.6221.050137282.23  225.4938872.23  200.13
   39209227.3992 42644.5234.7122 45105.4229.3693 47206.6235.559951222.23  272.71
#Mann= 20 ,-1 , 0
       0     .05       0  3570.3     .05       0  4685.1     .05       0
  6830.1     .12       0  8155.3     .05       0  9252.5     .05       0
   16727     .07       0 19106.3     .05       0 20363.6     .05       0
 21793.2     .05       0 21799.2     .05       0 22162.7     .05       0
 30662.5     .05       0 32783.7     .05       0 33741.1     .05       0
 34888.6     .05       0   39209     .05       0 42644.5     .05       0
 45105.4     .05       0 47206.6     .05       0
Bank Sta=21546.98,21976.89
XS Rating Curve= 0 ,0
Exp/Cntr=0.3,0.1

Type RM Length L Ch R = 1 ,197385  ,6885.54,6885.54,6885.54
XS GIS Cut Line= 6
3722652.4343227110597762.72693333719631.6011255510594290.5045471
3723555.2123728110587693.28250533724596.8789246410578005.7825234
 3719874.656741810572172.44904573700777.4344376310566998.8380019
#Sta/Elev= 30
       0  284.42  1107.4284.4335 2825.32  238.57  4756.7223.2795  5847.6207.7151
 6721.21  209.96 6861.13  169.78  6932.6169.8125  6938.6169.8152  7099.3 205.215
 7215.41   209.9  7561.8209.8061   14889237.5174 15301.3236.239517934.46  232.26
   18615212.7658   20587224.3774 23560.9  246.05 28930.4236.3719 30408.2225.5735
 31455.9224.6673 36445.6206.6646 36931.6 210.33437065.19  229.56 40096.5233.0328
 40987.5235.4924 44507.8226.339845911.95  234.55 47131.5  269.77 49310.7   271.4
#Mann= 20 ,-1 , 0
       0     .05       0  1107.4     .05       0  4756.7     .12       0
  5847.6     .05       0  6932.6     .05       0  6938.6     .05       0
  7099.3     .12       0  7561.8     .05       0   14889     .07       0
 15301.3     .05       0   18615     .05       0   20587     .05       0
 28930.4     .05       0 30408.2     .12       0 31455.9     .05       0
 36445.6     .05       0 36931.6     .05       0 40096.5     .05       0
 40987.5     .05       0 44507.8     .05       0
Bank Sta=6721.21,7215.41
XS Rating Curve= 0 ,0
Exp/Cntr=0.3,0.1

Type RM Length L Ch R = 1 ,190499  ,3165.02,3165.02,3165.02
XS GIS Cut Line= 6
3728638.6132952110598192.73690013727835.6621452110596868.9521461
3723799.2036827210587667.56339663724775.7660340510577945.3410432
3719979.7592218810572020.8620786 3700752.328844810566704.0216624
#Sta/Elev= 30
       0  296.34 1658.24  291.73 2088.15  258.68 2388.09  273.51 2608.04  248.55
  3230.7235.7656  3757.8  210.92 3837.78  179.85  3954.3169.8044  3960.3169.7988
 4277.68  210.58  5005.6207.1495    6272208.8715 13349.8235.7913 14547.3235.5457
 16522.2235.2578 17705.5216.593223095.36  245.24 28229.4231.4821 29260.9225.9526
 30465.3224.8663 35794.7 208.18936339.59  200.14 36505.4 227.823 39532.6232.9729
 40667.8235.9888 42530.2229.0003 44337.6225.7208 47266.7270.833148939.59  270.65
#Mann= 20 ,-1 , 0
       0     .05       0  3230.7     .16       0  3954.3     .05       0
  3960.3     .05       0  5005.6     .05       0    6272     .05       0
 13349.8     .05       0 14547.3     .05       0 16522.2     .05       0
 17705.5     .05       0 28229.4     .05       0 29260.9     .12       0
 30465.3     .05       0 35794.7     .05       0 36505.4     .05       0
 39532.6     .05       0 40667.8     .05       0 42530.2     .05       0
 44337.6     .05       0 47266.7     .05       0
Bank Sta=3757.8,4277.68
XS Rating Curve= 0 ,0
Exp/Cntr=0.3,0.1

Type RM Length L Ch R = 1 ,187334  ,5905.97,5905.97,5905.97
XS GIS Cut Line= 5
3732131.6010598810595436.33788533724041.3232772210587658.5601338
3724978.82337072 10577901.6157373720256.6011878810571998.8378444
3700951.0456389610566443.2823545
#Sta/Elev= 30
       0  299.17 1309.14  263.18 1479.02  294.86  1987.6 279.559  3085.6221.5318
 3287.82  250.64 3557.63  222.22 3877.42  256.62  4095.3237.2036 4348.25  208.45
 4796.81  169.82  4861.5  169.82  4867.5  169.82  5034.4194.3293  5106.6  208.33
  5451.4206.0596  9162.8 217.256 16526.7232.4239 27415.2229.4753 28192.3 229.846
   28808224.9818 30236.6224.667835623.65  200.14 38447.4223.3258 39326.2232.5649
 40575.2235.1406 42512.3 228.879 44201.2225.5086 48310.2271.449948673.65  270.47
#Mann= 20 ,-1 , 0
       0     .05       0  1987.6     .16       0  3085.6     .16       0
  4095.3     .12       0  4861.5     .05       0  4867.5     .05       0
  5034.4     .12       0  5451.4     .05       0  9162.8     .05       0
 16526.7     .05       0 27415.2     .12       0 28192.3     .05       0
   28808     .12       0 30236.6     .05       0 38447.4     .12       0
 39326.2     .05       0 40575.2     .05       0 42512.3     .05       0
 44201.2     .05       0 48310.2     .05       0
Bank Sta=4348.25,5106.6
XS Rating Curve= 0 ,0
Exp/Cntr=0.3,0.1

Type RM Length L Ch R = 1 ,181428  ,6289.43,6289.43,6289.43
XS GIS Cut Line= 5
3734457.9901078810588353.00461113724701.0457110610584568.2825217
3725256.6010303810577693.28249223720395.4900177110571755.7822281
3701228.8232986310565540.5046325
#Sta/Elev= 30
       0  293.62  809.63  298.89 1279.42  268.42    1441280.6341 1599.28  281.76
 2049.07  211.19  2373.9169.3983  2379.9169.3859 2426.65  169.29 2578.83  211.35
 12248.5233.7623 13924.5218.4284 14325.2 217.86417062.69  225.0817542.44  243.99
 22751.3235.6683 23378.1 229.223 24790.4 224.587 26529.5224.714730516.58  223.79
 32575.3201.4785 32883.1228.1223 34909.4222.0909 36301.8229.0304 37759.2233.5123
 39360.6229.3474 40415.3228.2111   40907225.5372   41670228.985145186.57  268.68
#Mann= 20 ,-1 , 0
       0     .16       0    1441     .12       0  2373.9     .05       0
  2379.9     .05       0 12248.5     .05       0 13924.5     .05       0
 14325.2     .05       0 22751.3     .16       0 23378.1     .12       0
 24790.4     .05       0 26529.5     .05       0 32575.3     .16       0
 32883.1     .05       0 34909.4     .12       0 36301.8     .05       0
 37759.2     .05       0 39360.6     .05       0 40415.3     .12       0
   40907     .07       0   41670     .05       0
Bank Sta=2049.07,2578.83
XS Rating Curve= 0 ,0
Exp/Cntr=0.3,0.1

Type RM Length L Ch R = 1 ,175139  ,6916.82,6916.82,6916.82
XS GIS Cut Line= 5
3739805.2123530510583561.33801333725534.3790181410578873.8378739
 3725360.767816810577103.00447333720846.8788787110571339.1157386
3702374.6566368810564464.1157091
#Sta/Elev= 30
       0   345.9   204.2342.2524  729.56  314.71   923.8330.3076 1918.84   359.5
  3525.3310.1625 3847.69  272.14  4157.5  287.64 4347.39  244.99 4787.12  210.69
 5086.94  165.85  5124.3  165.85  5130.3  165.85 5376.76  208.52  5652.7207.6753
  9804.3221.2613   13015216.442116630.41  243.77 21022.5231.6021 23852.6222.2249
 26670.6213.1463 31666.6212.0567 34003.6222.4802 35931.7220.8682 37159.5 223.806
   37900228.7894 39572.6229.3931   40054229.0784 40941.4225.070543833.11  265.69
#Mann= 20 ,-1 , 0
       0     .05       0   204.2     .16       0   923.8     .05       0
  3525.3     .16       0  5124.3     .05       0  5130.3     .05       0
  5652.7     .05       0  9804.3     .05       0   13015     .05       0
 21022.5     .12       0 23852.6     .05       0 26670.6     .05       0
 31666.6     .05       0 34003.6     .05       0 35931.7     .12       0
 37159.5     .05       0   37900     .05       0 39572.6     .05       0
   40054     .12       0 40941.4     .05       0
Bank Sta=4787.12,5376.76
XS Rating Curve= 0 ,0
Exp/Cntr=0.3,0.1

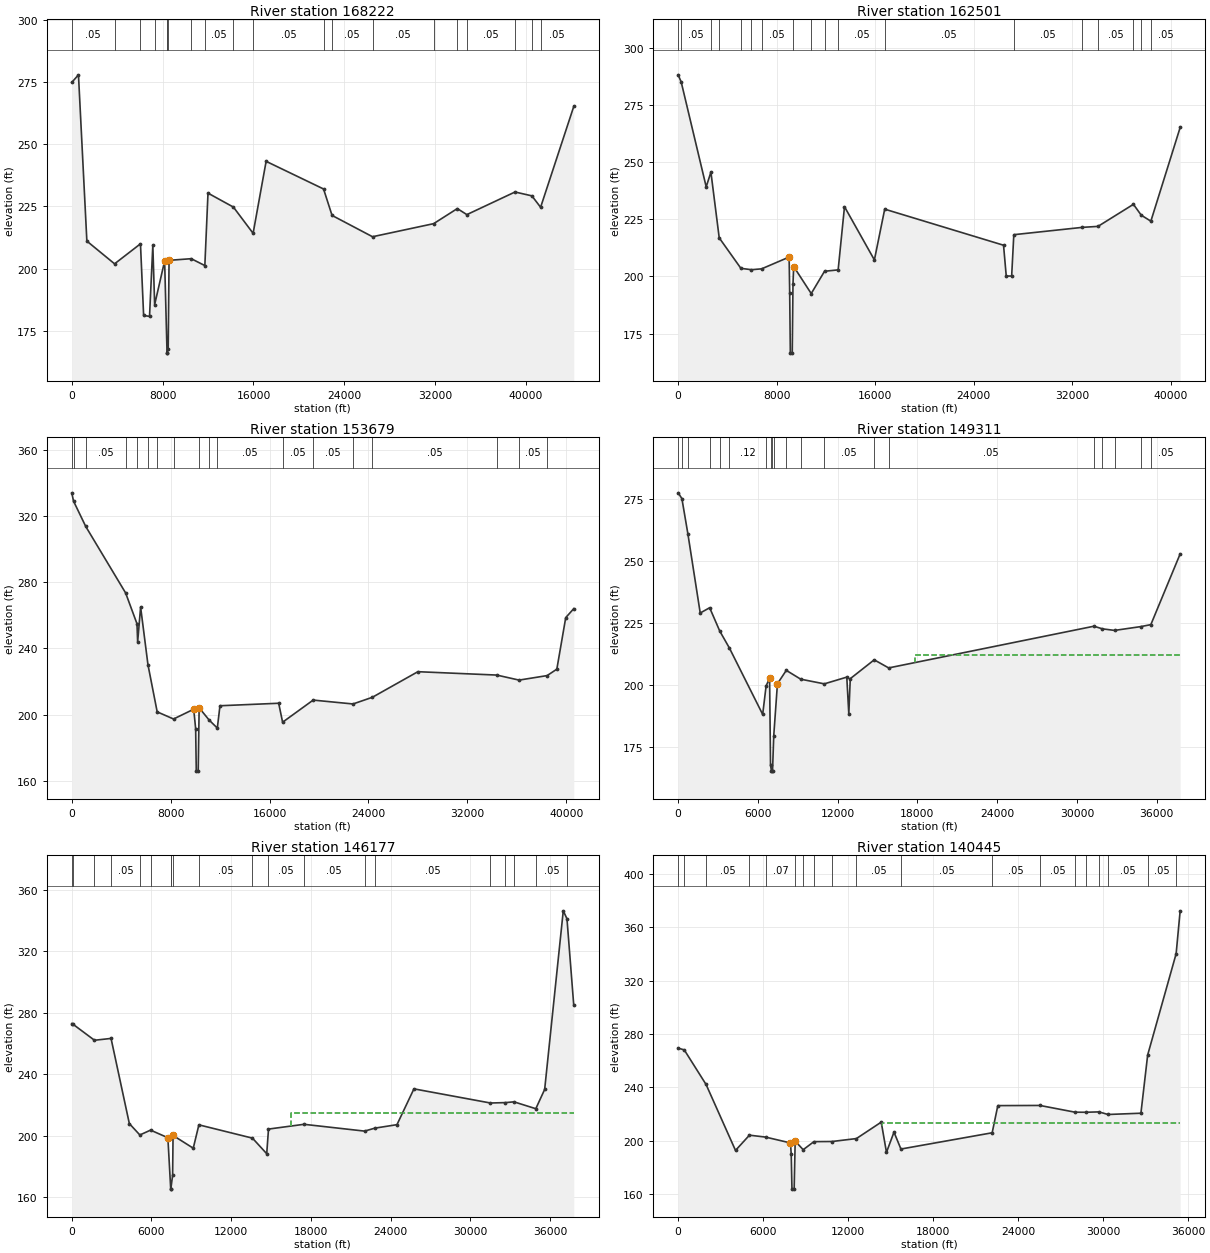
Type RM Length L Ch R = 1 ,168222  ,5721.15,5721.15,5721.15
XS GIS Cut Line= 4
3742374.6566892110574811.33779683725638.5454764710576894.6712286
3721298.2677397110571200.2269088 3702478.823423310563908.5600617
#Sta/Elev= 30
       0     275  589.84  278.07 1329.63  211.05  3769.7201.8822  6050.3  209.95
 6328.21  181.07 6848.06   180.7 7137.98  209.36  7298.7185.4194 8177.68  203.04
  8390.9165.9017  8396.9165.8867  8491.5167.4253 8567.57  203.29   10520203.9527
   11719201.180111996.56  230.38 14236.1224.7476 15969.6214.178117115.18   243.2
 22172.8232.0539 22921.5221.3987 26485.8212.8046 31866.7218.0749 33951.8224.1522
 34792.6221.7203 39033.1230.8372 40519.7229.2823 41286.5224.6771 44207.3  265.33
#Mann= 20 ,-1 , 0
       0     .05       0  3769.7     .05       0  6050.3     .12       0
  7298.7     .05       0  8390.9     .05       0  8396.9     .05       0
  8491.5     .12       0   10520     .12       0   11719     .05       0
 14236.1     .12       0 15969.6     .05       0 22172.8     .05       0
 22921.5     .05       0 26485.8     .05       0 31866.7     .05       0
 33951.8     .12       0 34792.6     .05       0 39033.1     .05       0
 40519.7     .12       0 41286.5     .05       0
Bank Sta=8177.68,8567.57
XS Rating Curve= 0 ,0
Exp/Cntr=0.3,0.1

Type RM Length L Ch R = 1 ,162501  ,8821.69,8821.69,8821.69
XS GIS Cut Line= 4
3741194.1013075610568561.33782963726819.1011862210572484.9490769
3713659.37881805 10566026.6158653702756.6010829710563387.7267858
#Sta/Elev= 30
       0  288.25   249.2  285.08  2278.6   239.2  2660.4  245.66  3335.4  216.88
  5096.6  203.53  5957.3  202.93  6779.1  203.31 9014.47  208.47 9060.06  192.63
  9112.5  166.41  9267.5  166.41 9328.09   196.7 9384.25  204.33 10809.2  192.49
 11890.3  202.25 12996.4  202.8613511.83  230.5215940.92  207.21 16778.5  229.44
26430.87  213.6526650.98  200.1627090.87  200.16 27265.7  218.26 32834.4  221.47
 34104.5   221.9   36982  231.56 37615.3  226.81   38398  224.1840777.82   265.2
#Mann= 19 ,-1 , 0
       0     .05       0   249.2     .05       0  2660.4     .16       0
  3335.4     .05       0  5096.6     .12       0  5957.3     .05       0
  6779.1     .05       0 9060.06               0 9328.09     .12       0
 10809.2     .12       0 11890.3     .12       0 12996.4     .05       0
 16778.5     .05       0 27265.7     .05       0 32834.4     .16       0
 34104.5     .05       0   36982     .05       0 37615.3     .12       0
   38398     .05       0
Bank Sta=9014.47,9384.25
XS Rating Curve= 0 ,0
Exp/Cntr=0.3,0.1

Type RM Length L Ch R = 1 ,153679  ,4368.04,4368.04,4368.04
XS GIS Cut Line= 2
 3743580.743187810566283.73805413703103.8234856410563040.5047112
#Sta/Elev= 30
       0  334.31   142.6  329.29  1131.6  313.91  4355.2  273.67  5274.8  255.01
 5329.54  243.99 5569.52  265.08  6163.5  230.18  6909.9  201.61  8233.9  197.28
 9864.24  203.2110021.05  191.43 10072.5   165.7 10227.5   165.710304.26  204.08
   11108  196.68 11773.8  191.7811988.92  205.3116738.49  206.82 17055.2  195.33
 19527.8  208.74 22750.1  206.39 24314.6  210.4327998.49  225.94 34376.6   223.9
 36185.3  220.85 38453.2  223.5839238.48  227.4739958.48   258.740608.48  264.15
#Mann= 19 ,-1 , 0
       0     .16       0   142.6     .12       0  1131.6     .05       0
  4355.2     .05       0  5274.8     .16       0  6163.5     .05       0
  6909.9     .12       0  8233.9     .05       010021.05               0
10304.26     .12       0   11108     .05       0 11773.8     .05       0
 17055.2     .05       0 19527.8     .05       0 22750.1     .05       0
 24314.6     .05       0 34376.6     .05       0 36185.3     .05       0
 38453.2     .05       0
Bank Sta=9864.24,10304.26
XS Rating Curve= 0 ,0
Exp/Cntr=0.3,0.1

Type RM Length L Ch R = 1 ,149311  ,3134,3134,3134
XS GIS Cut Line= 2
3741013.54556631 10563186.3380813703270.4901470510561797.4491265
#Sta/Elev= 30
       0  277.55   281.6275.2295   736.6 260.869 1659.94   229.1  2370.2 231.223
    3131221.8101  3857.4214.9641 6359.76  188.21  6618.7 199.739 6879.75  202.76
 6949.74  167.89    7018165.3565    7024165.3561 7099.74  165.35  7191.8179.5805
 7469.73  200.58  8135.7205.9789  9221.3 202.419 10996.2200.534612687.41  203.25
 12839.7  188.42 12949.7  202.62 14751.3 210.222 15838.3  206.96 31279.3223.7694
 31922.5222.7134 32835.1222.0816 34811.8223.6201 35564.1224.4108 37769.7  252.93
#Mann= 20 ,-1 , 0
       0     .05       0   281.6     .12       0   736.6     .16       0
  2370.2     .12       0    3131     .05       0  3857.4     .12       0
  6618.7     .07       0    7018     .05       0    7024     .05       0
  7191.8     .12       0  8135.7     .16       0  9221.3      .1       0
 10996.2     .05       0 14751.3     .05       0 15838.3     .05       0
 31279.3     .12       0 31922.5     .05       0 32835.1     .05       0
 34811.8     .16       0 35564.1     .05       0
#XS Ineff= 2 , 0
                        17785.09          212.25
Permanent Ineff=
       F       F
Bank Sta=6879.75,7469.73
XS Rating Curve= 0 ,0
Exp/Cntr=0.3,0.1

Type RM Length L Ch R = 1 ,146177  ,5732,5732,5732
XS GIS Cut Line= 3
3740874.6567364610562283.56003093737714.9343813810560061.3377693
3703860.7678378810558012.7267091
#Sta/Elev= 30
       0  273.05    77.5 272.755  1709.4 262.227  2956.3263.4223 4332.87     208
  5123.4200.5898  5930.4203.7487 7232.57   198.8  7447.5  165.35  7453.5  165.35
  7589.7 174.361 7622.53  200.28 9142.38  191.99  9566.5207.1829 13598.9198.5262
14671.84   188.4   14805204.4262 17473.7207.5356 22034.5203.1087 22811.1205.0394
24473.03   207.325749.84   230.6   31509221.3943 32640.4221.6577   33279222.1536
 34922.1217.685135588.47  230.2536988.47  346.46 37266.3341.309537778.47  284.86
#Mann= 20 ,-1 , 0
       0     .12       0    77.5     .05       0  1709.4     .05       0
  2956.3     .05       0  5123.4     .05       0  5930.4     .12       0
  7447.5     .05       0  7453.5     .05       0  7589.7     .12       0
  9566.5     .05       0 13598.9     .12       0   14805     .05       0
 17473.7     .05       0 22034.5     .05       0 22811.1     .05       0
   31509     .12       0 32640.4     .16       0   33279     .05       0
 34922.1     .05       0 37266.3     .12       0
#XS Ineff= 2 , 0
                        16480.54          215.08
Permanent Ineff=
       F       F
Bank Sta=7232.57,7622.53
XS Rating Curve= 0 ,0
Exp/Cntr=0.3,0.1

Type RM Length L Ch R = 1 ,140445  ,9271,9271,9271
XS GIS Cut Line= 3
3738201.0456138810555200.2267566 3728201.045600810559158.5600473
3703687.1566365510556311.3380515
#Sta/Elev= 30
       0  269.49     432  268.14  1970.9  242.23 4048.11   192.8  5031.1  204.23
  6170.7   202.8 7926.25  198.41  7980.7  190.19  8033.5  163.79  8188.5  163.79
 8260.48  199.78  8826.7  193.34  9582.7  199.38 10862.9  199.49 12583.4  201.69
14334.63  214.0114704.61  191.3615234.57  206.51   15725  193.84 22165.3  206.03
 22564.5  226.39 25536.9  226.51 28014.6  221.46   28768  221.41 29699.5  221.69
 30343.7  219.74 32664.5  220.69 33141.6  264.36 35150.5  340.25 35434.5   372.4
#Mann= 20 ,-1 , 0
       0     .12       0     432     .16       0  1970.9     .05       0
  5031.1     .07       0  6170.7     .07       0  7980.7               0
 8260.48     .05       0  8826.7     .05       0  9582.7     .05       0
 10862.9     .12       0 12583.4     .05       0   15725     .05       0
 22165.3     .05       0 25536.9     .05       0 28014.6     .12       0
   28768     .16       0 29699.5     .05       0 30343.7     .05       0
 33141.6     .05       0 35150.5     .05       0
#XS Ineff= 2 , 0
                        14385.59          212.99
Permanent Ineff=
       F       F
Bank Sta=7926.25,8260.48
XS Rating Curve= 0 ,0
Exp/Cntr=0.3,0.1

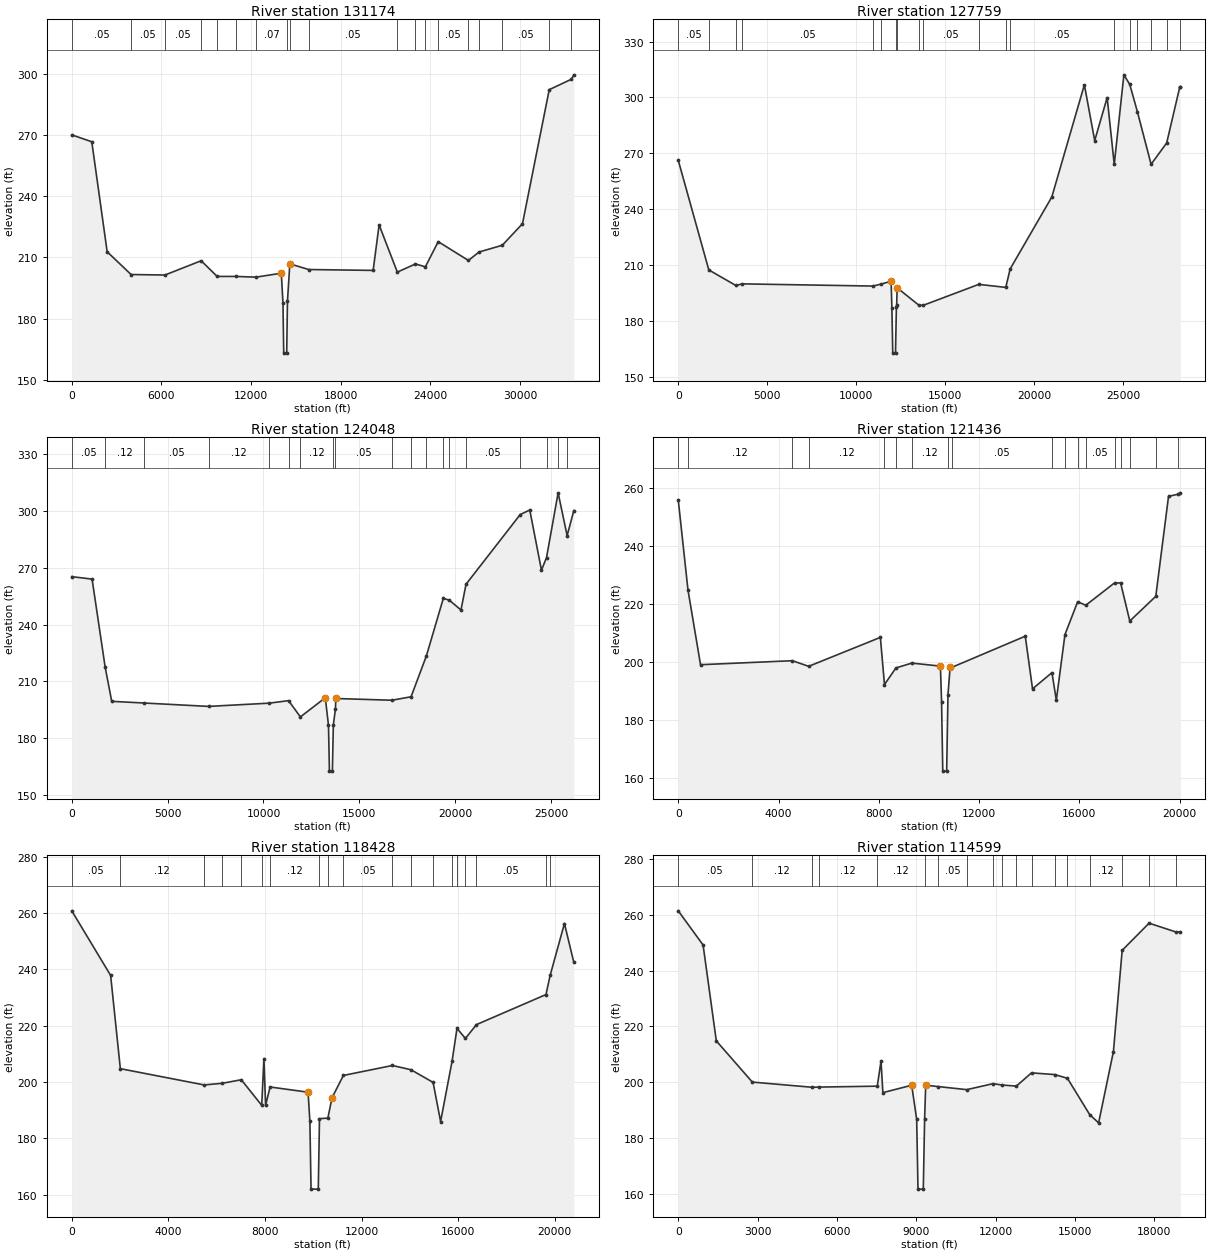
Type RM Length L Ch R = 1 ,131174  ,3415.05,3415.05,3415.05
XS GIS Cut Line= 3
3737020.4899041410554679.39348073721741.1356203910556476.9643606
3703582.99017821 10554922.449097
#Sta/Elev= 30
       0  270.19 1339.54  266.82 2369.19  212.81  3968.3  201.64  6237.7  201.39
  8660.7   208.4  9733.3   200.7 10988.9   200.7 12330.3  200.3514025.42  202.28
14138.16  187.47   14187  163.05   14387  163.0514437.87  188.4914595.25  206.72
 14606.7  206.86 15857.2  204.0920173.24  203.6620573.09  225.99 21792.6  202.82
 23007.5  206.83 23670.3  205.41 24528.3  217.77 26550.6  208.55 27265.2   212.7
 28816.1  215.9930169.34  226.57 31961.1  292.39 33449.7  297.5233607.99  299.67
#Mann= 20 ,-1 , 0
       0     .05       0  3968.3     .05       0  6237.7     .05       0
  8660.7     .12       0  9733.3     .07       0 10988.9     .07       0
 12330.3     .07       014138.16               014437.87     .05       0
 14606.7     .05       0 15857.2     .05       0 21792.6     .12       0
 23007.5     .05       0 23670.3     .05       0 24528.3     .05       0
 26550.6     .12       0 27265.2     .05       0 28816.1     .05       0
 31961.1     .05       0 33449.7     .05       0
Bank Sta=14025.42,14595.25
XS Rating Curve= 0 ,0
Exp/Cntr=0.3,0.1

Type RM Length L Ch R = 1 ,127759  ,3711,3711,3711
XS GIS Cut Line= 3
3735874.6565658910554262.72666313716812.1566332110553082.1712815
 3708478.823234310549401.6156505
#Sta/Elev= 30
       0  266.33  1717.6  207.44  3238.6   199.1    3592  199.96 10944.5  198.78
 11418.5  199.8911959.31  201.37 12003.8  187.13 12052.5  162.78 12207.5  162.78
12256.95  187.51 12272.3  188.3512299.29  197.84 13525.1  188.48 13764.3  188.44
 16884.9  199.69 18402.6  198.06 18650.3  208.0120988.98  246.5922818.98  306.81
23398.98  276.8624098.98  299.95 24496.7  264.0825038.98  312.17 25370.5  306.98
   25801  292.23 26566.8  264.15   27443  275.59 28181.8  305.7628208.98  305.43
#Mann= 20 ,-1 , 0
       0     .05       0  1717.6     .05       0  3238.6      .1       0
    3592     .05       0 10944.5     .12       0 11418.5     .05       0
 12003.8               012256.95     .05       0 12272.3     .12       0
 13525.1     .07       0 13764.3     .05       0 16884.9     .05       0
 18402.6     .12       0 18650.3     .05       0 24496.7     .05       0
 25370.5     .05       0   25801     .16       0 26566.8     .16       0
   27443     .16       0 28181.8     .05       0
Bank Sta=11959.31,12299.29
XS Rating Curve= 0 ,0
Exp/Cntr=0.3,0.1

Type RM Length L Ch R = 1 ,124048  ,2612.06,2612.06,2612.06
XS GIS Cut Line= 3
3734928.4760435510551489.28929663713331.2538181410550482.3447882
3708990.9760813910549058.7337903
#Sta/Elev= 30
       0  265.35 1059.54  264.06  1741.5  217.51 2083.56   199.4  3773.7  198.51
  7133.4  196.72 10295.5  198.43 11308.8  199.77 11925.6  191.1513224.42  201.31
13391.04  186.71 13439.5  162.48 13594.5  162.4813643.09  186.77 13754.1  195.45
 13774.2   200.9 16700.9  199.98 17697.8  201.81 18497.2  223.42 19379.4   253.8
 19683.2     25320301.61  247.71 20565.7  261.36 23391.5  298.2123890.13  300.62
24499.88  268.78   24765  275.45 25368.6   309.7 25839.2  287.0926189.16  300.34
#Mann= 20 ,-1 , 0
       0     .05       0  1741.5     .12       0  3773.7     .05       0
  7133.4     .12       0 10295.5     .07       0 11308.8     .07       0
 11925.6     .12       013391.04               013643.09     .05       0
 13754.1     .05       0 16700.9     .12       0 17697.8     .05       0
 18497.2     .16       0 19379.4     .05       0 19683.2     .16       0
 20565.7     .05       0 23391.5     .05       0   24765     .16       0
 25368.6     .05       0 25839.2     .16       0
Bank Sta=13224.42,13774.2
XS Rating Curve= 0 ,0
Exp/Cntr=0.3,0.1

Type RM Length L Ch R = 1 ,121436  ,3007.75,3007.75,3007.75
XS GIS Cut Line= 4
3733622.4675007210551312.61281273723726.6342740510550010.5294589
3723162.3978697210548968.86290713714493.9142224610547124.7156767
#Sta/Elev= 30
       0  255.83   388.4  224.75  889.21  198.96  4552.1  200.34  5203.2   198.4
 8062.83  208.38  8227.9  192.13  8684.8  197.85  9319.4  199.5210458.98  198.47
10504.82  186.11 10552.5  162.27 10707.5  162.2710760.09  188.5710847.23   198.3
 10939.6  198.1413843.45  208.7914133.19  190.64 14907.7  196.2215082.36  186.72
 15426.5  209.34 15933.3  220.67 16257.1  219.45 17410.2   227.2 17647.8  227.13
 18012.8  214.02 19049.6  222.5319558.74  257.01 19940.7  257.7520028.37  258.22
#Mann= 19 ,-1 , 0
       0     .05       0   388.4     .12       0  4552.1     .05       0
  5203.2     .12       0  8227.9     .05       0  8684.8     .07       0
  9319.4     .12       010504.82               010760.09     .12       0
 10939.6     .05       0 14907.7     .12       0 15426.5     .05       0
 15933.3     .16       0 16257.1     .05       0 17410.2     .05       0
 17647.8     .16       0 18012.8     .12       0 19049.6     .16       0
 19940.7     .05       0
Bank Sta=10458.98,10847.23
XS Rating Curve= 0 ,0
Exp/Cntr=0.3,0.1

Type RM Length L Ch R = 1 ,118428  ,3829.25,3829.25,3829.25
XS GIS Cut Line= 2
3734789.58721372 10551211.5116373715240.9760485610544128.1783627
#Sta/Elev= 30
       0  260.78 1609.41  237.86  2011.3  204.77    5482     199  6236.3  199.59
    7020  200.84  7866.3  191.77 7957.05  208.34 8027.02  191.85  8214.3  198.27
 9786.34  196.42 9860.85  186.04 9908.87  162.0310208.87  162.0310258.88  187.03
   10606  187.2310775.95  194.42 11248.1  202.37 13278.7   205.9 14047.5  204.39
 14963.4   199.915274.19  186.01 15750.2  207.46 15953.3  219.08 16301.1  215.49
 16759.7  220.41 19637.9  231.07 19811.8  237.9120402.19  256.2720792.04  242.47
#Mann= 20 ,-1 , 0
       0     .05       0  2011.3     .12       0    5482     .05       0
  6236.3     .05       0    7020     .12       0  7866.3     .12       0
  8214.3     .12       0 9860.85               010258.88     .05       0
   10606     .12       0 11248.1     .05       0 13278.7     .12       0
 14047.5     .05       0 14963.4     .12       0 15750.2     .16       0
 15953.3     .12       0 16301.1     .05       0 16759.7     .05       0
 19637.9     .08       0 19811.8     .05       0
Bank Sta=9786.34,10775.95
XS Rating Curve= 0 ,0
Exp/Cntr=0.3,0.1

Type RM Length L Ch R = 1 ,114599  ,3515.47,3515.47,3515.47
XS GIS Cut Line= 2
3736734.0318156310549162.9005767 3719164.587295810541975.4005161
#Sta/Elev= 30
       0   261.4  939.64  249.16 1439.45  214.82  2801.1  200.06  5055.4  198.21
  5314.7  198.27  7524.9   198.6 7667.03  207.61 7737.01  196.28 8827.18  198.93
 9014.99  186.72    9065  161.72    9265  161.72 9315.23  186.83 9356.37  198.95
  9819.9  198.46   10908  197.35 11896.2  199.48 12257.9     199 12783.8  198.62
 13356.6  203.36 14236.4  202.75 14714.6  201.42 15556.1  188.4215893.82  185.45
 16453.6     211 16784.8  247.26 17802.1  256.98 18820.3  253.8118982.61  253.89
#Mann= 19 ,-1 , 0
       0     .05       0  2801.1     .12       0  5055.4     .07       0
  5314.7     .12       0  7524.9     .12       0 9014.99               0
 9315.23     .12       0  9819.9     .05       0   10908     .05       0
 11896.2     .12       0 12257.9     .05       0 12783.8     .12       0
 13356.6     .05       0 14236.4     .16       0 14714.6     .12       0
 15556.1     .12       0 16784.8     .05       0 17802.1     .05       0
 18820.3     .16       0
Bank Sta=8827.18,9356.37
XS Rating Curve= 0 ,0
Exp/Cntr=0.3,0.1

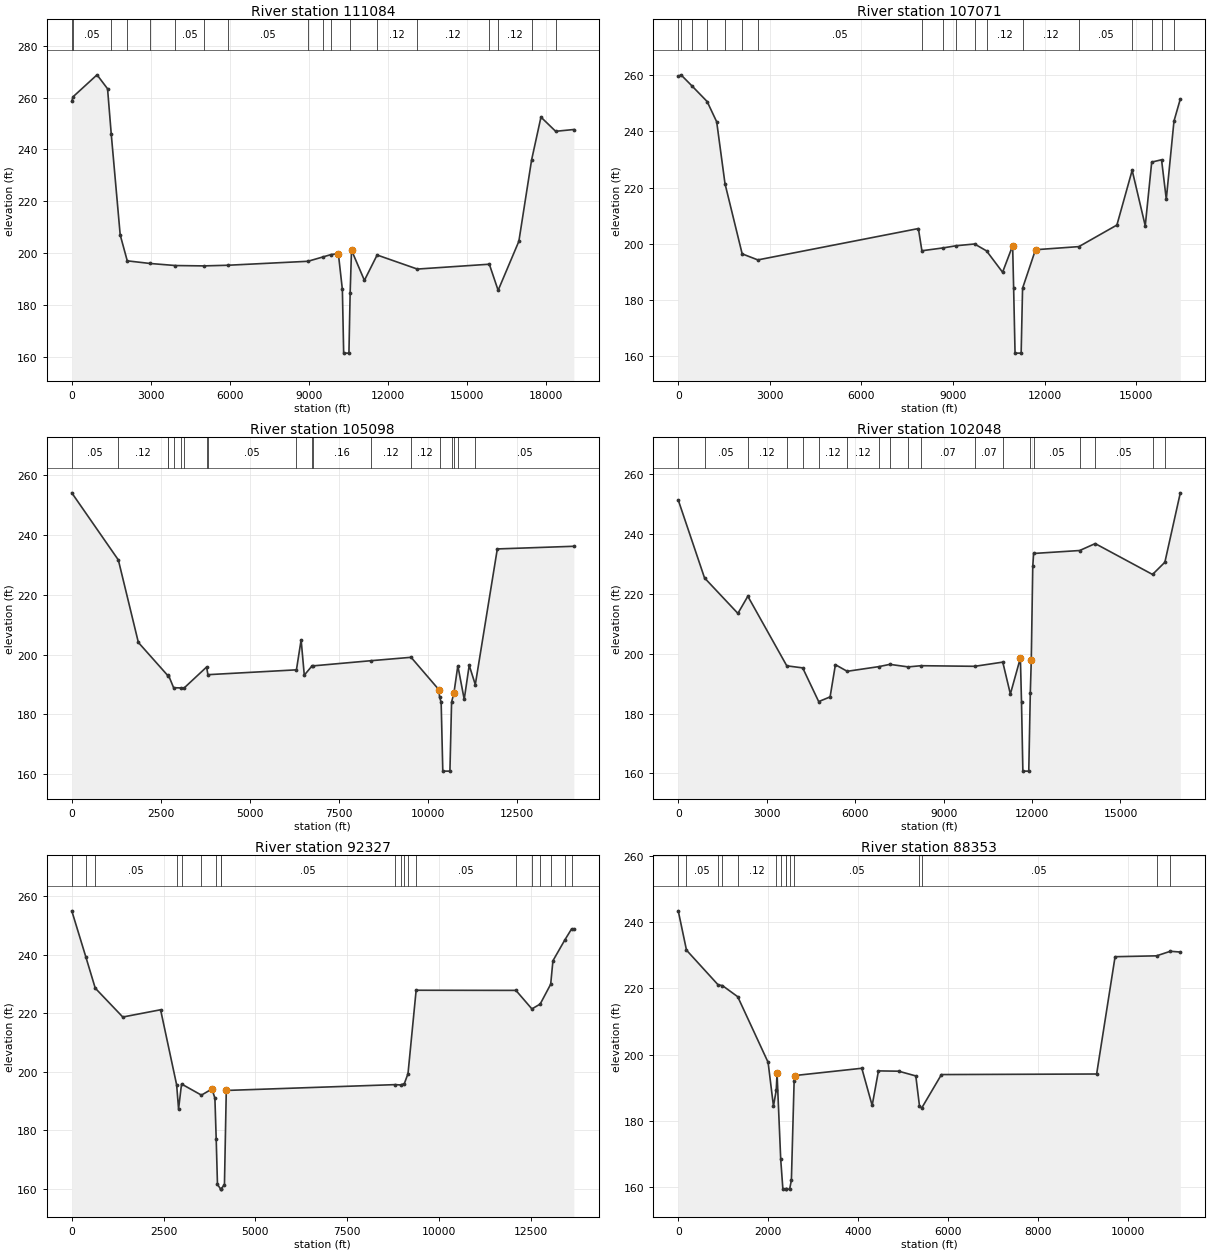
Type RM Length L Ch R = 1 ,111084  ,4012.52,4012.52,4012.52
XS GIS Cut Line= 3
3739824.3094277210541732.34489983724234.0315532210542808.7338232
3721217.6891607210541138.7194466
#Sta/Elev= 30
       0  258.62    51.6  260.33  959.84  268.77 1359.77  263.39  1498.8  246.04
 1839.69  207.04  2108.2  197.03  2971.6  196.02  3937.7  195.22  5005.8  195.08
  5928.6  195.33  8972.4  196.86  9547.3  198.55  9854.2  199.4610128.26   199.8
10280.88     186   10330  161.44   10530  161.4410576.74  184.8110628.16  201.15
11118.07   189.5 11600.6  199.28 13128.5  193.86 15863.9  195.73 16198.7  185.66
16986.33  204.58 17470.3  235.9717825.83  252.46 18383.6  246.99 19075.1  247.68
#Mann= 19 ,-1 , 0
       0     .16       0    51.6     .05       0  1498.8     .12       0
  2108.2     .05       0  2971.6     .12       0  3937.7     .05       0
  5005.8     .12       0  5928.6     .05       0  8972.4     .12       0
  9547.3     .07       0  9854.2     .12       010280.88               0
10576.74     .12       0 11600.6     .12       0 13128.5     .12       0
 15863.9     .05       0 16198.7     .12       0 17470.3     .05       0
 18383.6     .16       0
Bank Sta=10128.26,10628.16
XS Rating Curve= 0 ,0
Exp/Cntr=0.3,0.1

Type RM Length L Ch R = 1 ,107071  ,1973.21,1973.21,1973.21
XS GIS Cut Line= 3
3738157.9768023810539015.34081943727661.0958933110539342.1269112
 3721853.804358310540592.1267078
#Sta/Elev= 30
       0  259.54    90.2  260.11   454.8  256.11   945.8  250.62 1259.04  243.41
  1531.6  221.39  2093.6  196.43  2606.9  194.28 7863.94  205.43  7979.8  197.53
  8674.3  198.55  9111.4  199.33  9705.7  199.94 10095.9  197.4910621.68  189.89
10951.13  199.3310983.46  184.39   11030  161.12   11230  161.1211276.18  184.21
11699.88   197.9 13121.5  199.0114365.45  206.68 14865.5  226.1515293.91  206.39
 15505.1  229.06 15827.7   229.915982.77  215.86 16234.4  243.6416442.01  251.51
#Mann= 20 ,-1 , 0
       0     .16       0    90.2     .05       0   454.8     .05       0
   945.8     .16       0  1531.6     .12       0  2093.6     .07       0
  2606.9     .05       0  7979.8     .05       0  8674.3     .16       0
  9111.4     .16       0  9705.7     .12       0 10095.9     .12       0
10983.46               0   11070               011276.18     .12       0
 13121.5     .05       0 14865.5     .12       0 15505.1     .05       0
 15827.7     .16       0 16234.4     .05       0
Bank Sta=10951.13,11699.88
XS Rating Curve= 0 ,0
Exp/Cntr=0.3,0.1

Type RM Length L Ch R = 1 ,105098  ,3050,3050,3050
XS GIS Cut Line= 3
3737576.8309830610538498.23227363727488.5742567210537984.1811363
3723948.89924946 10536155.333088
#Sta/Elev= 30
       0  254.16    1307  231.67  1868.4  204.05  2703.2  192.84  2709.5  193.17
    2857   188.9  3054.6  188.82  3153.4  188.82    3783  195.83  3819.1  193.26
    6303  194.88  6434.5  204.92 6523.03   193.1  6741.2   196.2  6779.1  196.22
  8384.4  197.93  9518.8  199.0810301.02  188.21 10318.6   185.7 10362.8  184.06
   10409  160.96   10609  160.96 10655.2  184.06 10721.8  187.18 10830.9  196.25
11009.98     18511149.78   196.4   11321  189.9411938.62  235.3714085.47  236.26
#Mann= 20 ,-1 , 0
       0     .05       0    1307     .12       0  2703.2     .07       0
  2709.5     .12       0    2857     .07       0  3054.6     .12       0
  3153.4     .05       0    3783     .07       0  3819.1     .05       0
    6303     .16       0  6741.2     .05       0  6779.1     .16       0
  8384.4     .12       0  9518.8     .12       0 10318.6     .05       0
 10362.8               0 10655.2     .05       0 10721.8     .07       0
 10830.9     .12       0   11321     .05       0
Bank Sta=10301.02,10721.8
XS Rating Curve= 0 ,0
Exp/Cntr=0.3,0.1

Type RM Length L Ch R = 1 ,102048  ,9720.65,9720.65,9720.65
XS GIS Cut Line= 4
3737677.5079470610538177.23324363736110.9218413810537243.1140489
3727224.05575688 10535743.2906053721030.9067258810535651.6155915
#Sta/Elev= 30
       0  251.43     892  225.36 2023.78  213.49  2360.6  219.23  3682.1  195.95
  4221.3  195.26  4764.4  183.98  5151.2  185.56 5331.05  196.33  5730.9  194.12
    6809  195.69  7177.7  196.44    7800  195.59  8238.3  195.99 10058.1  195.79
 11008.4  197.1911266.03  186.51 11605.7  198.5711643.82  183.81   11690  160.72
   11890  160.7211942.56     18711975.34  197.9412025.29   229.2 12054.3  233.54
 13617.3  234.53 14143.7  236.85 16088.1  226.52 16506.6  230.61 17030.4  253.83
#Mann= 20 ,-1 , 0
       0     .05       0     892     .05       0  2360.6     .12       0
  3682.1     .05       0  4221.3     .12       0  4764.4     .12       0
  5730.9     .12       0    6809     .07       0  7177.7     .07       0
    7800     .12       0  8238.3     .07       0 10058.1     .07       0
 11008.4     .12       011643.82               011942.56     .05       0
 12054.3     .05       0 13617.3     .08       0 14143.7     .05       0
 16088.1     .08       0 16506.6     .05       0
Bank Sta=11605.7,11975.34
XS Rating Curve= 0 ,0
Exp/Cntr=0.3,0.1

Type RM Length L Ch R = 1 ,92327   ,3974.2,3974.2,3974.2
XS GIS Cut Line= 2
3736091.6705675610532787.03240993722441.4970805510531940.6781315
#Sta/Elev= 30
       0  255.07   380.4239.4297   639.6228.6356 1389.63  218.77 2419.36  221.25
  2856.7195.5811 2909.23  187.34  2990.1195.8781  3531.8192.0703 3818.99  194.18
 3898.97     191  3933.8177.2164 3968.95  161.54  4056.1  159.94  4062.1  159.94
  4158.9  161.47 4208.89  193.67  8810.7  195.66  8960.8195.5468  9059.6196.0303
  9158.5199.4018  9380.4227.9236 12098.8227.8737 12533.4221.5445 12758.8223.1966
 13045.6229.9867 13106.4     238 13426.1245.0206   13615248.893613676.23  248.74
#Mann= 20 ,-1 , 0
       0     .16       0   380.4     .05       0   639.6     .05       0
  2856.7     .12       0  2990.1     .05       0  3531.8     .12       0
  3933.8     .05       0  4056.1     .05       0  4062.1     .05       0
  8810.7     .12       0  8960.8      .1       0  9059.6     .05       0
  9158.5     .16       0  9380.4     .05       0 12098.8     .16       0
 12533.4     .12       0 12758.8     .16       0 13045.6     .16       0
 13426.1     .05       0   13615     .16       0
Bank Sta=3818.99,4208.89
XS Rating Curve= 0 ,0
Exp/Cntr=0.3,0.1

Type RM Length L Ch R = 1 ,88353   ,6090,6090,6090
XS GIS Cut Line= 4
3735652.6783353110530392.20189773734252.8395995510529081.8820118
3732473.3257701410529190.38901263725422.9966949710531625.1863084
#Sta/Elev= 30
       0  243.41   183.5231.5456   885.9221.0887   982.9220.8465  1322.1217.4995
 1997.09  197.71 2116.61  184.48  2178.3189.3171 2196.29  194.34  2277.6168.4698
 2325.77  159.45  2386.8  159.45  2392.8  159.45  2476.2  159.45 2515.01  162.16
  2575.5191.9261 2584.73  193.71 4080.17  195.91 4310.14  184.68 4450.12  195.12
 4900.06  195.03    5280   193.6  5361.7184.5594  5410.6183.9024 5849.92  194.01
 9299.39  194.18 9709.33  229.57 10630.3229.8321 10937.5 231.20511159.08  230.98
#Mann= 15 ,-1 , 0
       0     .16       0   183.5     .05       0   885.9     .16       0
   982.9     .05       0  1322.1     .12       0  2178.3     .16       0
  2277.6     .05       0  2386.8     .05       0  2392.8     .05       0
  2476.2     .07       0  2575.5     .05       0  5361.7     .07       0
  5410.6     .05       0 10630.3     .16       0 10937.5     .05       0
Bank Sta=2196.29,2584.73
XS Rating Curve= 0 ,0
Exp/Cntr=0.3,0.1