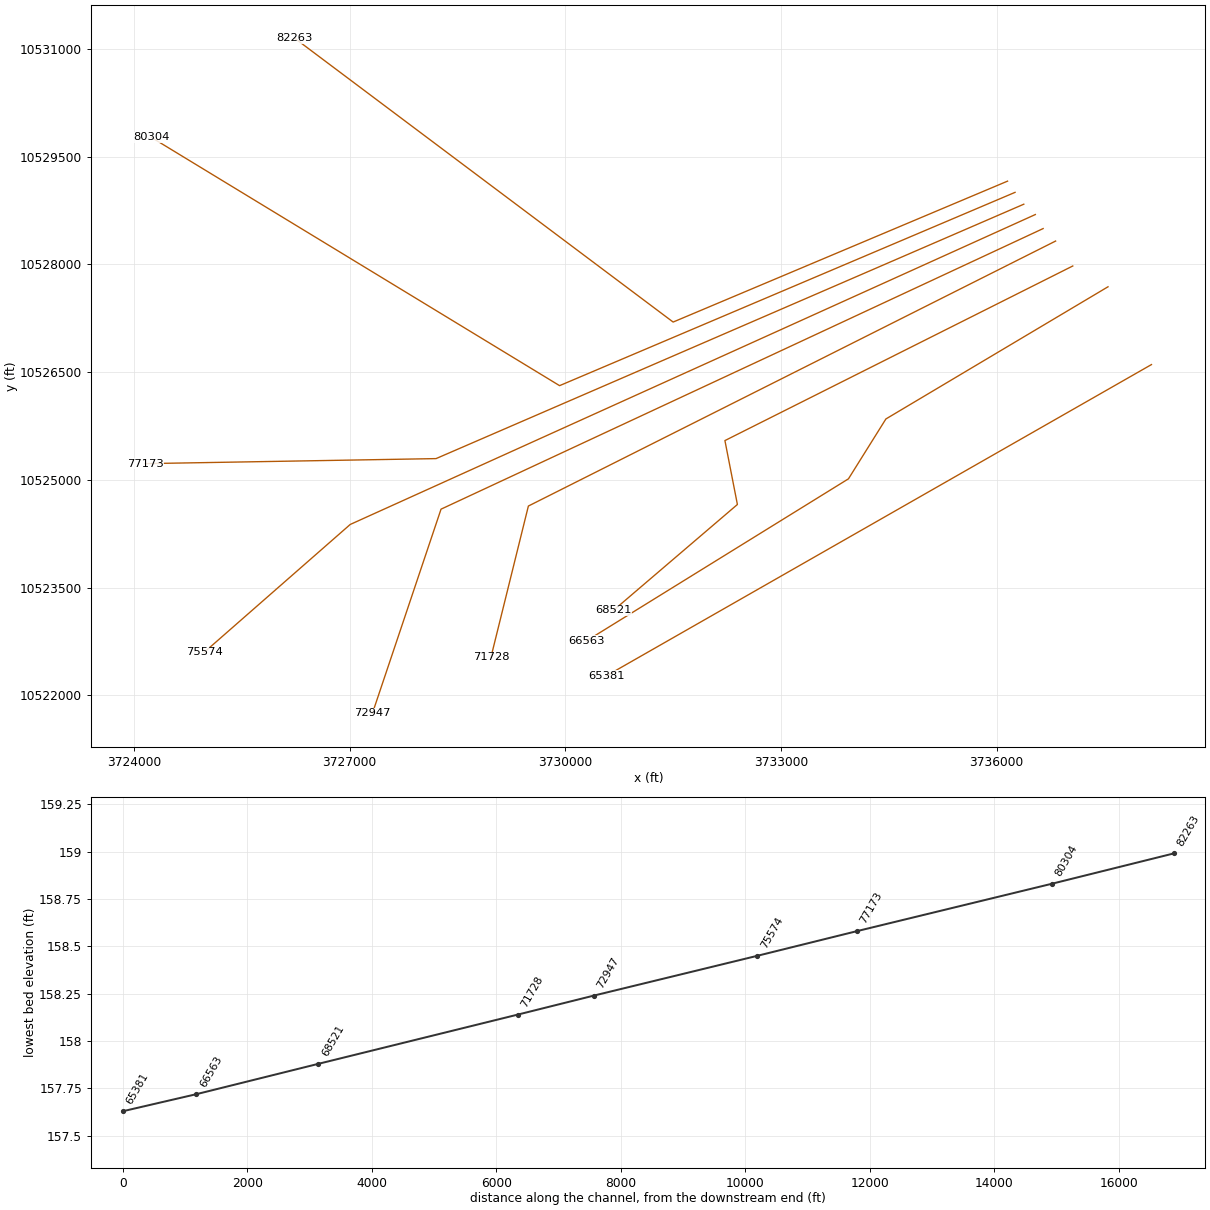
HEC-RAS study TRINITY RIVER.prj: TRINITY RIVER Base Level Engineering

--- TRINITY RIVER.g06 (geometry) --- (continued)

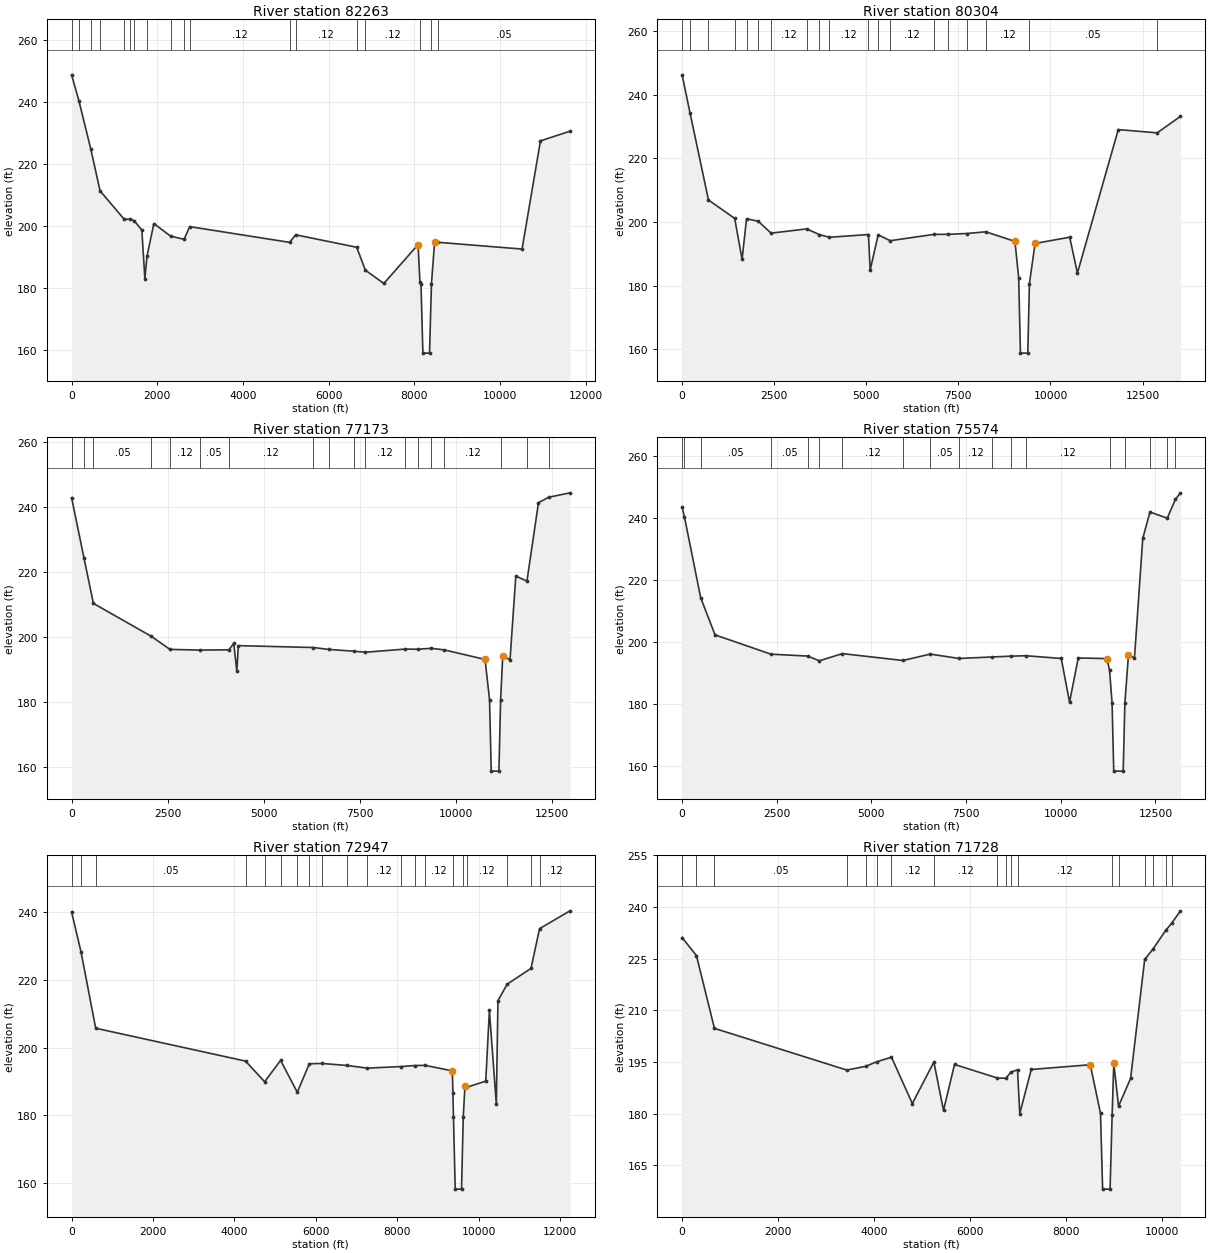
Type RM Length L Ch R = 1 ,82263   ,1959.43,1959.43,1959.43
XS GIS Cut Line= 3
3736152.1632287210529159.90843063731499.38546081 10527198.102971
3726236.1016960610531147.8641003
#Sta/Elev= 30
       0  248.85     170  240.51   446.4     225   664.4  211.38  1229.8  202.18
  1366.4  202.27  1464.2  201.72 1639.82  198.68 1709.82  183.06  1758.8  190.23
 1919.79  200.81    2309  196.78  2625.7  195.73  2756.1  199.84  5088.5  194.75
  5227.9   197.2  6653.2  193.17  6854.9  185.77 7286.22  181.48 8085.06  194.04
    8128  181.96 8152.98  181.25  8197.5  158.99  8352.5  158.99 8397.09  181.28
  8470.1  194.78  8552.8  194.77 10511.5  192.5910940.87  227.5311629.86  230.64
#Mann= 19 ,-1 , 0
       0     .05       0     170     .05       0   446.4     .12       0
   664.4     .05       0  1229.8     .12       0  1366.4     .12       0
  1464.2     .16       0  1758.8     .12       0    2309     .12       0
  2625.7     .05       0  2756.1     .12       0  5088.5     .07       0
  5227.9     .12       0  6653.2     .07       0  6854.9     .12       0
    8128     .05       0 8152.98               0 8397.09     .12       0
  8552.8     .05       0
Bank Sta=8085.06,8470.1
XS Rating Curve= 0 ,0
Exp/Cntr=0.3,0.1

Type RM Length L Ch R = 1 ,80304   ,3131.37,3131.37,3131.37
XS GIS Cut Line= 3
3736256.33001514 10529003.6584153729919.5244473110526312.6864347
3724242.4409852210529767.5473071
#Sta/Elev= 30
       0  246.27   217.3  234.19     716  206.94    1428  201.16  1628.7  188.26
  1748.8  201.05  2067.5  200.27  2416.2  196.53  3380.9  197.85  3726.3  196.08
  3997.9  195.23  5058.4  196.09 5105.93  184.96  5323.4  195.99  5649.4  194.15
  6832.2  196.14  7207.1  196.15  7732.7  196.41    8243  196.96 9035.86  193.93
 9137.81  182.43    9185  158.83    9385  158.83 9428.72  180.69 9582.75  193.29
10522.12  195.2510731.98  183.9811841.24  229.06 12896.3  228.0413530.11  233.22
#Mann= 20 ,-1 , 0
       0     .05       0   217.3     .12       0     716     .05       0
    1428     .16       0  1748.8     .05       0  2067.5     .16       0
  2416.2     .12       0  3380.9     .05       0  3726.3     .16       0
  3997.9     .12       0  5058.4     .12       0  5323.4     .12       0
  5649.4     .12       0  6832.2     .05       0  7207.1     .05       0
  7732.7     .16       0    8243     .12       0 9137.81               0
 9428.72     .05       0 12896.3     .05       0
Bank Sta=9035.86,9582.75
XS Rating Curve= 0 ,0
Exp/Cntr=0.3,0.1

Type RM Length L Ch R = 1 ,77173   ,1598.91,1598.91,1598.91
XS GIS Cut Line= 3
3736377.8576592210528838.72797063728200.7742758810525297.0611694
3724154.9385355610525227.0741047
#Sta/Elev= 30
       0  242.89   323.6   224.2   567.1  210.29  2072.7  200.14  2557.1  196.11
  3328.3   195.9  4090.2  195.98 4215.81  197.95 4295.73  189.44 4335.69  197.27
  6283.7  196.69  6679.4  196.11  7330.1  195.56  7633.2  195.23  8674.2  196.21
  9004.2  196.16  9353.7  196.45  9693.4  195.9510749.51  193.0110865.96   180.6
   10910  158.58   11110  158.5811153.78  180.47 11209.1  194.0911398.93  192.93
 11548.8  218.72 11838.4  217.1612138.28  241.35   12404  243.0112957.56  244.38
#Mann= 20 ,-1 , 0
       0     .05       0   323.6     .12       0   567.1     .05       0
  2072.7     .16       0  2557.1     .12       0  3328.3     .05       0
  4090.2     .12       0  6283.7     .12       0  6679.4     .05       0
  7330.1     .16       0  7633.2     .12       0  8674.2     .16       0
  9004.2     .05       0  9353.7     .16       0  9693.4     .12       0
10865.96               0   11070               011153.78     .12       0
 11838.4     .05       0   12404     .16       0
Bank Sta=10749.51,11209.1
XS Rating Curve= 0 ,0
Exp/Cntr=0.3,0.1

Type RM Length L Ch R = 1 ,75574   ,2627,2627,2627
XS GIS Cut Line= 3
3736538.4478892210528694.77550263727006.5312575510524380.1679901
3724975.6849255610522600.7719426
#Sta/Elev= 30
       0  243.45    63.2  240.27   489.9  214.34  869.41  202.33  2346.7  196.11
  3316.7   195.5    3623  193.98  4234.8  196.29  5831.9  194.08  6554.8  196.14
  7315.3  194.73  8197.4  195.22  8681.2  195.47  9078.6  195.6110013.21  194.73
10233.06  180.66 10462.9  194.8911220.12  194.69 11289.9  190.8911356.28  180.31
   11400  158.45   11650  158.4511693.72  180.3111788.04  195.7811947.46   194.9
12166.66   233.4 12356.5  241.89 12813.3   239.9 13026.2  245.93   13163  248.07
#Mann= 19 ,-1 , 0
       0     .05       0    63.2     .12       0   489.9     .05       0
  2346.7     .05       0  3316.7     .16       0    3623     .05       0
  4234.8     .12       0  5831.9     .16       0  6554.8     .05       0
  7315.3     .12       0  8197.4     .16       0  8681.2     .16       0
  9078.6     .12       0 11289.9     .05       011356.28               0
11693.72     .12       0 12356.5     .16       0 12813.3     .16       0
 13026.2     .05       0
Bank Sta=11220.12,11788.04
XS Rating Curve= 0 ,0
Exp/Cntr=0.3,0.1

Type RM Length L Ch R = 1 ,72947   ,1219.15,1219.15,1219.15
XS GIS Cut Line= 3
3736646.9548900610528499.4629011 3728270.218690810524593.2128396
3727315.3577396410521750.3310581
#Sta/Elev= 30
       0  240.04   230.5  228.34   592.1  205.73  4272.2  196.03  4741.8  189.94
  5133.6  196.24  5543.9  186.84  5839.7  195.24  6154.4  195.33  6770.1  194.73
  7266.9  193.95  8095.8  194.42  8425.1  194.71  8677.9  194.78 9352.68  193.15
 9365.83  186.58 9379.78   179.6  9422.5  158.24  9577.5  158.24 9620.22   179.6
 9662.57  188.81  9712.8  188.3210172.39  190.1210262.35  210.9710432.29  183.33
10472.28  213.86 10698.4  218.73 11284.1  223.39 11493.8  235.1112241.64  240.38
#Mann= 22 ,-1 , 0
       0     .16       0   230.5     .12       0   592.1     .05       0
  4272.2     .12       0  4741.8     .07       0  5133.6     .12       0
  5543.9     .12       0  5839.7     .05       0  6154.4     .05       0
  6770.1     .05       0  7266.9     .12       0  8095.8     .16       0
  8425.1     .05       0  8677.9     .12       0 9352.68               0
 9365.83     .12       0 9379.78               0 9620.22     .05       0
  9712.8     .12       0 10698.4     .16       0 11284.1     .16       0
 11493.8     .12       0
Bank Sta=9352.68,9662.57
XS Rating Curve= 0 ,0
Exp/Cntr=0.3,0.1

Type RM Length L Ch R = 1 ,71728   ,3207.29,3207.29,3207.29
XS GIS Cut Line= 3
3736820.5660913910528325.85169973729485.4967720510524636.6156399
3728964.6631680610522531.5811361
#Sta/Elev= 30
       0  231.12   298.6  225.89   673.5  204.78    3429  192.68  3819.6  193.75
    4050  195.07  4360.4  196.41 4794.51  182.97  5243.6  195.01 5443.77  180.98
 5673.51  194.31  6567.5  190.36  6742.3  190.31  6848.2  192.07  6985.4  192.76
 7031.95  180.06 7271.68  192.85  8500.4  194.23 8713.55  180.12  8757.5  158.14
  8912.5  158.14 8955.39  179.59 8990.07  194.71  9088.8  182.21 9339.83  190.24
  9633.5  224.76  9802.1   227.7 10073.5  233.24 10192.9  235.2410379.12  238.87
#Mann= 19 ,-1 , 0
       0     .16       0   298.6     .12       0   673.5     .05       0
    3429     .07       0  3819.6     .16       0    4050     .05       0
  4360.4     .12       0  5243.6     .12       0  6567.5     .05       0
  6742.3     .07       0  6848.2     .05       0  6985.4     .12       0
 8713.55               0 8955.39     .05       0  9088.8     .12       0
  9633.5     .16       0  9802.1     .12       0 10073.5     .16       0
 10192.9     .12       0
Bank Sta=8500.4,8990.07
XS Rating Curve= 0 ,0
Exp/Cntr=0.3,0.1

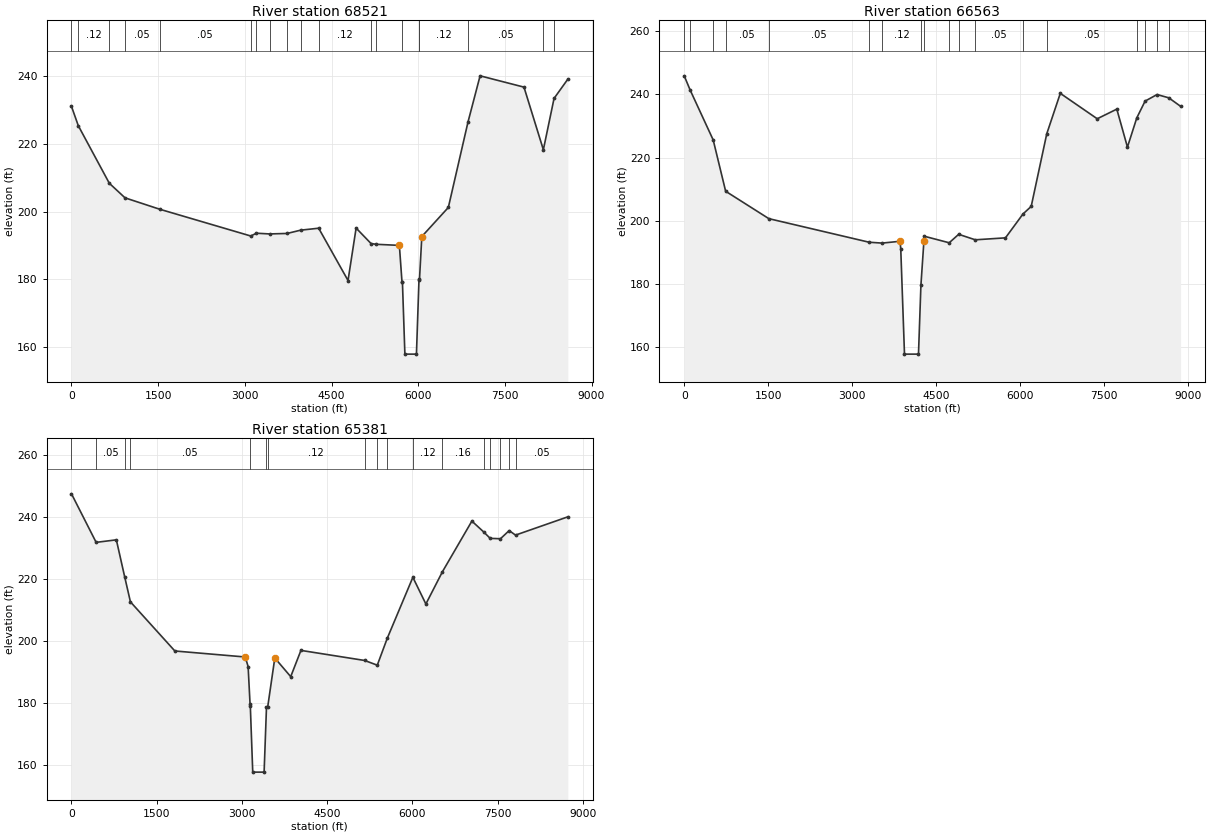
Type RM Length L Ch R = 1 ,68521   ,1958.46,1958.46,1958.46
XS GIS Cut Line= 4
3737059.2814932210527978.62962513732219.8715526310525548.0741188
3732393.4827539610524658.31704013730669.2614648810523184.1054216
#Sta/Elev= 30
       0  231.07   117.9  225.36   654.6  208.36   926.8  204.05  1524.3   200.7
  3102.4  192.78  3200.9   193.6    3428  193.39  3731.9  193.53  3965.3   194.5
  4277.9  195.08 4786.02  179.63  4925.9  195.12  5183.7  190.56  5268.4  190.33
 5674.51  190.01    5720  179.16 5727.44  179.16    5770  157.88    5970  157.88
 6014.09  179.93  6022.2   179.8 6063.02  192.62 6521.91  201.21  6862.2  226.45
 7071.55   240.1 7831.07  236.76  8166.4  218.26  8351.6  233.43 8590.59  239.13
#Mann= 20 ,-1 , 0
       0     .05       0   117.9     .12       0   654.6     .05       0
   926.8     .05       0  1524.3     .05       0  3102.4     .07       0
  3200.9     .05       0    3428     .12       0  3731.9     .16       0
  3965.3     .05       0  4277.9     .12       0  5183.7     .07       0
  5268.4     .12       0    5720     .05       0 5727.44               0
 6014.09     .05       0  6022.2     .12       0  6862.2     .05       0
  8166.4     .16       0  8351.6     .12       0
Bank Sta=5674.51,6063.02
XS Rating Curve= 0 ,0
Exp/Cntr=0.3,0.1

Type RM Length L Ch R = 1 ,66563   ,1181.63,1181.63,1181.63
XS GIS Cut Line= 4
3737549.7326120610527689.27784163734459.4549999710525849.0000262
3733938.6217240510525015.66671913730292.78813647 10522758.722086
#Sta/Elev= 30
       0  245.87   108.8  241.26   517.7  225.56   740.1  209.31    1512  200.63
  3303.7  193.16  3535.8  192.89  3854.8  193.46 3868.12  191.16    3935  157.72
    4185  157.72 4228.88  179.66 4281.63  193.43  4288.4  195.06  4733.7  192.99
    4903  195.67  5199.7  193.93 5738.85  194.55  6052.4  202.12 6198.63  204.51
  6476.8  227.53 6718.38  240.32 7378.05  232.27 7727.88  235.32 7917.79  223.29
    8085  232.56  8233.1  237.86  8446.4  239.94  8655.7  238.91 8867.33  236.21
#Mann= 19 ,-1 , 0
       0     .16       0   108.8     .16       0   517.7     .12       0
   740.1     .05       0    1512     .05       0  3303.7     .05       0
  3535.8     .12       0 3868.12               0 4228.88     .05       0
  4288.4     .12       0  4733.7     .05       0    4903      .1       0
  5199.7     .05       0  6052.4     .16       0  6476.8     .05       0
    8085     .12       0  8233.1     .07       0  8446.4     .12       0
  8655.7     .16       0
Bank Sta=3854.8,4281.63
XS Rating Curve= 0 ,0
Exp/Cntr=0.3,0.1

Type RM Length L Ch R = 1 ,65381   ,1166.86,1166.86,1166.86
XS GIS Cut Line= 2
3738154.2970197210526606.17174013730570.5661242210522272.6111816
#Sta/Elev= 30
       0  247.43   433.9  231.77  789.51  232.58   937.4  220.54    1037  212.58
 1818.87  196.72  3058.1  194.78 3108.07  191.69  3142.2  179.61 3147.15  178.81
 3189.52  157.63 3389.52  157.63 3431.45   178.6  3452.2   178.6 3577.78  194.46
 3857.61  188.44  4037.5  196.91  5158.7  193.66  5380.9  192.14  5555.9  200.79
  6007.1  220.49  6236.1  211.88  6526.6  222.27 7045.59  238.63  7256.1  235.08
  7367.5  233.06  7548.7  232.94  7701.8  235.57  7813.2  234.11 8734.52  240.01
#Mann= 18 ,-1 , 0
       0     .16       0   433.9     .05       0   937.4     .08       0
    1037     .05       0  3142.2     .12       0 3147.15               0
 3431.45     .05       0  3452.2     .12       0  5158.7     .05       0
  5380.9     .12       0  5555.9     .05       0  6007.1     .12       0
  6526.6     .16       0  7256.1     .05       0  7367.5     .12       0
  7548.7     .16       0  7701.8     .08       0  7813.2     .05       0
Bank Sta=3058.1,3577.78
XS Rating Curve= 0 ,0
Exp/Cntr=0.3,0.1