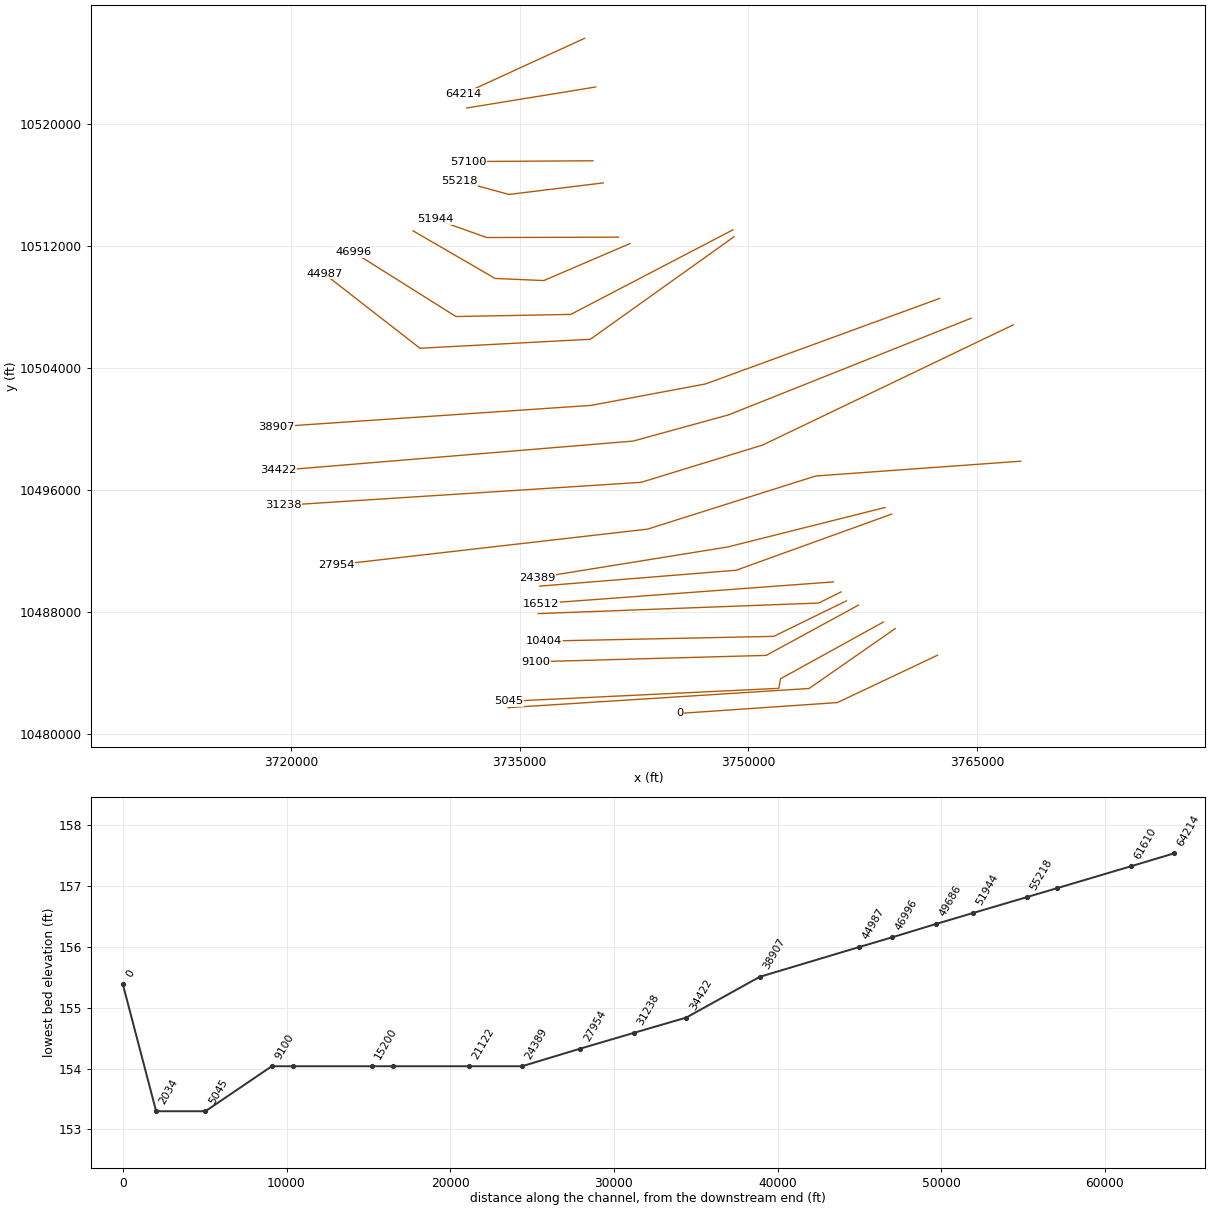
HEC-RAS study TRINITY RIVER.prj: TRINITY RIVER Base Level Engineering

--- TRINITY RIVER.g06 (geometry) --- (continued)

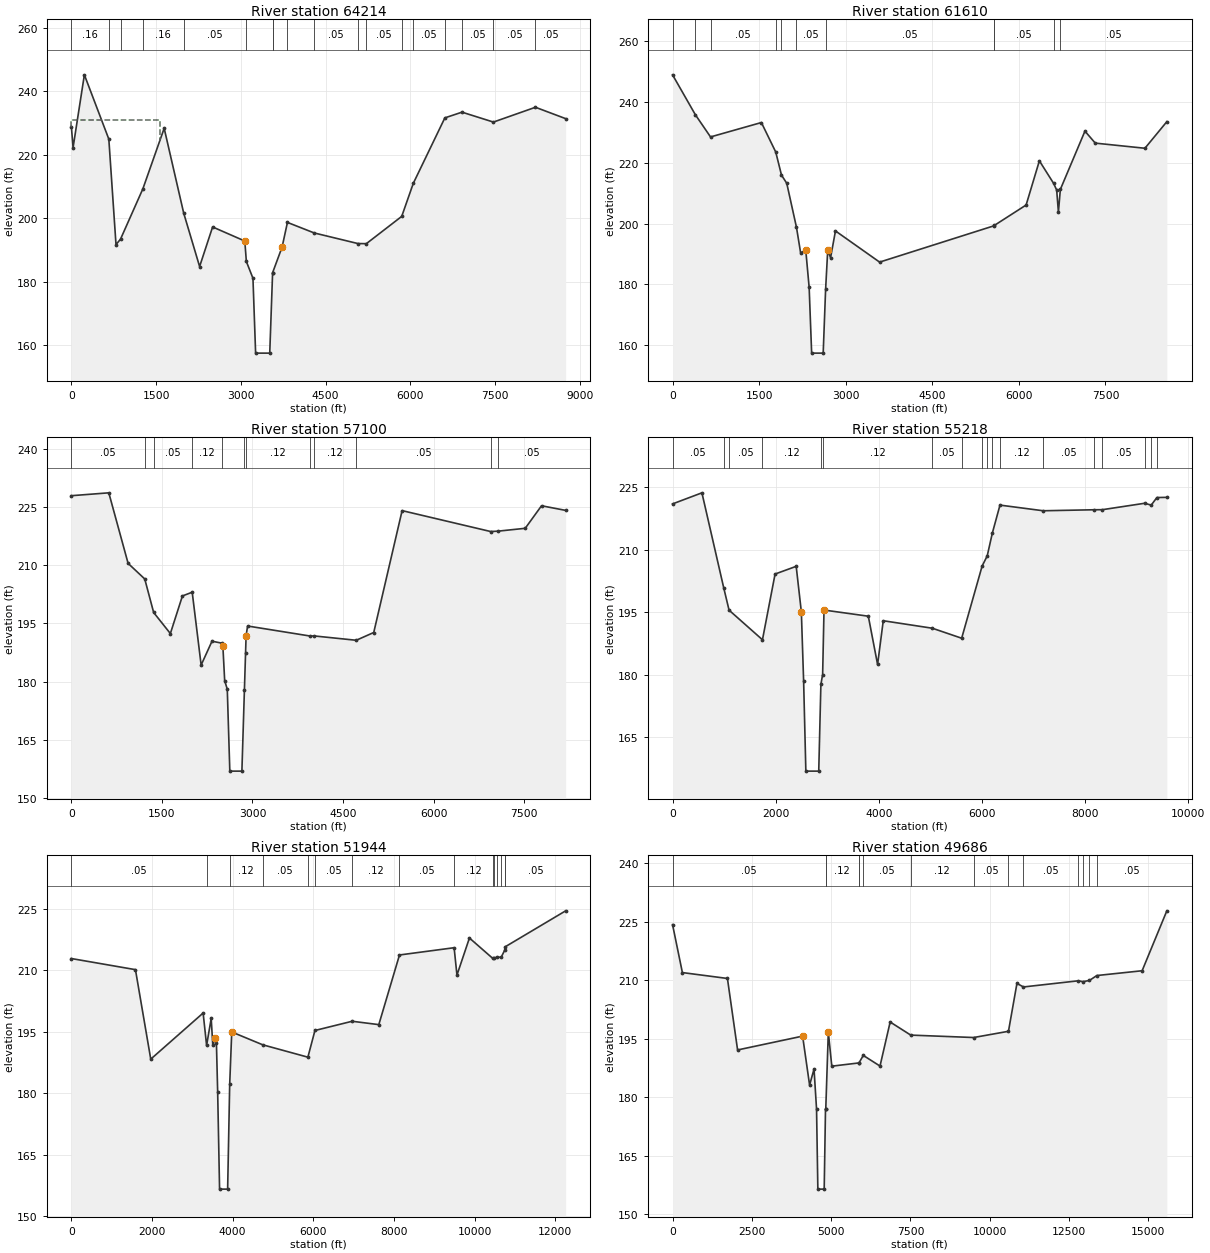
Type RM Length L Ch R = 1 ,64214   ,2604,2604,2604
XS GIS Cut Line= 2
3739251.1215977210525640.66678143731299.7326448910521994.8331938
#Sta/Elev= 30
       0  228.79   29.99  222.22  229.93  245.13   662.7  224.89  789.76  191.71
   869.5  193.41  1265.4  209.26 1642.21   228.3  1988.1  201.58 2269.32  184.79
 2499.26  197.25 3069.09  192.82  3096.6  186.38 3213.32   181.1 3260.44  157.54
 3510.44  157.54 3561.03  182.84  3561.1  182.85  3728.9  190.92  3823.6  198.68
  4297.5  195.36    5070  192.03  5220.1  191.99  5846.2  200.58  6050.9  210.98
  6609.5  231.58  6912.5  233.38  7468.7  230.26  8212.7  234.92 8747.43  231.34
#Mann= 19 ,-1 , 0
       0     .16       0   662.7     .12       0   869.5     .05       0
  1265.4     .16       0  1988.1     .05       0  3096.6     .12       0
 3213.32               0 3561.03     .05       0  3561.1     .12       0
  3823.6     .05       0  4297.5     .05       0    5070     .12       0
  5220.1     .05       0  5846.2     .12       0  6050.9     .05       0
  6609.5     .16       0  6912.5     .05       0  7468.7     .05       0
  8212.7     .05       0
#XS Ineff= 2 , 0
         1561.42  231.01
Permanent Ineff=
       F       F
Bank Sta=3069.09,3728.9
XS Rating Curve= 0 ,0
Exp/Cntr=0.3,0.1

Type RM Length L Ch R = 1 ,61610   ,4510,4510,4510
XS GIS Cut Line= 2
3739979.15721513 10522446.2581443731526.4664433910521068.2198896
#Sta/Elev= 30
       0  248.97   394.2  235.86     658  228.52 1538.97  233.26  1787.9  223.55
  1887.5  215.95 1978.68  213.26  2147.3  198.74 2218.52   190.4 2308.46  191.14
 2366.75  178.96    2410  157.33    2610  157.33 2651.92  178.29 2688.21  191.14
 2738.18  188.76 2822.58  197.57 3587.61   187.3  5571.2  199.27  5573.6  199.36
  6125.9   206.1 6355.74  220.65  6603.3   213.2 6655.54  211.02 6685.52  203.77
  6719.1  211.24 7145.21  230.43 7324.22  226.48  8184.5  224.79 8564.24  233.55
#Mann= 12 ,-1 , 0
       0     .05       0   394.2     .16       0     658     .05       0
  1787.9     .16       0  1887.5     .12       0  2147.3     .05       0
 2366.75               0 2651.92     .05       0  5571.2     .16       0
  5573.6     .05       0  6603.3     .12       0  6719.1     .05       0
Bank Sta=2308.46,2688.21
XS Rating Curve= 0 ,0
Exp/Cntr=0.3,0.1

Type RM Length L Ch R = 1 ,57100   ,1882,1882,1882
XS GIS Cut Line= 2
3739801.20579939 10517602.5079893731612.2326760610517550.3889987
#Sta/Elev= 30
       0  227.86  619.93   228.6   939.9  210.44  1215.5  206.43  1363.1   197.8
 1639.83  192.38 1839.81  202.06  2001.8  203.02 2149.77  184.27 2329.75  190.41
  2498.2  189.89 2509.73   189.2 2539.73  180.26 2582.86  178.04    2625  156.97
    2825  156.97 2866.96  177.95 2885.75  187.35 2894.74  191.84 2919.69  194.32
  3959.7  191.73  4020.3  191.77  4719.4  190.65 5009.47  192.65 5479.42  224.02
  6946.3  218.64  7066.1  218.73 7519.22  219.47  7789.2  225.27 8189.16  224.08
#Mann= 14 ,-1 , 0
       0     .05       0  1215.5     .12       0  1363.1     .05       0
  2001.8     .12       0  2498.2     .16       0 2582.86               0
 2866.96     .05       0 2885.75               0 2894.74     .12       0
  3959.7     .16       0  4020.3     .12       0  4719.4     .05       0
  6946.3     .07       0  7066.1     .05       0
Bank Sta=2509.73,2894.74
XS Rating Curve= 0 ,0
Exp/Cntr=0.3,0.1

Type RM Length L Ch R = 1 ,55218   ,3273.54,3273.54,3273.54
XS GIS Cut Line= 3
3740478.0322016310516149.0994785 3734290.277516810515391.4152983
3731057.4916595510516275.3803939
#Sta/Elev= 30
       0  221.02  569.45  223.68     993  200.82  1095.9  195.49  1743.6  188.38
 1988.07  204.17 2397.68  206.02 2497.59  195.09 2541.69  178.47    2585  156.82
    2835  156.82 2876.66  177.65  2910.5  180.03 2937.16  195.52 3796.34  194.04
 3976.17  182.44 4086.06  192.95  5038.1  191.15  5606.7  188.75  6003.2  206.08
  6102.4  208.54  6201.5  214.01  6349.6  220.73  7188.7  219.37  8170.5  219.61
  8335.9  219.63  9154.7  221.17  9282.6  220.73  9392.7  222.55 9585.43  222.59
#Mann= 19 ,-1 , 0
       0     .05       0     993     .12       0  1095.9     .05       0
  1743.6     .12       0 2541.69               0 2876.66     .05       0
  2910.5     .12       0  5038.1     .05       0  5606.7     .07       0
  6003.2     .05       0  6102.4     .12       0  6201.5     .16       0
  6349.6     .12       0  7188.7     .05       0  8170.5     .12       0
  8335.9     .05       0  9154.7     .12       0  9282.6     .05       0
  9392.7     .07       0
Bank Sta=2497.59,2937.16
XS Rating Curve= 0 ,0
Exp/Cntr=0.3,0.1

Type RM Length L Ch R = 1 ,51944   ,2257.57,2257.57,2257.57
XS GIS Cut Line= 3
3741488.2778845610512587.98356923732825.4215226310512562.7273861
3729441.0985668910513775.0222057
#Sta/Elev= 30
       0  212.81  1588.7   210.1 1968.39  188.27 3267.31  199.52  3353.4  191.61
 3467.14   198.2 3507.11  191.67 3567.06  193.51 3597.03   192.1 3627.66  180.23
    3675  156.56    3875  156.56 3926.09   182.1 3976.71   194.9  4744.6  191.77
    5865  188.75    6040  195.26  6963.2  197.51 7623.69  196.69  8136.4  213.68
  9491.7  215.45 9561.54  208.77 9871.08  217.82 10446.9  212.87 10486.8  212.98
 10553.4   213.1 10659.9  213.16 10749.5  214.92 10765.3  215.7212257.61  224.45
#Mann= 16 ,-1 , 0
       0     .05       0  3353.4     .12       0 3627.66               0
 3926.09     .12       0  4744.6     .05       0    5865     .12       0
    6040     .05       0  6963.2     .12       0  8136.4     .05       0
  9491.7     .12       0 10446.9     .05       0 10486.8     .07       0
 10553.4     .05       0 10659.9     .12       0 10749.5     .07       0
 10765.3     .05       0
Bank Sta=3567.06,3976.71
XS Rating Curve= 0 ,0
Exp/Cntr=0.3,0.1

Type RM Length L Ch R = 1 ,49686   ,2689.79,2689.79,2689.79
XS GIS Cut Line= 4
3742237.2327514710512168.44438213736577.5104751310509737.8888757
3733383.0660766410509876.77770563728001.1217880510513001.7776891
#Sta/Elev= 30
       0  224.23  309.98  211.93 1729.87  210.42 2049.85  192.08  4099.7  195.63
 4319.69  183.07 4459.68  187.19 4538.94  176.91    4580  156.38    4780  156.38
 4821.06  176.91  4829.5  176.91 4909.65  196.65 5019.64  187.92  5872.4  188.75
    5876  188.75  6011.8  190.68 6539.27  187.95 6859.02  199.25  7508.1  195.89
  9491.1  195.27 10588.5  196.8710855.45  209.15 11060.7  208.24 12788.8  209.82
   12937   209.6 13139.7  209.91 13373.5  211.1714801.21   212.415580.37  227.77
#Mann= 15 ,-1 , 0
       0     .05       0 4538.94               0 4821.06     .05       0
  4829.5     .12       0  5872.4     .05       0    5876     .12       0
  6011.8     .05       0  7508.1     .12       0  9491.1     .05       0
 10588.5     .12       0 11060.7     .05       0 12788.8     .08       0
   12937     .05       0 13139.7     .08       0 13373.5     .05       0
Bank Sta=4099.7,4909.65
XS Rating Curve= 0 ,0
Exp/Cntr=0.3,0.1

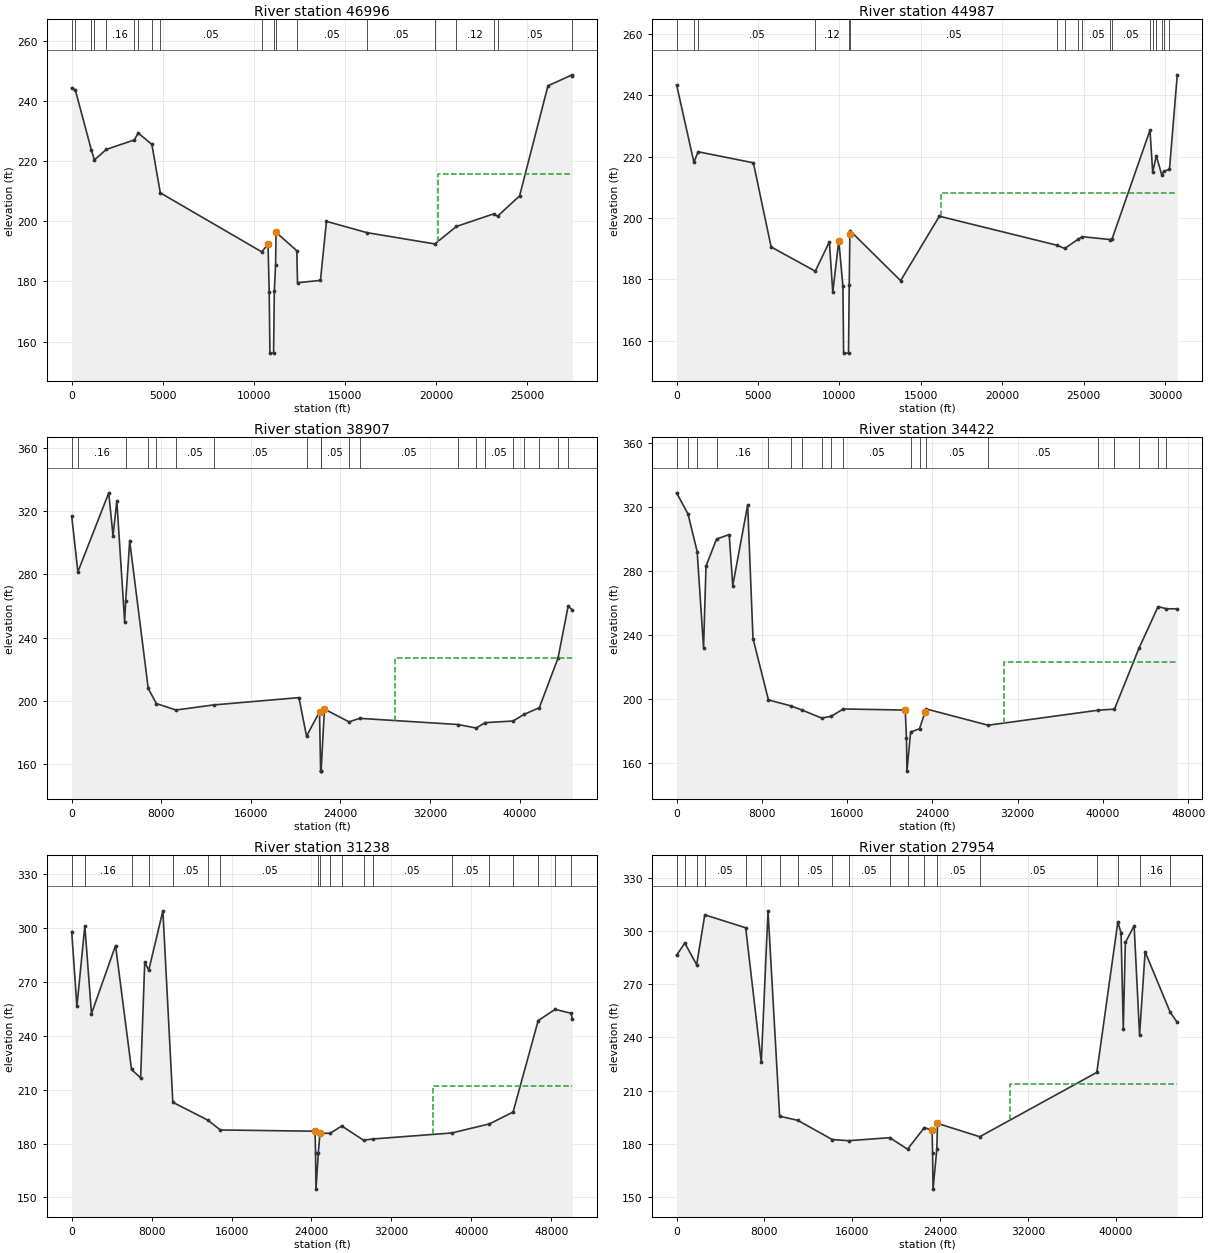
Type RM Length L Ch R = 1 ,46996   ,2009,2009,2009
XS GIS Cut Line= 4
 3748986.196943810513069.12138653738348.3438757210507515.6666141
3730813.6217404810507376.7777843 3724077.510540810511612.8887346
#Sta/Elev= 30
       0  244.44   196.3  243.81  1082.8   223.7  1247.7  220.46  1901.1  223.96
  3434.3   227.1    3653   229.4  4402.3  225.63  4865.4   209.5 10431.4  189.88
10781.17  192.3510844.98  176.67   10886  156.16   11086  156.1611127.04  176.68
 11196.6  185.6311220.82  196.37 12360.8  190.2512399.98  179.5913659.33  180.37
13989.16  200.01 16214.4  196.26   19941   192.5 21128.4  198.33 23172.6   202.5
 23382.7  201.7224594.11  208.47 26153.5  245.13 27481.6  248.7827492.97  248.28
#Mann= 21 ,-1 , 0
       0      .1       0   196.3     .05       0  1082.8     .05       0
  1247.7     .12       0  1901.1     .16       0  3434.3     .05       0
    3653     .05       0  4402.3     .12       0  4865.4     .05       0
 10431.4     .07       010844.98               0   11070               0
11127.04     .05       0 11196.6     .05       0 12360.8     .05       0
 16214.4     .05       0   19941     .05       0 21128.4     .12       0
 23172.6     .12       0 23382.7     .05       0 27481.6     .08       0
#XS Ineff= 2 , 0
                        20088.97          215.84
Permanent Ineff=
       F       F
Bank Sta=10781.17,11220.82
XS Rating Curve= 0 ,0
Exp/Cntr=0.3,0.1

Type RM Length L Ch R = 1 ,44987   ,6080,6080,6080
XS GIS Cut Line= 4
3749067.6990773810512620.73711263739633.0660438110505883.7223715
3728452.5106490610505293.44435263722167.7883103810510189.2777367
#Sta/Elev= 30
       0  243.33  1063.8  218.09  1317.2  221.55 4717.19  217.95 5806.55  190.56
  8520.3  182.67 9384.45  192.22 9594.33   175.8 9962.69  192.6410216.37  177.82
   10260     156   10560     156 10604.3  178.1510643.71  194.63 10648.5  195.88
13762.34  179.5916141.44  200.57 23361.2  191.13 23843.1  190.07 24674.7  193.11
 24929.6   193.9 26639.9  192.97 26754.1  193.21 29079.8  228.56 29246.4  214.89
 29469.1  220.21 29800.4  214.09 29935.2  215.13 30277.2  215.8630755.73  246.59
#Mann= 19 ,-1 , 0
       0     .05       0  1063.8     .12       0  1317.2     .05       0
  8520.3     .12       010216.37               0 10604.3     .05       0
 10648.5     .05       0 23361.2     .12       0 23843.1     .05       0
 24674.7     .12       0 24929.6     .05       0 26639.9     .08       0
 26754.1     .05       0 29079.8     .16       0 29246.4     .05       0
 29469.1     .12       0 29800.4     .05       0 29935.2     .12       0
 30277.2     .05       0
#XS Ineff= 2 , 0
                        16212.93          208.19
Permanent Ineff=
       F       F
Bank Sta=9962.69,10643.71
XS Rating Curve= 0 ,0
Exp/Cntr=0.3,0.1

Type RM Length L Ch R = 1 ,38907   ,4485.35,4485.35,4485.35
XS GIS Cut Line= 4
3762549.5651582210508566.0831485 3747185.149364810502949.6944469
3739685.1492729610501543.4443066 3719008.065955310500137.1944945
#Sta/Elev= 30
       0  316.97   552.5281.6139 3309.75  331.63 3689.72   304.5  4029.7  326.48
 4729.64  249.92  4820.7263.0641  5179.6  301.12    6836207.8112  7562.6198.2531
  9310.8194.1863 12665.7197.395220293.92  202.03 20972.8  177.6622131.76  193.03
22231.64  155.51   22268  155.51   22274  155.5122571.25  194.78 24764.9186.6878
 25720.6188.9093 34515.5185.0026 36122.5182.7852 36927.3186.1946   39411187.2224
 40397.5 191.387 41763.5195.6799 43431.8227.0083 44337.4259.9035 44713.2  257.54
#Mann= 20 ,-1 , 0
       0     .16       0   552.5     .16       0  4820.7      .1       0
    6836     .16       0  7562.6     .12       0  9310.8     .05       0
 12665.7     .05       0 20972.8     .12       0   22268     .05       0
   22274     .05       0 24764.9     .05       0 25720.6     .05       0
 34515.5     .05       0 36122.5     .12       0 36927.3     .05       0
   39411     .12       0 40397.5     .12       0 41763.5     .16       0
 43431.8     .16       0 44337.4     .05       0
#XS Ineff= 2 , 0
                        28914.59          227.35
Permanent Ineff=
       F       F
Bank Sta=22131.76,22571.25
XS Rating Curve= 0 ,0
Exp/Cntr=0.3,0.1

Type RM Length L Ch R = 1 ,34422   ,3183.98,3183.98,3183.98
XS GIS Cut Line= 4
3764611.1971898110507263.99979463748695.5659633910500918.4445724
3742448.2014896410499200.50312643719164.3159708810497272.6109848
#Sta/Elev= 30
       0  328.66  1069.5  315.47  1928.3     292 2529.12   231.9 2759.04  282.86
  3746.1  299.78 4933.89  302.59 5268.16   270.7 6667.67  321.07  7167.5  237.67
  8616.9  199.31 10710.9  195.62 11754.1  193.02 13614.6  187.97 14519.9  189.14
 15639.9  193.6621452.98  192.9821569.08   175.3   21610  154.8421958.87  179.27
   22790  181.3223322.62  191.98 23373.2  193.75 29235.2  183.51 39530.2  192.87
 41084.7  193.58 43377.9   231.5 45175.9  257.63 45948.8  256.2646974.77  256.21
#Mann= 20 ,-1 , 0
       0     .05       0  1069.5     .16       0  1928.3     .16       0
  3746.1     .16       0  8616.9     .05       0 10710.9     .12       0
 11754.1     .05       0 13614.6     .12       0 14519.9     .05       0
 15639.9     .05       021569.08               021958.87     .05       0
   22790     .12       0 23373.2     .05       0 29235.2     .05       0
 39530.2     .12       0 41084.7     .05       0 43377.9     .05       0
 45175.9     .05       0 45948.8     .05       0
#XS Ineff= 2 , 0
                        30693.95          223.09
Permanent Ineff=
       F       F
Bank Sta=21452.98,23322.62
XS Rating Curve= 0 ,0
Exp/Cntr=0.3,0.1

Type RM Length L Ch R = 1 ,31238   ,3284,3284,3284
XS GIS Cut Line= 4
3767378.1240706310506829.97211943750935.1494107210498939.2779271
3742966.39927213 10496491.3612353719476.8160020610494980.9443083
#Sta/Elev= 30
       0  298.15  519.95  256.39  1314.9  301.23 1979.81  252.37 4389.57  290.33
  5986.3   221.3 6899.34  216.56  7309.3  280.96  7715.1  276.62 9127.48  309.68
 10123.9  202.97 13622.6  193.06   14876  187.5624355.96  186.8724409.22  174.98
   24450  154.5924690.78  174.98 24844.3  185.5524865.77  185.65   25886  185.75
 27031.1  189.79 29210.5  181.86 30121.1  182.53 38041.2  185.88 41817.6  190.94
 44181.4  197.56 46695.5  248.52 48388.2  254.77 49981.5  252.5950114.83  249.23
#Mann= 20 ,-1 , 0
       0     .16       0  1314.9     .16       0  5986.3     .05       0
  7715.1     .16       0 10123.9     .05       0 13622.6     .12       0
   14876     .05       024409.22               024690.78     .05       0
 24844.3     .12       0   25886     .12       0 27031.1     .05       0
 29210.5     .12       0 30121.1     .05       0 38041.2     .05       0
 41817.6     .12       0 44181.4     .05       0 46695.5     .05       0
 48388.2     .05       0 49981.5     .05       0
#XS Ineff= 2 , 0
                           36121          212.32
Permanent Ineff=
       F       F
Bank Sta=24355.96,24865.77
XS Rating Curve= 0 ,0
Exp/Cntr=0.3,0.1

Type RM Length L Ch R = 1 ,27954   ,3564.83,3564.83,3564.83
XS GIS Cut Line= 4
 3767866.405246310497878.14914383754424.7326546310496908.0277245
3743383.0660897210493418.44448063722966.3992459610491074.6945749
#Sta/Elev= 30
       0  286.41   747.8  293.27  1827.4  281.01  2565.4  309.21  6293.2   301.9
  7714.3  225.95 8327.94  311.47  9383.7  195.49 11037.8  193.18 14170.6  182.34
 15671.2  181.68 19417.7  183.38 21038.3  176.89 22570.8  189.0823276.63  187.46
23319.72  174.47   23360  154.3323705.05  176.8523766.63  191.44 27616.7  183.92
 38279.3  220.23   40197  305.26 40490.6  298.8340690.52     24540881.84  293.61
41680.14  303.03 42174.7  241.3242679.75  288.34 44963.1  254.23 45608.6  248.49
#Mann= 20 ,-1 , 0
       0     .16       0   747.8     .05       0  1827.4     .05       0
  2565.4     .05       0  6293.2     .16       0  7714.3     .16       0
  9383.7     .12       0 11037.8     .05       0 14170.6     .05       0
 15671.2     .05       0 19417.7     .12       0 21038.3     .12       0
 22570.8     .12       023319.72               023705.05     .05       0
 27616.7     .05       0 38279.3     .16       0   40197     .16       0
 42174.7     .16       0 44963.1     .16       0
#XS Ineff= 2 , 0
                        30367.73          213.58
Permanent Ineff=
       F       F
Bank Sta=23276.63,23766.63
XS Rating Curve= 0 ,0
Exp/Cntr=0.3,0.1

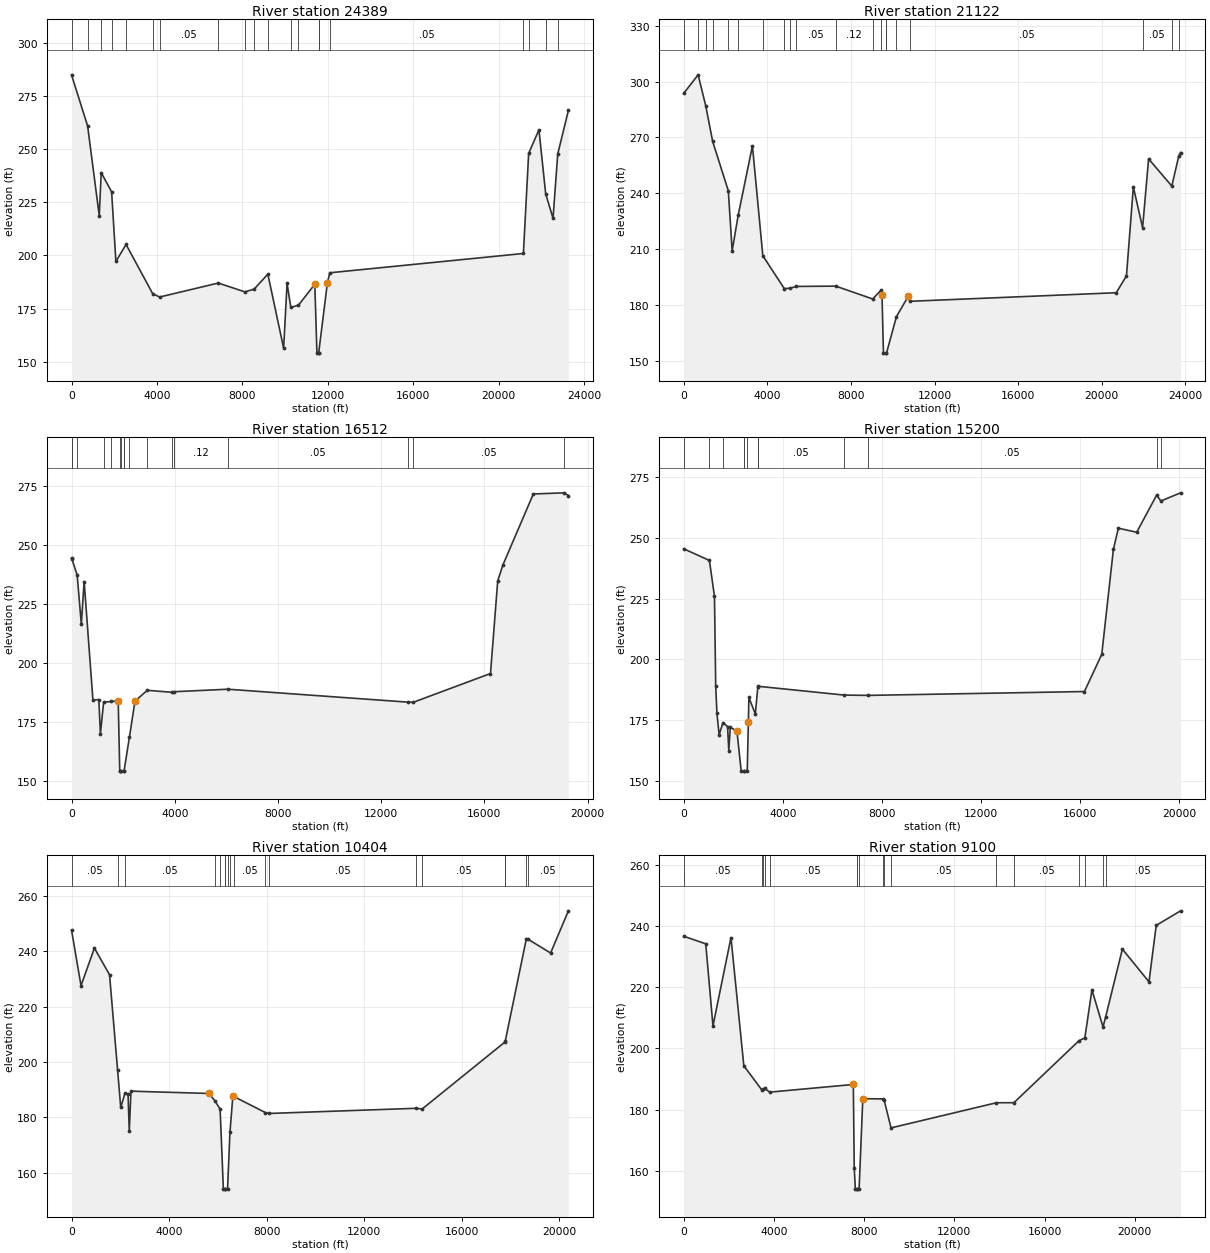
Type RM Length L Ch R = 1 ,24389   ,3267.16,3267.16,3267.16
XS GIS Cut Line= 3
3758968.8360992210494839.9547609 3748644.8236108  10492247.57051
3736179.5457198910490233.6814931
#Sta/Elev= 30
       0  284.97   754.8260.9008 1299.33   218.7  1391.2238.9406  1878.4229.9425
 2078.93  197.16  2554.5205.1596  3804.3181.9738  4128.6180.4367  6872.8 187.006
  8121.9 182.856  8554.8184.1632  9195.4191.1974 9934.86  156.3510094.78  186.85
 10272.3175.5253 10630.4176.610911394.33  186.4511494.31  154.04 11568.8154.0502
 11574.8 154.05111984.19  187.16 12098.4191.8465   21164200.9191 21410.2 247.996
21892.06  259.12 22208.4228.910622551.93  217.49 22771.8247.697223271.79  268.28
#Mann= 20 ,-1 , 0
       0     .16       0   754.8     .16       0  1391.2     .16       0
  1878.4     .12       0  2554.5     .05       0  3804.3     .12       0
  4128.6     .05       0  6872.8     .05       0  8121.9     .12       0
  8554.8     .05       0  9195.4     .12       0 10272.3     .05       0
 10630.4     .12       0 11568.8     .05       0 11574.8     .05       0
 12098.4     .05       0   21164     .12       0 21410.2     .05       0
 22208.4     .12       0 22771.8     .05       0
Bank Sta=11394.33,11984.19
XS Rating Curve= 0 ,0
Exp/Cntr=0.3,0.1

Type RM Length L Ch R = 1 ,21122   ,4609.76,4609.76,4609.76
XS GIS Cut Line= 3
3759402.8637744610494405.92708563749200.3792582210490719.7927256
 3736318.434877810489678.1261738
#Sta/Elev= 30
       0  293.65   691.6303.6255  1057.6286.8901  1385.6267.8579  2135.5241.3061
 2319.56  209.03  2613.5228.4782 3289.38  265.45  3786.7206.3776  4814.6188.7247
  5092.2188.9107  5389.5189.8884  7276.6190.0538  9042.8183.1454  9457.8188.0575
 9488.18  185.43 9558.17  154.04  9697.2  154.04  9703.2  154.04 10179.2173.6735
10747.93  184.66 10836.2   181.920693.34   186.521183.13  195.5421512.98  243.38
 21955.1221.446822242.67  258.45 23352.5243.8365 23687.9260.0687   23772  261.85
#Mann= 20 ,-1 , 0
       0     .05       0   691.6     .16       0  1057.6     .05       0
  1385.6     .16       0  2135.5     .12       0  2613.5     .16       0
  3786.7     .05       0  4814.6     .05       0  5092.2     .16       0
  5389.5     .05       0  7276.6     .12       0  9042.8     .12       0
  9457.8     .12       0  9697.2     .05       0  9703.2     .05       0
 10179.2     .12       0 10836.2     .05       0 21955.1     .05       0
 23352.5     .16       0 23687.9     .05       0
Bank Sta=9488.18,10747.93
XS Rating Curve= 0 ,0
Exp/Cntr=0.3,0.1

Type RM Length L Ch R = 1 ,16512   ,1312.22,1312.22,1312.22
XS GIS Cut Line= 2
3755589.2680552210489955.90383353736382.3520728110488532.6127168
#Sta/Elev= 30
       0  244.59     9.6244.3428   219.3 237.395  379.99   216.5  489.99   234.6
  829.98  184.28 1059.98  184.43 1119.98  169.87  1244.5183.3414  1535.5183.6288
 1809.96  183.92 1869.96  154.04  1891.9  154.04  1899.7  154.04  2029.7  154.04
  2035.7  154.04  2246.8168.6338 2459.94  183.78    2938188.3832  3876.5187.5559
  3975.4187.7847  6059.5188.8471 13035.3183.3604 13251.1183.3086 16239.8  195.52
 16519.8  234.88 16719.8  241.62 17899.8  271.81 19098.3272.3018 19259.8  271.13
#Mann= 17 ,-1 , 0
       0     .05       0     9.6     .16       0   219.3     .12       0
  1244.5     .05       0  1535.5     .12       0  1891.9     .07       0
  1899.7     .05       0  2029.7     .05       0  2035.7     .05       0
  2246.8     .12       0    2938     .05       0  3876.5     .07       0
  3975.4     .12       0  6059.5     .05       0 13035.3     .12       0
 13251.1     .05       0 19098.3     .08       0
Bank Sta=1809.96,2459.94
XS Rating Curve= 0 ,0
Exp/Cntr=0.3,0.1

Type RM Length L Ch R = 1 ,15200   ,4796.25,4796.25,4796.25
XS GIS Cut Line= 3
3756075.3792877210489296.1817277 3754617.0459183 10488567.014879
3736214.2680913810487872.5704017
#Sta/Elev= 30
       0  245.44  1038.4240.6408 1242.73  225.87 1292.44  189.01 1342.15  177.74
 1431.63  169.01  1587.1 173.991 1770.44  172.34 1820.42   162.5 1880.41   172.1
 2150.35  170.41 2320.31  154.04  2436.4  154.04  2442.4  154.04  2564.8154.2286
 2610.24  174.24 2630.24  184.32 2890.18  177.58  2991.5188.5226    2998188.9234
  6463.1185.3094  7424.8185.168316167.46  186.7616867.32  202.0517337.23  245.22
17537.19   253.918277.04  252.24 19080.5267.4795 19254.1265.0852 20046.7  268.44
#Mann= 12 ,-1 , 0
       0     .05       0  1038.4     .12       0  1587.1     .05       0
  2436.4     .05       0  2442.4     .05       0  2564.8     .12       0
  2991.5     .07       0    2998     .05       0  6463.1     .12       0
  7424.8     .05       0 19080.5     .08       0 19254.1     .05       0
Bank Sta=2150.35,2610.24
XS Rating Curve= 0 ,0
Exp/Cntr=0.3,0.1

Type RM Length L Ch R = 1 ,10404   ,1304,1304,1304
XS GIS Cut Line= 3
 3756422.601362310488705.90370883751665.6568079710486379.5149889
3736596.2125374710486067.0149577
#Sta/Elev= 30
       0  247.71  389.66  227.62  939.17  241.17 1558.63  231.54  1888.1197.1953
 2018.22  183.56  2193.6188.8027 2317.96  188.27 2367.91  175.14 2437.85  189.46
 5635.17  188.62  5875.2186.0061  6091.4182.9544 6224.88  154.04    6305  154.04
    6311  154.04  6395.6  154.04  6494.4174.5512 6614.69  187.79  6674.9187.4159
  7942.8181.7387  8109.4181.3981 14102.3183.2565 14375.4183.0284 17758.8 207.166
 17781.6207.6469 18646.1244.6189   18692244.490219638.47   239.420368.15  254.65
#Mann= 18 ,-1 , 0
       0     .05       0  1888.1     .16       0  2193.6     .05       0
  5875.2     .12       0  6091.4     .05       0    6305     .05       0
    6311     .05       0  6395.6     .07       0  6494.4     .12       0
  6674.9     .05       0  7942.8     .07       0  8109.4     .05       0
 14102.3     .08       0 14375.4     .05       0 17758.8     .08       0
 17781.6     .05       0 18646.1     .08       0   18692     .05       0
Bank Sta=5635.17,6614.69
XS Rating Curve= 0 ,0
Exp/Cntr=0.3,0.1

Type RM Length L Ch R = 1 ,9100    ,4054.9,4054.9,4054.9
XS GIS Cut Line= 3
3757221.2126259710488428.12604913751170.8651466410485129.5148642
3736040.6568900510484712.8483747
#Sta/Elev= 30
       0  236.67  978.74  234.19 1298.33  207.38  2097.3  236.24 2666.56  194.34
  3461.2186.4754    3528 186.637  3594.3186.9774  3810.8185.7293 7520.96  188.24
 7560.95  160.97 7610.94  154.04  7681.3  154.04  7687.3  154.04  7777.1154.0854
 7940.84  183.59  8853.1183.5269  8889.1183.0591  9192.3174.0475 13863.8 182.264
 14639.3182.2847 17524.8 202.539   17784  203.4618098.04  219.16 18590.3207.0105
 18701.9210.185919447.78  232.4720627.54  221.7620947.48  240.2222027.27  244.97
#Mann= 17 ,-1 , 0
       0     .05       0  3461.2     .16       0    3528     .05       0
  3594.3     .16       0  3810.8     .05       0  7681.3     .05       0
  7687.3     .05       0  7777.1     .12       0  8853.1     .05       0
  8889.1     .12       0  9192.3     .05       0 13863.8     .12       0
 14639.3     .05       0 17524.8     .16       0   17784     .05       0
 18590.3     .08       0 18701.9     .05       0
Bank Sta=7520.96,7940.84
XS Rating Curve= 0 ,0
Exp/Cntr=0.3,0.1

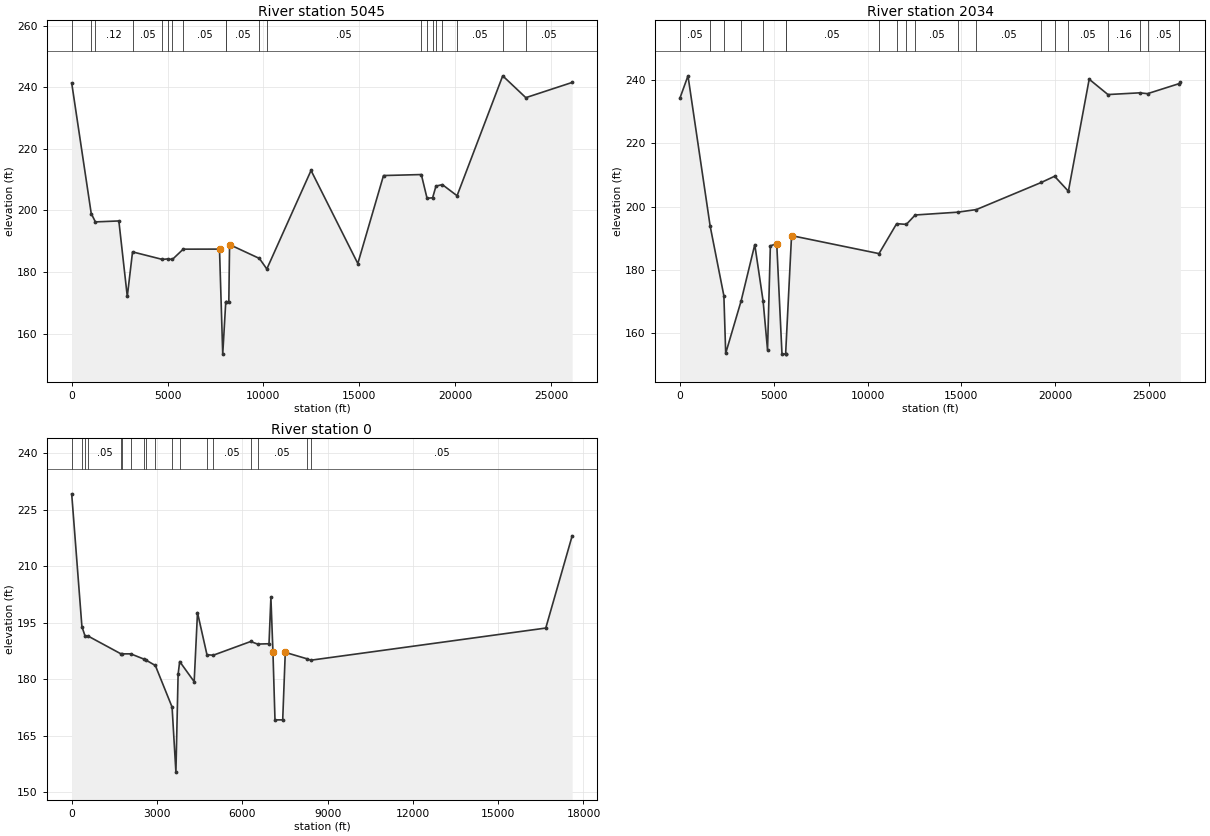
Type RM Length L Ch R = 1 ,5045    ,3011,3011,3011
XS GIS Cut Line= 4
3758853.1568686410487317.01508243752105.4197079710483591.2899223
3751995.28508572  10482966.289863734260.1866977210482114.8719434
#Sta/Elev= 30
       0   241.4  1018.6198.9879  1235.9196.2598 2459.36  196.57 2899.24  172.04
  3173.5186.5211  4728.3184.0677  5027.5 184.255    5248  184.05    5817187.4046
 7708.01  187.42 7876.59   153.3  8033.2170.1126  8039.2170.1101  8193.9  170.29
 8233.56  188.89  9787.7184.3902 10175.5180.960412481.56  212.9714920.92  182.74
16260.57  211.32 18232.7211.6425 18531.4203.9361 18821.9 204.091 18996.5207.8923
 19330.1208.3688 20096.5204.7573 22476.9243.7168 23682.2236.624126098.64  241.57
#Mann= 20 ,-1 , 0
       0     .05       0  1018.6     .05       0  1235.9     .12       0
  3173.5     .05       0  4728.3     .12       0  5027.5     .16       0
    5248     .12       0    5817     .05       0  8033.2     .05       0
  8039.2     .05       0  9787.7     .12       0 10175.5     .05       0
 18232.7     .05       0 18531.4     .05       0 18821.9     .08       0
 18996.5     .05       0 19330.1     .12       0 20096.5     .05       0
 22476.9     .16       0 23682.2     .05       0
Bank Sta=7708.01,8233.56
XS Rating Curve= 0 ,0
Exp/Cntr=0.3,0.1

Type RM Length L Ch R = 1 ,2034    ,2034.13,2034.13,2034.13
XS GIS Cut Line= 3
3759629.1113534710486886.04120683753984.2076170610482956.9936187
3734235.9436359710481698.3130652
#Sta/Elev= 30
       0  234.27  429.85  241.34  1610.7193.8132  2342.8171.7371 2439.17  153.56
  3263.6170.1882 3988.64  187.94  4434.1170.0082 4668.41  154.63 4818.36  187.55
 5158.25  188.25 5438.95   153.3  5625.9   153.3  5631.9   153.3 5947.98  190.79
 10607.4185.1003 11547.5194.5645 12065.3194.3475 12535.5197.3164 14808.1198.2082
 15796.2199.0318 19251.4207.6008 19963.6209.5659 20698.4 204.83121806.52  240.27
   22806235.4167 24490.7235.9585 24916.8235.6982 26611.7238.898426666.31  239.27
#Mann= 20 ,-1 , 0
       0     .05       0  1610.7     .05       0  2342.8     .12       0
  3263.6     .05       0  4434.1     .12       0  5625.9     .05       0
  5631.9     .05       0 10607.4     .05       0 11547.5     .07       0
 12065.3     .07       0 12535.5     .05       0 14808.1     .05       0
 15796.2     .05       0 19251.4     .05       0 19963.6     .12       0
 20698.4     .05       0   22806     .16       0 24490.7     .16       0
 24916.8     .05       0 26611.7     .12       0
Bank Sta=5158.25,5947.98
XS Rating Curve= 0 ,0
Exp/Cntr=0.3,0.1

Type RM Length L Ch R = 1 ,0       ,0,0,0
BEGIN DESCRIPTION:
TRINITY RIVER 269.0
END DESCRIPTION:
XS GIS Cut Line= 3
      3762408.67     10485138.57      3755839.09     10482031.22
      3745529.04     10481322.25
#Sta/Elev= 30
       0  229.22   359.5193.9954   467.9191.5481   575.3191.4916  1746.8186.7102
  1763.7186.7652  2078.9186.7645    2535185.3914  2602.1185.1518  2941.5183.6827
  3530.6  172.65  3665.4  155.39  3742.8  181.32    3798  184.73  4307.7  179.38
  4424.6  197.71  4757.6186.5366  4978.6186.4022  6296.6190.0459  6537.7189.3599
  6939.8  189.45  7006.2  201.72  7078.4   187.2    7150  169.25  7421.6  169.25
  7511.8  187.16  8264.8185.4776  8409.4185.0794 16673.4  193.61 17601.8  218.07
#Mann= 18 ,-1 , 0
       0     .05       0   359.5     .16       0   467.9     .12       0
   575.3     .05       0  1746.8     .16       0  1763.7      .1       0
  2078.9     .05       0    2535      .1       0  2602.1     .05       0
  2941.5     .12       0  3530.6    .033       0    3798     .12       0
  4757.6      .1       0  4978.6     .05       0  6296.6     .12       0
  6537.7     .05       0  8264.8     .07       0  8409.4     .05       0
Bank Sta=7078.4,7511.8
XS Rating Curve= 0 ,0
Exp/Cntr=0.3,0.1
Stream Node=LTT_River       ,1               , 0 , 0 ,Upstream end
Stream Node=LTT_River       ,1               , 0 , 1 ,Downstream end

Chan Stop Cuts=-1
CM Template=300',False, 0 , 1
 CM Simple Trapezoid=40,300,2,
CM Template=200',False, 0 , 1
 CM Simple Trapezoid=40,200,2,
CM Template=250',False, 0 , 1
 CM Simple Trapezoid=40,250,2,
CM Template=155',False, 0 , 1
 CM Simple Trapezoid=40,155,2,
CM Template=100,False, 0 , 1
 CM Simple Trapezoid=40,100,2,
Use User Specified Reach Order=0
Composite Channel Slope=5