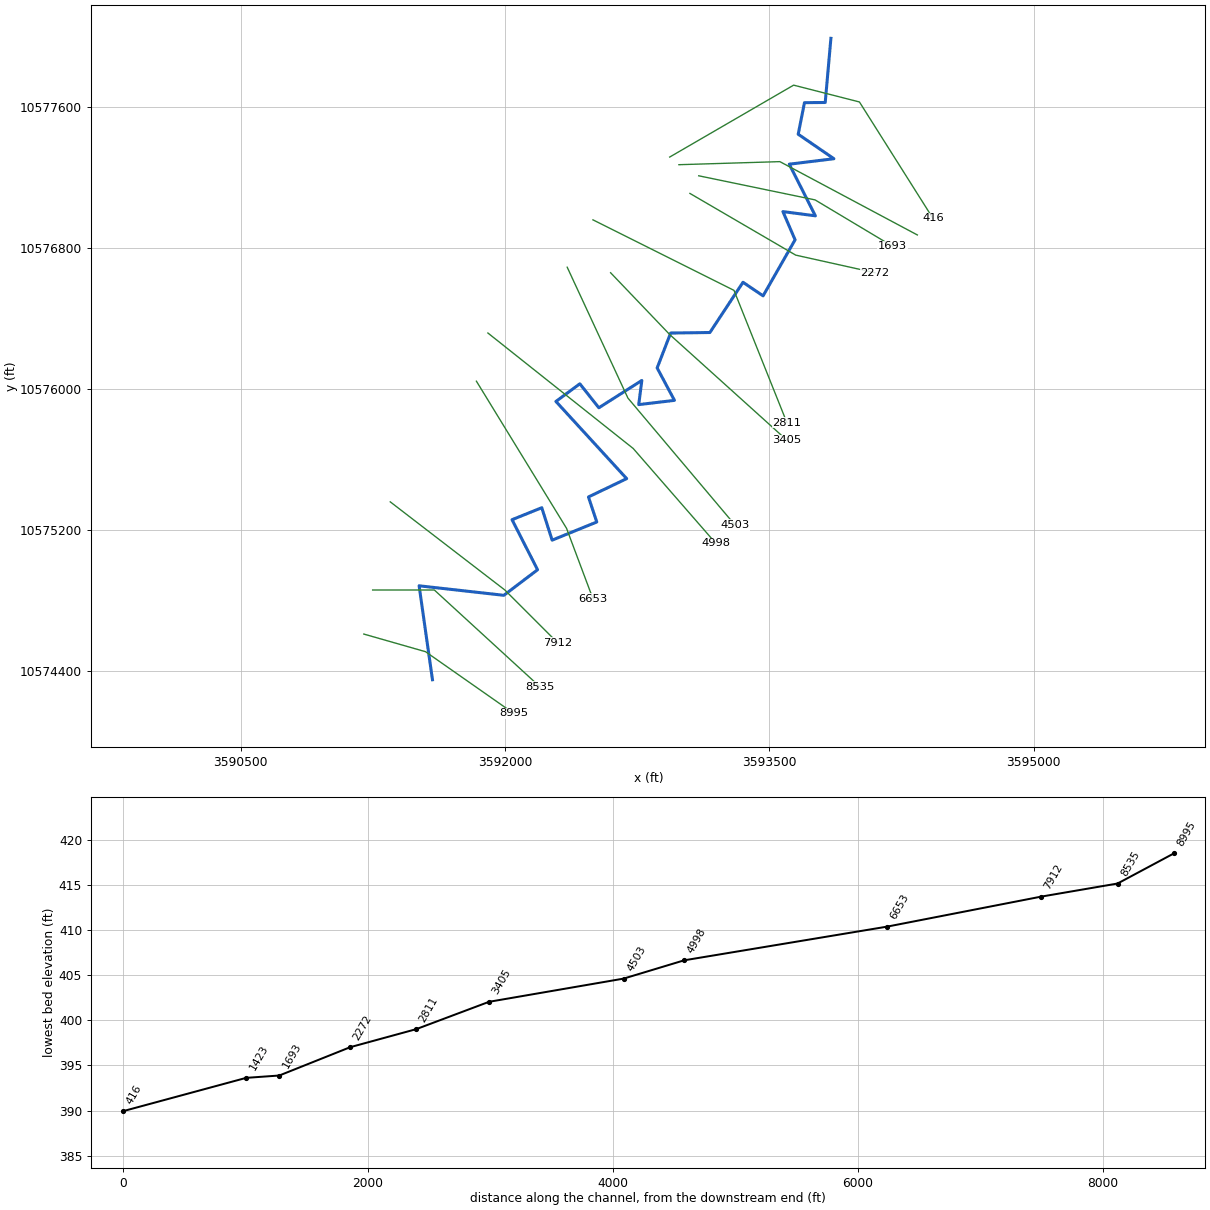
--- CHURCH CREEK.prj (project) ---

Proj Title=CHURCH CREEK Base Level Engineering
Current Plan=p01
Default Exp/Contr=0.3,0.1
English Units
Geom File=g01
Flow File=f01
Plan File=p01
BEGIN DESCRIPTION:
CHURCH CREEK
END DESCRIPTION:

--- CHURCH CREEK.p01 (plan) ---

Plan Title=Multiple Run
Short Identifier=Multiple
Geom File=g01
Flow File=f01
Subcritical Flow
K Sum by GR= 0
Std Step Tol= 0.01
Critical Tol= 0.01
Num of Std Step Trials= 20
Max Error Tol= 0.3
Flow Tol Ratio= 0.001
Split Flow NTrial= 30
Split Flow Tol= 0.02
Split Flow Ratio= 0.02
Log Output Level= 0
Friction Slope Method= 1
Unsteady Friction Slope Method= 2
Unsteady Bridges Friction Slope Method= 1
Parabolic Critical Depth
Global Vel Dist=  1 , 1 , 1
Global Log Level= 0
CheckData=True
Encroach Param= -1, 0, 0, 0
BEGIN DESCRIPTION:
Multiple Run
END DESCRIPTION:

--- CHURCH CREEK.f01 (steady flow) ---

Flow Title=Multiple
Number of Profiles=7
Profile Names=10-year,25-year,50-year,1pct_min,100-year,1pct_plu,500-year
River Rch & RM= CHURCH CREEK,Reach-1,8995
    1053    1448    1775    1588    2148    2905    3135
River Rch & RM= CHURCH CREEK,Reach-1,7912
    1423    1983    2451    2208    2986    4039    4421
Boundary for River Rch & Prof#=CHURCH CREEK,Reach-1,1
Up Type=0
Dn Type=3
Dn Slope=0.005
Boundary for River Rch & Prof#=CHURCH CREEK,Reach-1,2
Up Type=0
Dn Type=3
Dn Slope=0.005
Boundary for River Rch & Prof#=CHURCH CREEK,Reach-1,3
Up Type=0
Dn Type=3
Dn Slope=0.005
Boundary for River Rch & Prof#=CHURCH CREEK,Reach-1,4
Up Type=0
Dn Type=3
Dn Slope=0.005
Boundary for River Rch & Prof#=CHURCH CREEK,Reach-1,5
Up Type=0
Dn Type=3
Dn Slope=0.005
Boundary for River Rch & Prof#=CHURCH CREEK,Reach-1,6
Up Type=0
Dn Type=3
Dn Slope=0.005
Boundary for River Rch & Prof#=CHURCH CREEK,Reach-1,7
Up Type=0
Dn Type=3
Dn Slope=0.005

--- CHURCH CREEK.g01 (geometry) ---

Geom Title=Existing Conditions

River Reach=CHURCH CREEK,Reach-1
Reach XY= 30
      3591589.00     10574351.00      3591513.25     10574884.00
      3591994.00     10574830.00      3592185.25     10574975.00
      3592040.50     10575259.00      3592209.00     10575327.00
      3592268.00     10575143.00      3592521.25     10575246.00
      3592474.00     10575388.00      3592690.75     10575492.00
      3592289.50     10575930.00      3592425.00     10576030.00
      3592533.00     10575894.00      3592776.75     10576049.00
      3592759.25     10575912.00      3592962.00     10575936.00
      3592863.75     10576120.00      3592940.25     10576318.00
      3593163.00     10576321.00      3593350.75     10576606.00
      3593464.75     10576529.00      3593646.25     10576847.00
      3593577.25     10577007.00      3593761.50     10576983.00
      3593613.25     10577276.00      3593866.50     10577307.00
      3593664.00     10577446.00      3593699.50     10577625.00
      3593817.25     10577626.00      3593849.50     10577990.00

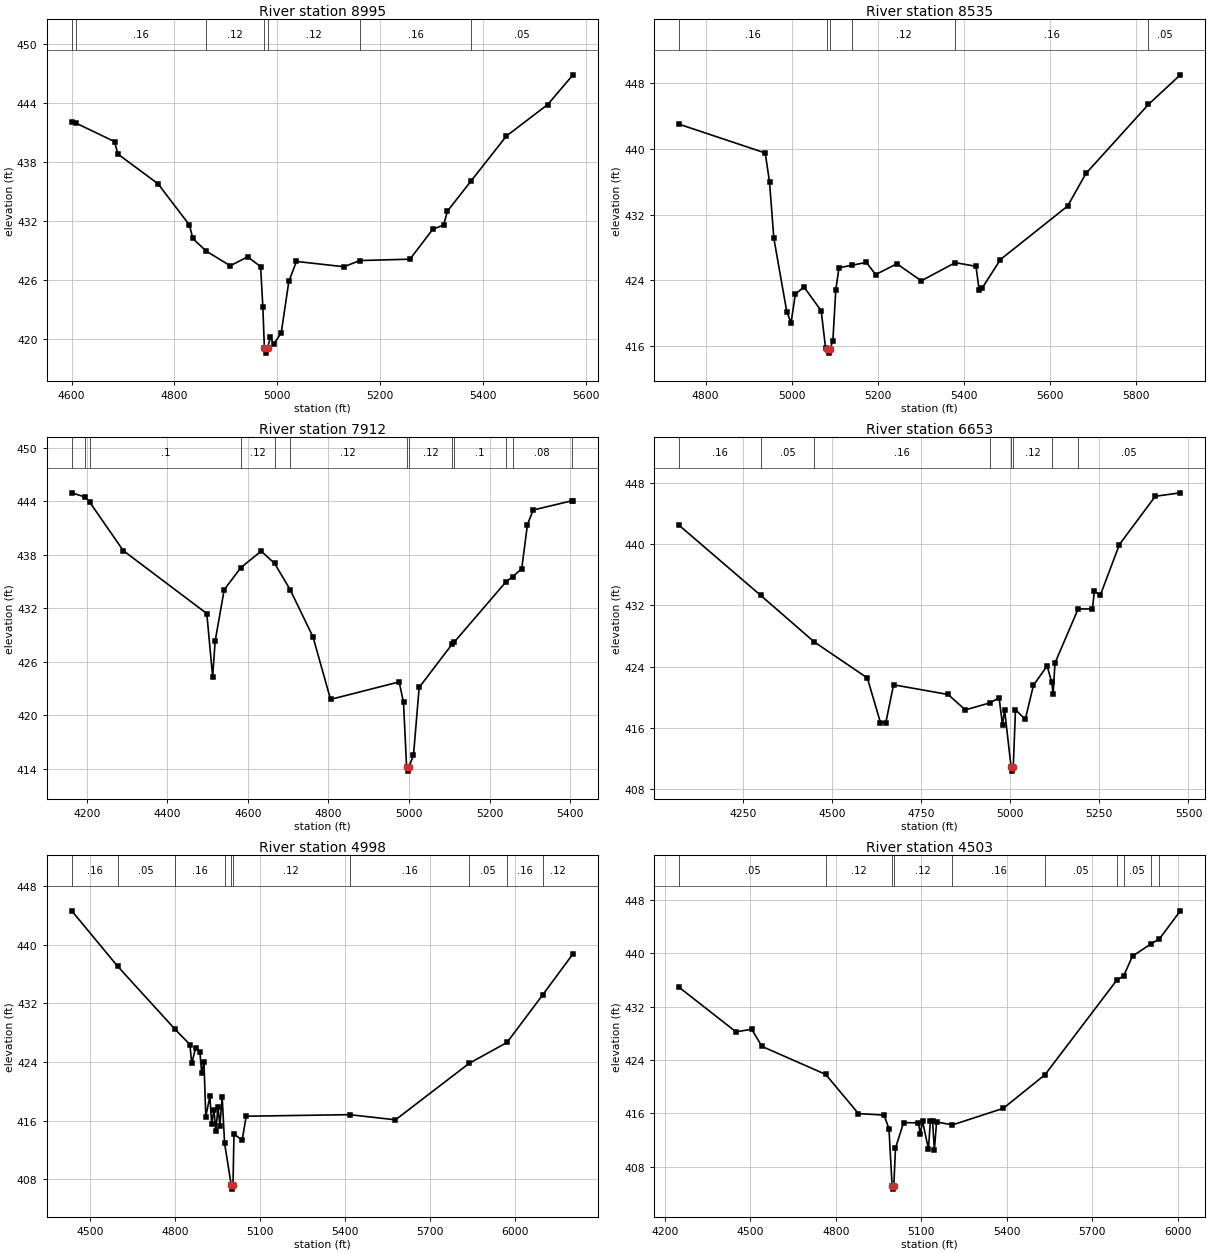
Type RM Length L Ch R = 1,8995,460,460,460
BEGIN DESCRIPTION:
CHURCH CREEK 11.0
END DESCRIPTION:
XS GIS Cut Line= 3
      3591199.61     10574610.19      3591549.61     10574510.19
      3592049.58     10574160.21
#Sta/Elev= 30
  4600.4  442.11  4608.5  441.97  4683.6  440.08  4690.1  438.81  4768.1  435.78
  4829.2  431.57  4835.7  430.20  4861.9  428.91  4908.5  427.42  4942.3  428.33
  4967.5  427.34  4971.8  423.26  4974.9  419.01  4977.7  418.51  4980.9  419.01
  4986.6  420.16  4992.7  419.41  5007.6  420.58  5022.4  425.83  5037.2  427.86
  5129.6  427.32  5160.3  427.95  5257.8  428.09  5302.3  431.15  5323.2  431.57
  5330.6  432.99  5376.6  436.07  5445.3  440.65  5525.5  443.86  5574.7  446.89
#Mann=7,-1,0
  4600.4    0.05       0  4608.5    0.16       0  4861.9    0.12       0
  4974.9    0.07       0  4980.9    0.12       0  5160.3    0.16       0
  5376.6    0.05       0
Bank Sta=4974.9,4980.9
Exp/Cntr=0.3,0.1

Type RM Length L Ch R = 1,8535,623,623,623
BEGIN DESCRIPTION:
CHURCH CREEK 10.0
END DESCRIPTION:
XS GIS Cut Line= 3
      3591249.61     10574860.19      3591599.61     10574860.19
      3592199.58     10574310.21
#Sta/Elev= 30
  4738.5  443.00  4938.5  439.50  4948.5  436.00  4958.5  429.15  4988.5  420.23
  4998.5  418.85  5008.5  422.34  5028.5  423.21  5068.5  420.32  5078.5  415.85
  5083.0  415.67  5085.7  415.17  5089.0  415.67  5095.6  416.66  5102.4  422.87
  5109.8  425.55  5140.7  425.86  5173.3  426.20  5194.9  424.72  5244.2  426.03
  5300.9  423.96  5379.8  426.17  5427.9  425.72  5435.3  422.82  5442.1  423.07
  5484.7  426.55  5640.7  433.05  5683.2  437.01  5828.3  445.40  5902.4  449.00
#Mann=6,-1,0
  4738.5    0.16       0  5083.0    0.07       0  5089.0    0.16       0
  5140.7    0.12       0  5379.8    0.16       0  5828.3    0.05       0
Bank Sta=5083,5089
Exp/Cntr=0.3,0.1

Type RM Length L Ch R = 1,7912,1259,1259,1259
BEGIN DESCRIPTION:
CHURCH CREEK 9.0
END DESCRIPTION:
XS GIS Cut Line= 3
      3591349.59     10575360.21      3591999.61     10574860.19
      3592299.64     10574560.15
#Sta/Elev= 30
  4162.7  444.95  4196.6  444.47  4207.2  443.91  4290.5  438.47  4498.0  431.40
  4512.5  424.32  4518.8  428.33  4541.2  434.08  4582.6  436.56  4633.0  438.41
  4666.4  437.02  4704.7  434.10  4761.7  428.77  4805.2  421.77  4975.5  423.73
  4986.3  421.43  4993.9  414.22  4996.7  413.72  4999.9  414.22  5011.1  415.51
  5025.2  423.11  5107.3  427.99  5112.3  428.20  5240.8  434.97  5257.9  435.55
  5279.8  436.44  5293.9  441.37  5308.1  443.02  5403.5  444.05  5407.1  444.05
#Mann=13,-1,0
  4162.7     0.1       0  4196.6    0.05       0  4207.2     0.1       0
  4582.6    0.12       0  4666.4    0.16       0  4704.7    0.12       0
  4993.9    0.07       0  4999.9    0.12       0  5107.3    0.16       0
  5112.3     0.1       0  5240.8    0.05       0  5257.9    0.08       0
  5403.5     0.1       0
Bank Sta=4993.9,4999.9
Exp/Cntr=0.3,0.1

Type RM Length L Ch R = 1,6653,1655,1655,1655
BEGIN DESCRIPTION:
CHURCH CREEK 8.0
END DESCRIPTION:
XS GIS Cut Line= 3
      3591838.33     10576044.81      3592349.61     10575210.19
      3592499.62     10574810.16
#Sta/Elev= 30
  4071.3  442.46  4300.6  433.30  4450.5  427.24  4599.4  422.54  4636.1  416.73
  4651.3  416.73  4672.9  421.65  4825.7  420.39  4874.2  418.38  4943.2  419.29
  4968.9  419.96  4978.5  416.43  4984.3  418.41  5002.6  410.89  5005.4  410.39
  5008.6  410.89  5014.9  418.39  5042.4  417.14  5065.2  421.59  5103.5  424.10
  5116.7  421.98  5120.4  420.46  5125.7  424.50  5190.6  431.54  5230.7  431.55
  5236.1  433.84  5253.0  433.36  5306.4  439.95  5407.0  446.24  5477.3  446.69
#Mann=8,-1,0
  4071.3    0.16       0  4300.6    0.05       0  4450.5    0.16       0
  4943.2    0.12       0  5002.6    0.07       0  5008.6    0.12       0
  5116.7     0.1       0  5190.6    0.05       0
Bank Sta=5002.6,5008.6
Exp/Cntr=0.3,0.1

Type RM Length L Ch R = 1,4998,495,495,495
BEGIN DESCRIPTION:
CHURCH CREEK 7.0
END DESCRIPTION:
XS GIS Cut Line= 3
      3591903.43     10576318.23      3592728.11     10575662.83
      3593196.86     10575124.64
#Sta/Elev= 30
  4436.1  444.60  4598.0  437.04  4799.6  428.48  4852.6  426.37  4859.0  423.82
  4873.4  425.95  4887.8  425.39  4894.2  422.52  4902.3  423.95  4908.7  416.56
  4923.1  419.31  4929.5  415.54  4937.5  417.48  4943.9  414.61  4951.9  417.82
  4958.3  415.31  4966.4  419.22  4974.9  412.94  4998.6  407.16  5001.3  406.66
  5004.6  407.16  5008.0  414.18  5036.8  413.34  5051.2  416.60  5415.5  416.81
  5577.4  416.11  5837.2  423.81  5970.5  426.65  6096.3  433.14  6203.2  438.74
#Mann=10,-1,0
  4436.1    0.16       0  4598.0    0.05       0  4799.6    0.16       0
  4974.9    0.12       0  4998.6    0.07       0  5004.6    0.12       0
  5415.5    0.16       0  5837.2    0.05       0  5970.5    0.16       0
  6096.3    0.12       0
Bank Sta=4998.6,5004.6
Exp/Cntr=0.3,0.1

Type RM Length L Ch R = 1,4503,1098,1098,1098
BEGIN DESCRIPTION:
CHURCH CREEK 6.0
END DESCRIPTION:
XS GIS Cut Line= 3
      3592353.40     10576691.48      3592697.72     10575949.29
      3593304.99     10575229.25
#Sta/Elev= 30
  4249.4  434.89  4449.3  428.21  4504.4  428.60  4540.2  426.03  4764.2  421.83
  4879.2  415.95  4969.0  415.73  4986.4  413.70  4997.4  405.13  5000.2  404.63
  5003.4  405.13  5009.3  410.77  5037.7  414.60  5089.9  414.57  5096.4  412.88
  5104.2  414.82  5125.0  410.65  5131.8  414.84  5139.3  414.88  5145.9  410.52
  5153.6  414.70  5209.3  414.26  5387.7  416.74  5534.2  421.78  5786.6  435.97
  5809.9  436.56  5841.5  439.55  5906.8  441.41  5936.2  442.15  6009.5  446.35
#Mann=10,-1,0
  4249.4    0.05       0  4764.2    0.12       0  4997.4    0.07       0
  5003.4    0.12       0  5209.3    0.16       0  5534.2    0.05       0
  5786.6    0.16       0  5809.9    0.05       0  5906.8    0.16       0
  5936.2    0.05       0
Bank Sta=4997.4,5003.4
Exp/Cntr=0.3,0.1

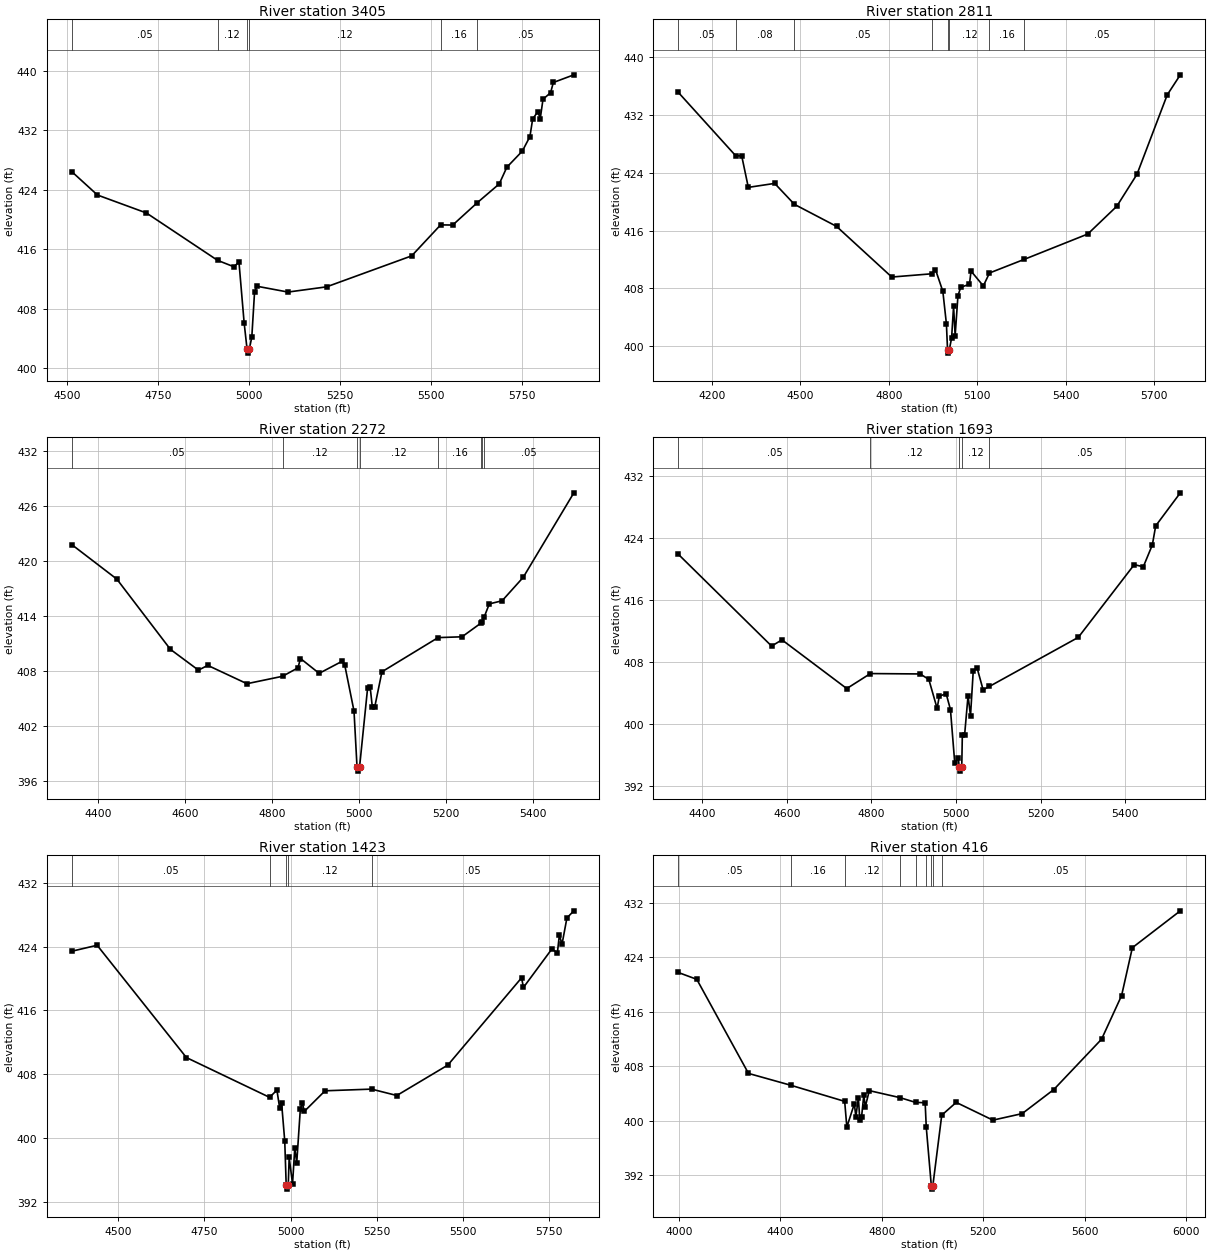
Type RM Length L Ch R = 1,3405,594,594,594
BEGIN DESCRIPTION:
CHURCH CREEK 5.0
END DESCRIPTION:
XS GIS Cut Line= 3
      3592599.64     10576660.16      3592934.99     10576309.54
      3593599.59     10575710.21
#Sta/Elev= 30
  4512.9  426.43  4583.5  423.29  4718.1  420.88  4913.6  414.52  4958.4  413.66
  4972.5  414.28  4986.7  406.13  4994.8  402.56  4997.6  402.06  5000.8  402.56
  5007.8  404.23  5015.3  410.23  5022.0  411.04  5107.2  410.26  5213.3  410.96
  5447.2  415.12  5526.8  419.28  5560.1  419.26  5627.8  422.27  5687.9  424.78
  5708.8  427.02  5751.4  429.19  5772.3  431.14  5779.8  433.51  5794.0  434.48
  5800.7  433.56  5808.2  436.15  5829.1  437.03  5836.6  438.40  5893.0  439.43
#Mann=6,-1,0
  4512.9    0.05       0  4913.6    0.12       0  4994.8    0.07       0
  5000.8    0.12       0  5526.8    0.16       0  5627.8    0.05       0
Bank Sta=4994.8,5000.8
Exp/Cntr=0.3,0.1

Type RM Length L Ch R = 1,2811,539,539,539
BEGIN DESCRIPTION:
CHURCH CREEK 4.0
END DESCRIPTION:
XS GIS Cut Line= 3
      3592499.62     10576960.18      3593299.61     10576560.19
      3593599.61     10575810.18
#Sta/Elev= 30
  4085.8  435.16  4280.6  426.37  4301.0  426.35  4323.4  421.99  4412.8  422.54
  4479.7  419.64  4622.4  416.59  4809.7  409.57  4945.5  410.02  4957.9  410.61
  4982.9  407.59  4995.0  403.08  4998.8  399.53  5001.5  399.03  5004.8  399.53
  5012.5  401.08  5019.3  405.55  5024.6  401.45  5034.1  406.97  5043.5  408.15
  5073.1  408.57  5078.5  410.39  5120.2  408.34  5141.0  410.13  5259.0  412.02
  5474.3  415.53  5572.6  419.37  5641.2  423.81  5743.6  434.80  5788.0  437.58
#Mann=8,-1,0
  4085.8    0.05       0  4280.6    0.08       0  4479.7    0.05       0
  4945.5    0.12       0  4998.8    0.07       0  5004.8    0.12       0
  5141.0    0.16       0  5259.0    0.05       0
Bank Sta=4998.8,5004.8
Exp/Cntr=0.3,0.1

Type RM Length L Ch R = 1,2272,579,579,579
BEGIN DESCRIPTION:
CHURCH CREEK 3.0
END DESCRIPTION:
XS GIS Cut Line= 3
      3593049.58     10577110.21      3593649.61     10576760.19
      3594099.58     10576660.20
#Sta/Elev= 30
  4339.3  421.75  4443.1  417.98  4566.3  410.32  4630.8  408.05  4652.3  408.57
  4742.5  406.57  4824.4  407.38  4859.9  408.30  4865.7  409.32  4908.7  407.70
  4961.6  409.02  4967.4  408.65  4988.9  403.59  4995.8  397.53  4998.6  397.03
  5001.8  397.53  5020.3  406.14  5026.1  406.20  5031.1  404.01  5036.5  404.01
  5053.2  407.87  5182.4  411.60  5237.6  411.69  5281.3  413.19  5284.1  413.35
  5288.3  413.82  5300.3  415.28  5329.8  415.62  5378.4  418.18  5494.9  427.40
#Mann=8,-1,0
  4339.3    0.05       0  4824.4    0.12       0  4995.8    0.07       0
  5001.8    0.12       0  5182.4    0.16       0  5281.3    0.12       0
  5284.1    0.16       0  5288.3    0.05       0
Bank Sta=4995.8,5001.8
Exp/Cntr=0.3,0.1

Type RM Length L Ch R = 1,1693,270,270,270
BEGIN DESCRIPTION:
CHURCH CREEK 2.0
END DESCRIPTION:
XS GIS Cut Line= 3
      3593099.62     10577210.19      3593759.65     10577073.43
      3594199.57     10576810.21
#Sta/Elev= 30
  4343.4  421.93  4564.1  410.05  4588.5  410.86  4741.7  404.56  4797.6  406.50
  4915.3  406.45  4935.7  405.74  4955.3  402.00  4960.4  403.57  4976.6  403.90
  4986.8  401.85  4997.0  394.91  5005.4  395.64  5007.5  394.39  5010.3  393.89
  5013.5  394.39  5014.9  398.59  5020.3  398.59  5028.4  403.64  5034.2  401.04
  5040.7  406.86  5049.8  407.22  5064.0  404.40  5079.0  404.84  5289.0  411.18
  5421.2  420.58  5442.6  420.30  5464.0  423.13  5471.9  425.59  5530.1  429.86
#Mann=5,-1,0
  4343.4    0.05       0  4797.6    0.12       0  5007.5    0.07       0
  5013.5    0.12       0  5079.0    0.05       0
Bank Sta=5007.5,5013.5
Exp/Cntr=0.3,0.1

Type RM Length L Ch R = 1,1423,1007,1007,1007
BEGIN DESCRIPTION:
Mapping XS e9f68e29
END DESCRIPTION:
XS GIS Cut Line= 3
      3592987.09     10577273.08      3593559.99     10577290.44
      3594339.94     10576874.47
#Sta/Elev= 30
  4365.1  423.41  4438.7  424.16  4697.8  410.10  4939.2  405.12  4960.5  406.03
  4968.4  403.79  4974.1  404.37  4983.2  399.64  4987.4  394.13  4990.1  393.63
  4993.4  394.13  4996.0  397.60  5005.8  394.29  5012.3  398.76  5018.0  396.94
  5028.5  403.71  5034.3  404.41  5040.0  403.36  5100.2  405.94  5235.1  406.15
  5308.4  405.35  5456.5  409.16  5670.4  420.08  5676.0  418.88  5758.2  423.68
  5774.5  423.23  5780.2  425.45  5787.8  424.27  5802.1  427.58  5822.2  428.47
#Mann=5,-1,0
  4365.1    0.05       0  4939.2    0.12       0  4987.4    0.07       0
  4993.4    0.12       0  5235.1    0.05       0
Bank Sta=4987.4,4993.4
Exp/Cntr=0.3,0.1

Type RM Length L Ch R = 1,416,0,0,0
BEGIN DESCRIPTION:
CHURCH CREEK 1.0
END DESCRIPTION:
XS GIS Cut Line= 4
      3592934.95     10577316.46      3593638.12     10577724.47
      3594011.38     10577628.98      3594428.03     10576969.29
#Sta/Elev= 30
  3997.7  421.78  4070.8  420.77  4274.5  406.94  4443.9  405.17  4653.6  402.83
  4662.1  399.05  4691.8  402.49  4697.6  400.55  4707.5  403.35  4713.3  400.07
  4719.9  400.46  4729.0  403.76  4734.8  402.04  4750.6  404.41  4871.4  403.38
  4933.0  402.68  4970.7  402.63  4975.1  399.02  4995.0  390.43  4997.8  389.93
  5001.0  390.43  5036.1  400.80  5093.1  402.68  5237.7  400.07  5353.0  401.03
  5477.7  404.57  5665.9  411.97  5744.8  418.38  5787.2  425.42  5976.2  430.84
#Mann=9,-1,0
  3997.7    0.05       0  4443.9    0.16       0  4653.6    0.12       0
  4871.4    0.16       0  4933.0    0.12       0  4975.1    0.16       0
  4995.0    0.07       0  5001.0    0.16       0  5036.1    0.05       0
Bank Sta=4995,5001
Exp/Cntr=0.3,0.1

Chan Stop Cuts=-1