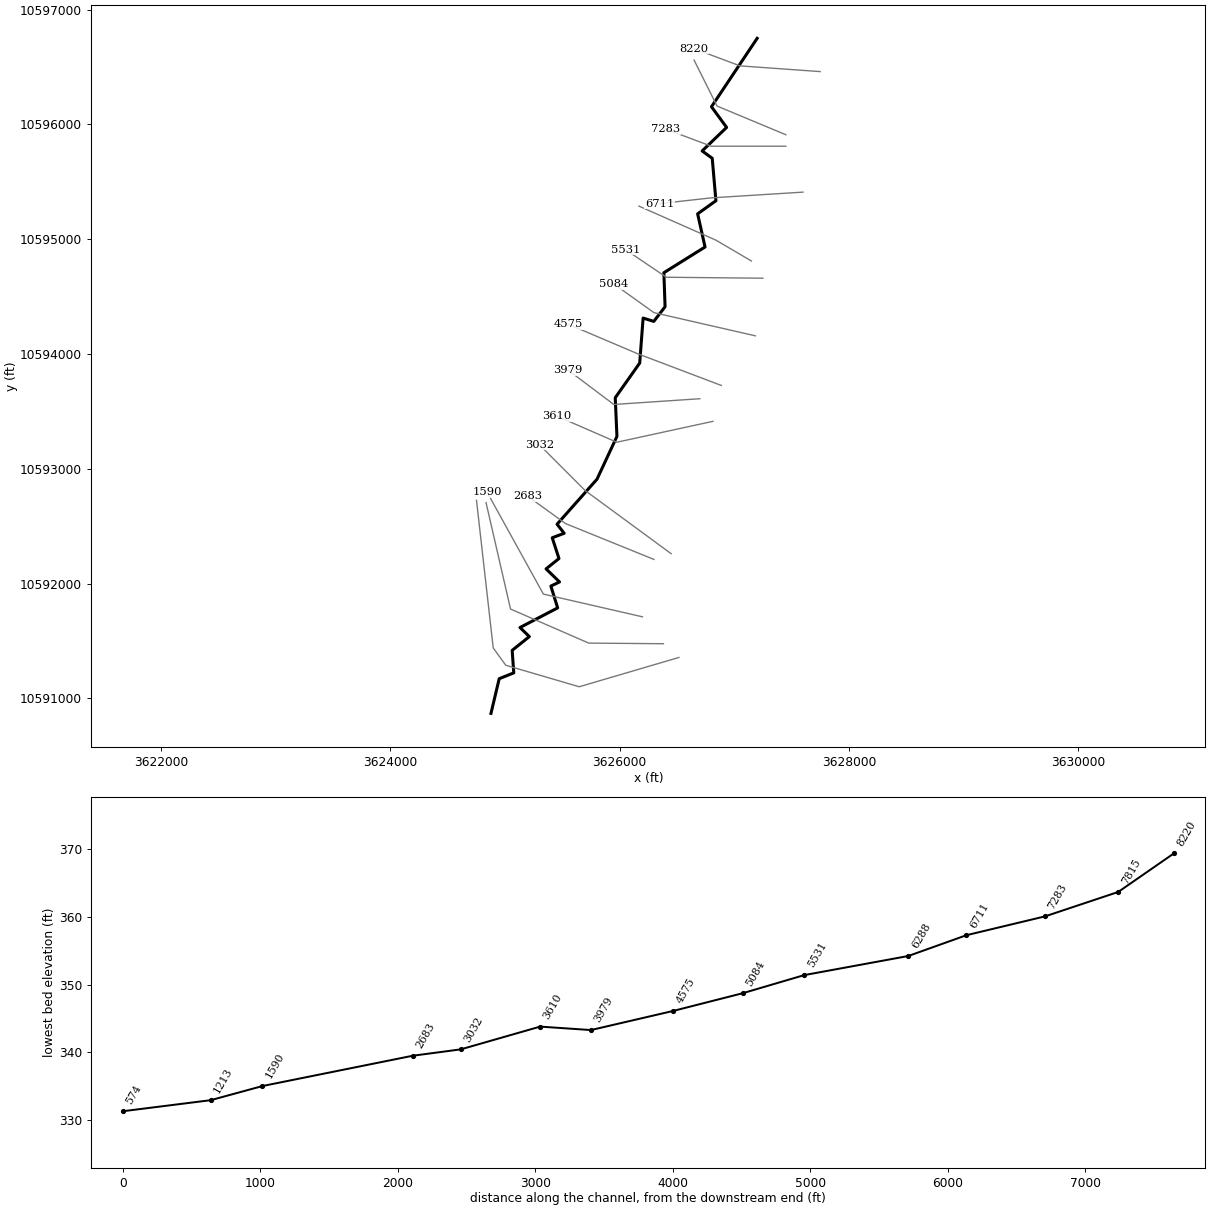
--- DOWDY BRANCH.prj (project) ---

Proj Title=DOWDY BRANCH Base Level Engineering
Current Plan=p01
Default Exp/Contr=0.3,0.1
English Units
Geom File=g01
Flow File=f01
Plan File=p01
BEGIN DESCRIPTION:
DOWDY BRANCH
END DESCRIPTION:

--- DOWDY BRANCH.p01 (plan) ---

Plan Title=Multiple Run
Short Identifier=Multiple
Geom File=g01
Flow File=f01
Subcritical Flow
K Sum by GR= 0
Std Step Tol= 0.01
Critical Tol= 0.01
Num of Std Step Trials= 20
Max Error Tol= 0.3
Flow Tol Ratio= 0.001
Split Flow NTrial= 30
Split Flow Tol= 0.02
Split Flow Ratio= 0.02
Log Output Level= 0
Friction Slope Method= 1
Unsteady Friction Slope Method= 2
Unsteady Bridges Friction Slope Method= 1
Parabolic Critical Depth
Global Vel Dist=  1 , 1 , 1
Global Log Level= 0
CheckData=True
Encroach Param= -1, 0, 0, 0
BEGIN DESCRIPTION:
Multiple Run
END DESCRIPTION:

--- DOWDY BRANCH.f01 (steady flow) ---

Flow Title=Multiple
Number of Profiles=7
Profile Names=10-year,25-year,50-year,1pct_min,100-year,1pct_plu,500-year
River Rch & RM= DOWDY BRANCH,Reach-1,8220
    1873    2683    3381    3108    4203    5683    6474
Boundary for River Rch & Prof#=DOWDY BRANCH,Reach-1,1
Up Type=0
Dn Type=3
Dn Slope=0.005
Boundary for River Rch & Prof#=DOWDY BRANCH,Reach-1,2
Up Type=0
Dn Type=3
Dn Slope=0.005
Boundary for River Rch & Prof#=DOWDY BRANCH,Reach-1,3
Up Type=0
Dn Type=3
Dn Slope=0.005
Boundary for River Rch & Prof#=DOWDY BRANCH,Reach-1,4
Up Type=0
Dn Type=3
Dn Slope=0.005
Boundary for River Rch & Prof#=DOWDY BRANCH,Reach-1,5
Up Type=0
Dn Type=3
Dn Slope=0.005
Boundary for River Rch & Prof#=DOWDY BRANCH,Reach-1,6
Up Type=0
Dn Type=3
Dn Slope=0.005
Boundary for River Rch & Prof#=DOWDY BRANCH,Reach-1,7
Up Type=0
Dn Type=3
Dn Slope=0.005

--- DOWDY BRANCH.g01 (geometry) ---

Geom Title=Existing Conditions

River Reach=DOWDY BRANCH,Reach-1
Reach XY= 30
      3627199.50     10596750.00      3626801.25     10596154.00
      3626933.25     10595974.00      3626720.00     10595769.00
      3626807.75     10595705.00      3626840.00     10595335.00
      3626680.50     10595221.00      3626745.00     10594932.00
      3626386.00     10594708.00      3626396.50     10594412.00
      3626298.25     10594284.00      3626205.00     10594313.00
      3626175.25     10593921.00      3625962.00     10593619.00
      3625976.75     10593282.00      3625802.75     10592909.00
      3625454.50     10592517.00      3625516.50     10592438.00
      3625412.50     10592399.00      3625471.25     10592218.00
      3625358.75     10592128.00      3625476.00     10592014.00
      3625400.50     10591978.00      3625459.75     10591788.00
      3625131.25     10591617.00      3625212.75     10591538.00
      3625063.00     10591418.00      3625077.00     10591222.00
      3624950.00     10591171.00      3624878.25     10590869.00

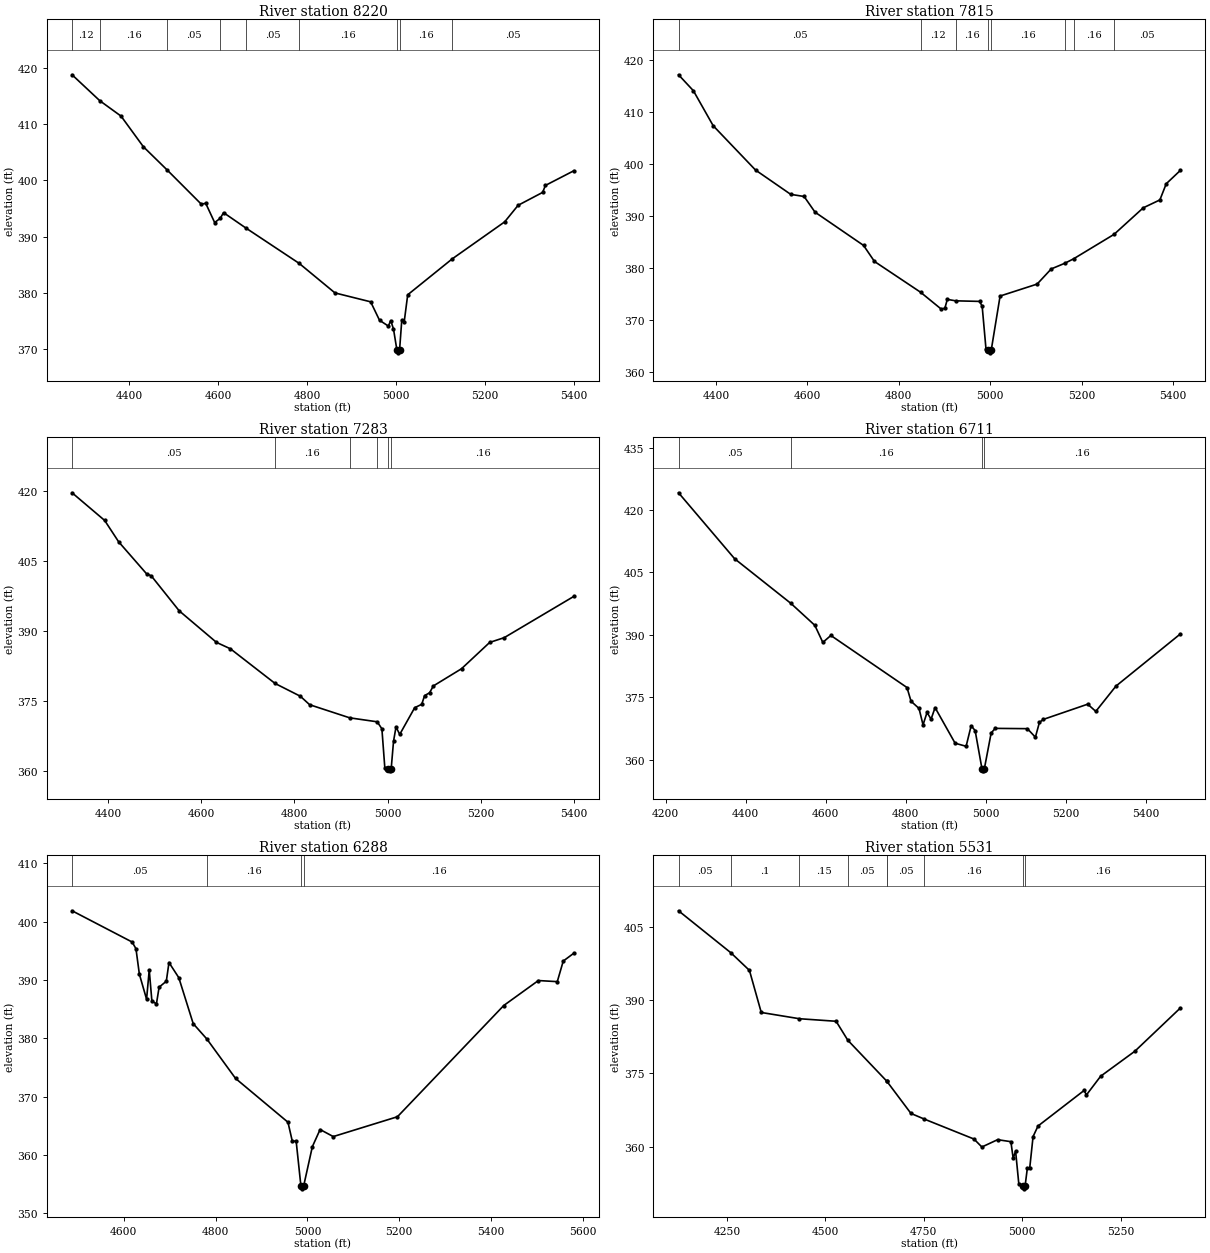
Type RM Length L Ch R = 1,8220,405,405,405
BEGIN DESCRIPTION:
DOWDY BRANCH 14.0
END DESCRIPTION:
XS GIS Cut Line= 3
      3627749.57     10596460.19      3627049.61     10596510.19
      3626649.65     10596660.17
#Sta/Elev= 30
  4270.8  418.78  4333.3  414.16  4381.0  411.43  4431.2  405.99  4484.8  401.85
  4561.5  395.78  4571.5  395.93  4591.6  392.51  4604.2  393.27  4611.6  394.27
  4661.6  391.55  4781.8  385.25  4862.3  380.00  4942.5  378.42  4962.5  375.14
  4982.3  374.11  4987.7  375.08  4993.9  373.60  5001.6  369.85  5004.3  369.35
  5007.6  369.85  5012.6  375.21  5017.9  374.79  5025.9  379.67  5126.0  386.05
  5244.0  392.63  5274.3  395.58  5329.4  397.87  5335.7  399.11  5399.7  401.72
#Mann=9,-1,0
  4270.8    0.12       0  4333.3    0.16       0  4484.8    0.05       0
  4604.2    0.16       0  4661.6    0.05       0  4781.8    0.16       0
  5001.6    0.07       0  5007.6    0.16       0  5126.0    0.05       0
Bank Sta=5001.6,5007.6
Exp/Cntr=0.3,0.1

Type RM Length L Ch R = 1,7815,532,532,532
BEGIN DESCRIPTION:
DOWDY BRANCH 13.0
END DESCRIPTION:
XS GIS Cut Line= 3
      3627449.58     10595910.20      3626849.61     10596160.19
      3626649.60     10596560.21
#Sta/Elev= 30
  4318.3  417.12  4350.8  414.05  4394.1  407.32  4486.7  398.80  4563.6  394.13
  4592.9  393.72  4616.7  390.71  4722.9  384.31  4746.7  381.23  4847.4  375.32
  4892.4  372.09  4900.6  372.21  4906.0  373.94  4924.3  373.66  4976.6  373.55
  4982.2  372.63  4990.6  364.36  4996.0  364.16  4998.8  363.66  5002.0  364.16
  5021.4  374.58  5102.4  376.88  5133.2  379.79  5163.1  380.89  5182.0  381.73
  5270.6  386.44  5334.4  391.54  5370.8  393.06  5384.7  396.17  5415.5  398.73
#Mann=8,-1,0
  4318.3    0.05       0  4847.4    0.12       0  4924.3    0.16       0
  4996.0    0.07       0  5002.0    0.16       0  5163.1    0.05       0
  5182.0    0.16       0  5270.6    0.05       0
Bank Sta=4996,5002
Exp/Cntr=0.3,0.1

Type RM Length L Ch R = 1,7283,572,572,572
BEGIN DESCRIPTION:
DOWDY BRANCH 12.0
END DESCRIPTION:
XS GIS Cut Line= 3
      3627449.62     10595810.19      3626799.61     10595810.19
      3626399.62     10595960.18
#Sta/Elev= 30
  4322.6  419.65  4392.6  413.72  4422.6  409.14  4482.6  402.28  4492.6  401.85
  4552.6  394.35  4632.6  387.59  4662.6  386.21  4758.5  378.78  4812.6  376.05
  4832.6  374.23  4918.6  371.42  4977.6  370.57  4987.7  369.07  4994.0  360.69
  5001.7  360.56  5004.4  360.06  5007.7  360.56  5012.7  366.41  5018.0  369.46
  5026.0  367.87  5058.1  373.59  5073.2  374.32  5079.4  376.18  5090.1  376.79
  5098.1  378.25  5158.6  381.94  5219.1  387.58  5250.3  388.60  5399.8  397.45
#Mann=6,-1,0
  4322.6    0.05       0  4758.5    0.16       0  4918.6    0.12       0
  4977.6    0.16       0  5001.7    0.07       0  5007.7    0.16       0
Bank Sta=5001.7,5007.7
Exp/Cntr=0.3,0.1

Type RM Length L Ch R = 1,6711,423,423,423
BEGIN DESCRIPTION:
DOWDY BRANCH 11.0
END DESCRIPTION:
XS GIS Cut Line= 3
      3627599.64     10595410.19      3626799.61     10595360.19
      3626349.57     10595310.18
#Sta/Elev= 30
  4232.4  424.14  4372.7  408.27  4513.2  397.55  4573.1  392.27  4593.1  388.16
  4613.2  389.83  4803.5  377.31  4813.6  374.02  4833.6  372.28  4843.6  368.33
  4853.6  371.31  4863.7  369.71  4873.7  372.48  4923.8  363.92  4951.3  363.18
  4963.9  368.13  4973.9  366.95  4990.9  357.78  4993.7  357.28  4996.9  357.78
  5013.9  366.38  5024.0  367.49  5104.4  367.42  5124.5  365.37  5134.6  368.94
  5144.7  369.66  5255.3  373.31  5275.5  371.57  5325.8  377.65  5486.8  390.19
#Mann=4,-1,0
  4232.4    0.05       0  4513.2    0.16       0  4990.9    0.07       0
  4996.9    0.16       0
Bank Sta=4990.9,4996.9
Exp/Cntr=0.3,0.1

Type RM Length L Ch R = 1,6288,757,757,757
BEGIN DESCRIPTION:
DOWDY BRANCH 10.0
END DESCRIPTION:
XS GIS Cut Line= 3
      3627149.64     10594810.17      3626840.38     10594991.54
      3626168.47     10595288.43
#Sta/Elev= 30
  4487.4  401.88  4618.3  396.52  4626.6  395.37  4634.0  391.01  4649.7  386.72
  4655.5  391.73  4661.3  386.39  4671.2  385.93  4677.0  388.78  4692.7  389.80
  4698.5  393.01  4719.9  390.41  4751.3  382.53  4781.1  379.89  4843.5  373.14
  4957.7  365.63  4967.0  362.43  4975.6  362.35  4985.9  354.71  4988.6  354.21
  4991.9  354.71  5010.8  361.43  5027.7  364.38  5056.4  363.17  5196.2  366.57
  5427.8  385.64  5503.2  389.92  5544.4  389.73  5557.4  393.26  5580.5  394.61
#Mann=4,-1,0
  4487.4    0.05       0  4781.1    0.16       0  4985.9    0.07       0
  4991.9    0.16       0
Bank Sta=4985.9,4991.9
Exp/Cntr=0.3,0.1

Type RM Length L Ch R = 1,5531,447,447,447
BEGIN DESCRIPTION:
DOWDY BRANCH 9.0
END DESCRIPTION:
XS GIS Cut Line= 3
      3627249.62     10594660.19      3626408.08     10594668.62
      3626049.65     10594910.16
#Sta/Elev= 30
  4127.3  408.29  4260.1  399.70  4307.3  396.09  4337.3  387.48  4434.2  386.20
  4527.3  385.68  4557.0  381.80  4655.6  373.45  4656.0  373.41  4717.3  366.82
  4751.6  365.65  4877.3  361.58  4897.3  359.95  4937.3  361.45  4971.0  361.04
  4976.8  357.63  4982.9  359.12  4991.2  352.32  5000.9  351.89  5003.6  351.39
  5006.9  351.89  5012.8  355.64  5018.9  355.73  5027.3  362.09  5039.9  364.25
  5156.8  371.52  5162.8  370.61  5198.8  374.43  5285.7  379.55  5401.1  388.39
#Mann=9,-1,0
  4127.3    0.05       0  4260.1     0.1       0  4434.2    0.15       0
  4557.0    0.05       0  4655.6     0.1       0  4656.0    0.05       0
  4751.6    0.16       0  5000.9    0.07       0  5006.9    0.16       0
Bank Sta=5000.9,5006.9
Exp/Cntr=0.3,0.1

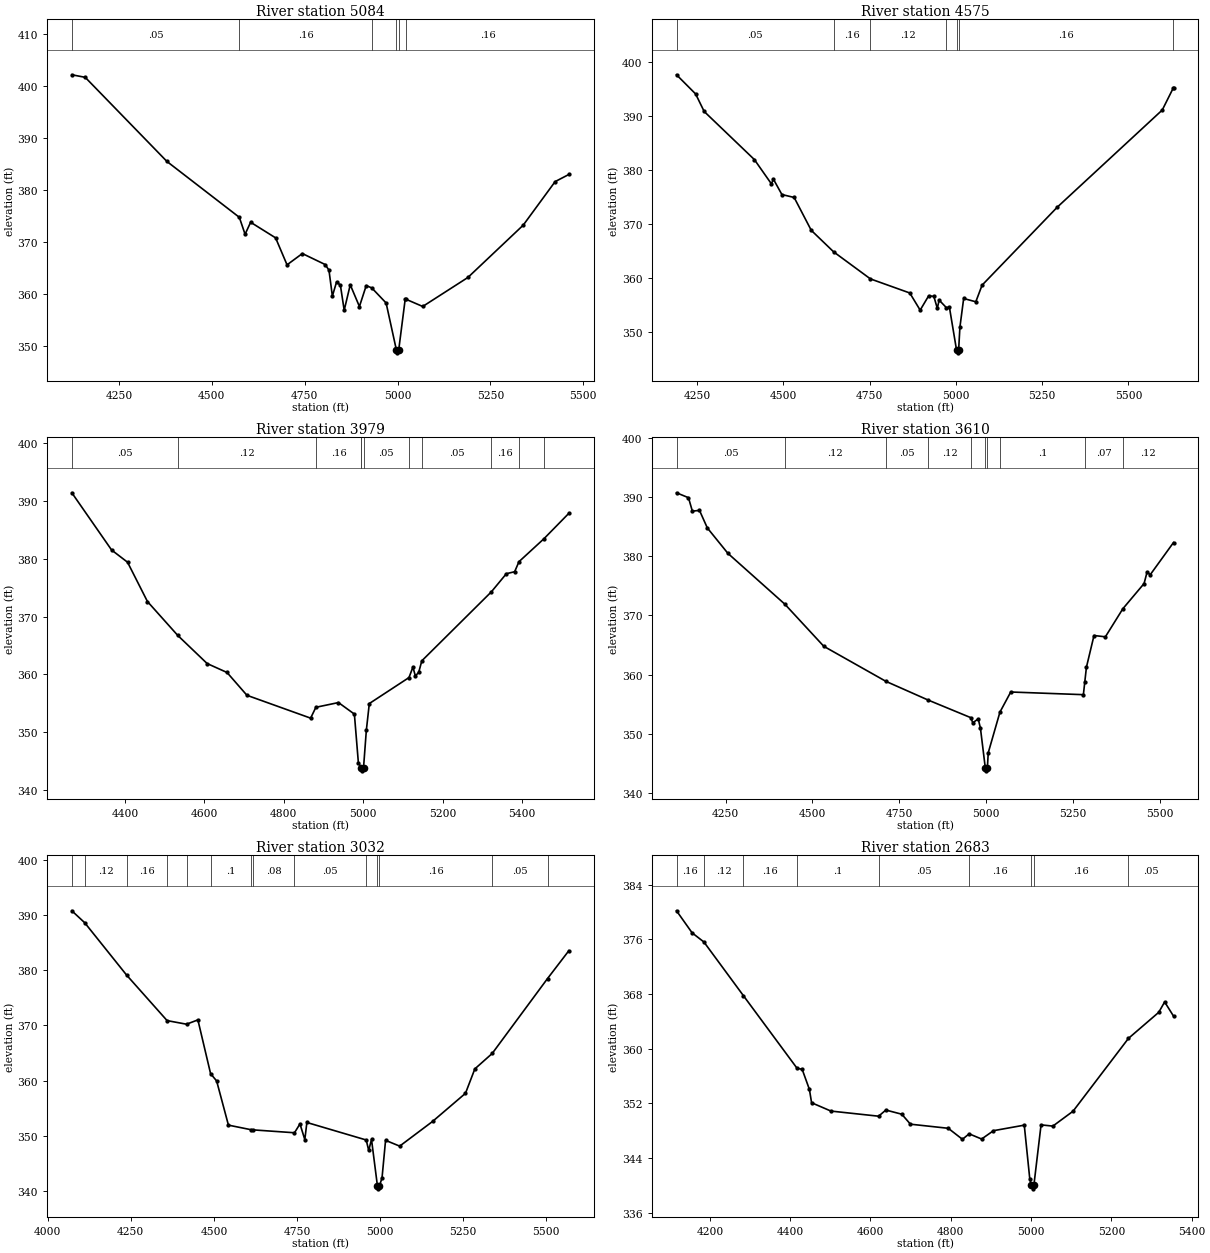
Type RM Length L Ch R = 1,5084,509,509,509
BEGIN DESCRIPTION:
DOWDY BRANCH 8.0
END DESCRIPTION:
XS GIS Cut Line= 3
      3627184.13     10594158.20      3626299.61     10594360.19
      3625949.62     10594610.18
#Sta/Elev= 30
  4123.5  402.21  4159.5  401.72  4379.5  385.53  4574.2  374.79  4589.7  371.53
  4604.6  373.84  4671.8  370.84  4702.6  365.65  4743.8  367.82  4805.1  365.71
  4815.4  364.63  4824.6  359.64  4835.9  362.36  4846.2  361.73  4856.4  356.91
  4872.7  361.81  4897.4  357.63  4915.7  361.66  4930.6  361.21  4969.2  358.31
  4997.0  349.22  4999.8  348.72  5003.0  349.22  5020.5  359.01  5023.2  359.01
  5067.7  357.64  5189.3  363.22  5338.0  373.27  5424.0  381.66  5460.9  383.03
#Mann=6,-1,0
  4123.5    0.05       0  4574.2    0.16       0  4930.6    0.12       0
  4997.0    0.07       0  5003.0    0.12       0  5023.2    0.16       0
Bank Sta=4997,5003
Exp/Cntr=0.3,0.1

Type RM Length L Ch R = 1,4575,596,596,596
BEGIN DESCRIPTION:
DOWDY BRANCH 7.0
END DESCRIPTION:
XS GIS Cut Line= 3
      3626887.27     10593725.91      3626158.08     10594001.96
      3625549.61     10594260.19
#Sta/Elev= 30
  4190.1  397.61  4245.5  394.06  4270.3  390.81  4415.8  381.90  4465.4  377.38
  4470.7  378.30  4495.6  375.42  4531.1  374.88  4580.7  368.79  4645.6  364.80
  4752.2  359.79  4866.3  357.18  4896.4  354.00  4921.2  356.67  4936.1  356.54
  4946.1  354.33  4951.4  355.86  4972.4  354.46  4981.2  354.54  5001.9  346.59
  5004.7  346.09  5007.9  346.59  5011.6  350.84  5022.5  356.16  5057.7  355.55
  5075.9  358.63  5294.0  373.09  5598.2  391.08  5630.5  395.21  5630.8  395.21
#Mann=7,-1,0
  4190.1    0.05       0  4645.6    0.16       0  4752.2    0.12       0
  4972.4    0.16       0  5001.9    0.07       0  5007.9    0.16       0
  5630.5    0.08       0
Bank Sta=5001.9,5007.9
Exp/Cntr=0.3,0.1

Type RM Length L Ch R = 1,3979,369,369,369
BEGIN DESCRIPTION:
DOWDY BRANCH 6.0
END DESCRIPTION:
XS GIS Cut Line= 3
      3626699.63     10593610.19      3625949.61     10593560.19
      3625549.60     10593860.20
#Sta/Elev= 30
  4266.4  391.46  4366.6  381.54  4406.7  379.43  4456.8  372.62  4533.2  366.74
  4607.2  361.87  4657.3  360.32  4707.4  356.37  4867.8  352.41  4881.0  354.29
  4937.9  355.11  4978.0  353.11  4988.0  344.72  4994.8  343.81  4995.0  343.78
  4997.8  343.28  5001.0  343.78  5008.1  350.30  5015.6  354.94  5115.5  359.44
  5125.4  361.25  5131.6  359.73  5140.0  360.34  5147.8  362.34  5322.9  374.29
  5360.8  377.44  5381.6  377.78  5392.5  379.52  5455.3  383.49  5518.1  387.90
#Mann=11,-1,0
  4266.4    0.05       0  4533.2    0.12       0  4881.0    0.16       0
  4994.8    0.05       0  4995.0    0.03       0  5001.0    0.05       0
  5115.5    0.08       0  5147.8    0.05       0  5322.9    0.16       0
  5392.5    0.12       0  5455.3    0.16       0
Bank Sta=4995,5001
Exp/Cntr=0.3,0.1

Type RM Length L Ch R = 1,3610,578,578,578
BEGIN DESCRIPTION:
DOWDY BRANCH 5.0
END DESCRIPTION:
XS GIS Cut Line= 3
      3626814.30     10593413.41      3625975.79     10593231.12
      3625449.59     10593460.20
#Sta/Elev= 30
  4108.3  390.70  4142.8  389.87  4154.0  387.60  4174.5  387.73  4197.1  384.77
  4256.4  380.48  4420.4  371.91  4532.7  364.80  4711.9  358.88  4833.8  355.72
  4956.3  352.76  4961.9  351.90  4977.6  352.55  4984.0  350.99  4998.0  344.29
  5000.8  343.79  5004.0  344.29  5006.5  346.84  5040.2  353.70  5071.3  357.09
  5280.6  356.64  5284.6  358.75  5289.4  361.28  5311.2  366.62  5344.0  366.40
  5394.4  371.14  5455.5  375.39  5463.9  377.27  5473.5  376.90  5540.3  382.31
#Mann=10,-1,0
  4108.3    0.05       0  4420.4    0.12       0  4711.9    0.05       0
  4833.8    0.12       0  4956.3    0.08       0  4998.0    0.07       0
  5004.0    0.08       0  5040.2     0.1       0  5284.6    0.07       0
  5394.4    0.12       0
Bank Sta=4998,5004
Exp/Cntr=0.3,0.1

Type RM Length L Ch R = 1,3032,349,349,349
BEGIN DESCRIPTION:
DOWDY BRANCH 4.0
END DESCRIPTION:
XS GIS Cut Line= 3
      3626449.64     10592260.17      3625699.61     10592810.19
      3625299.59     10593210.20
#Sta/Elev= 30
  4072.5  390.76  4111.2  388.60  4237.5  379.11  4359.2  370.88  4417.7  370.23
  4451.9  371.01  4490.1  361.28  4508.3  359.96  4543.8  351.96  4610.4  351.15
  4616.3  351.11  4742.6  350.58  4759.1  352.18  4773.7  349.34  4779.9  352.44
  4958.5  349.27  4966.0  347.37  4974.4  349.37  4992.3  340.93  4995.0  340.43
  4998.3  340.93  5006.1  342.43  5016.7  349.21  5059.2  348.16  5158.2  352.63
  5257.2  357.72  5285.4  362.14  5337.6  364.93  5504.1  378.49  5568.3  383.53
#Mann=14,-1,0
  4072.5    0.05       0  4111.2    0.12       0  4237.5    0.16       0
  4359.2    0.12       0  4417.7    0.16       0  4490.1     0.1       0
  4610.4    0.05       0  4616.3    0.08       0  4742.6    0.05       0
  4958.5    0.16       0  4992.3    0.07       0  4998.3    0.16       0
  5337.6    0.05       0  5504.1    0.16       0
Bank Sta=4992.3,4998.3
Exp/Cntr=0.3,0.1

Type RM Length L Ch R = 1,2683,1093,1093,1093
BEGIN DESCRIPTION:
DOWDY BRANCH 3.0
END DESCRIPTION:
XS GIS Cut Line= 3
      3626299.63     10592210.18      3625527.88     10592522.79
      3625199.59     10592760.20
#Sta/Elev= 30
  4116.9  380.18  4155.8  376.95  4185.2  375.61  4283.5  367.76  4417.3  357.12
  4429.8  356.99  4447.9  354.04  4453.3  352.09  4501.5  350.87  4620.2  350.12
  4638.3  351.02  4678.0  350.41  4699.5  348.95  4793.7  348.35  4829.0  346.74
  4845.7  347.54  4876.8  346.78  4906.3  348.00  4983.0  348.81  4996.8  340.90
  5000.9  339.99  5003.7  339.49  5006.9  339.99  5024.8  348.85  5054.2  348.67
  5104.5  350.85  5242.5  361.51  5317.9  365.32  5332.6  366.84  5354.7  364.77
#Mann=9,-1,0
  4116.9    0.16       0  4185.2    0.12       0  4283.5    0.16       0
  4417.3     0.1       0  4620.2    0.05       0  4845.7    0.16       0
  5000.9    0.07       0  5006.9    0.16       0  5242.5    0.05       0
Bank Sta=5000.9,5006.9
Exp/Cntr=0.3,0.1

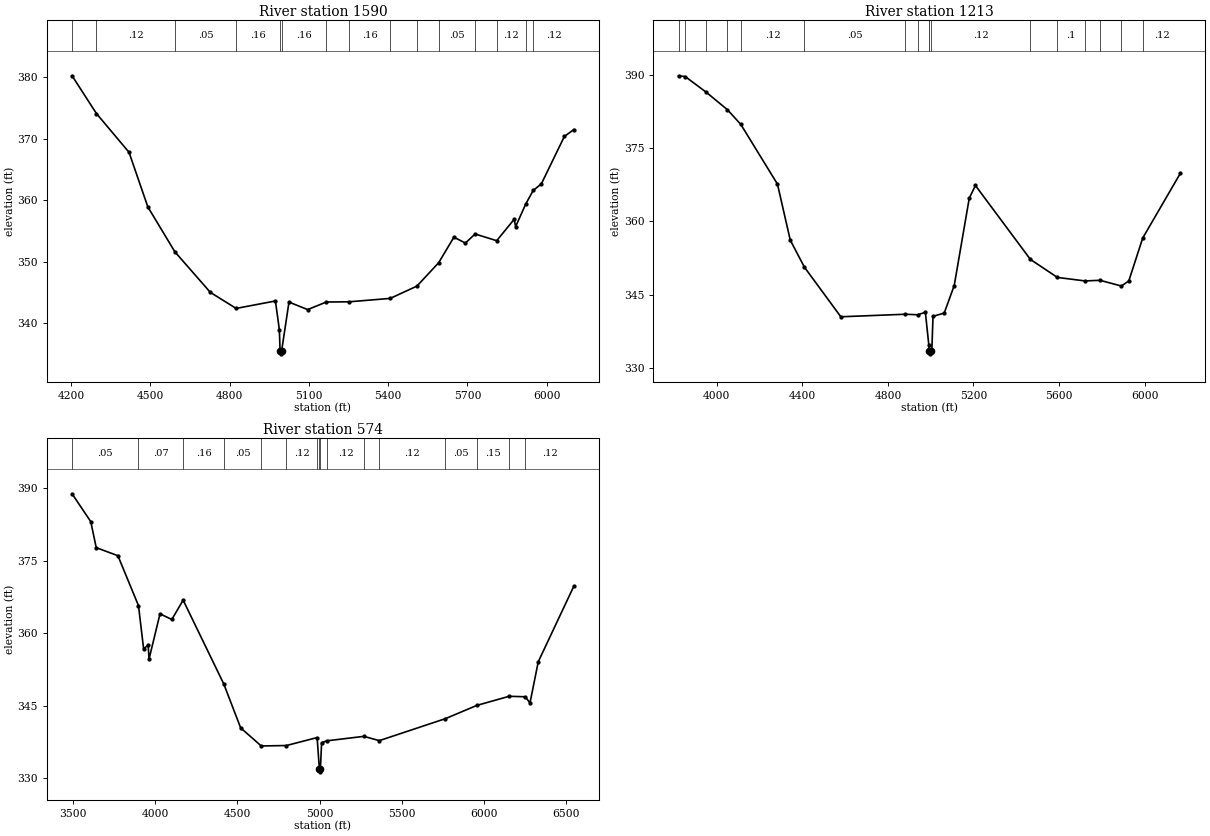
Type RM Length L Ch R = 1,1590,377,377,377
BEGIN DESCRIPTION:
DOWDY BRANCH 2.0
END DESCRIPTION:
XS GIS Cut Line= 3
      3626199.63     10591710.18      3625335.17     10591908.21
      3624845.59     10592793.61
#Sta/Elev= 30
  4204.3  380.26  4296.6  374.11  4419.8  367.81  4490.9  358.93  4593.1  351.63
  4727.5  345.02  4825.1  342.41  4973.7  343.62  4988.6  338.96  4991.3  335.52
  4994.0  335.02  4997.3  335.52  5025.0  343.44  5095.7  342.22  5166.3  343.45
  5253.3  343.49  5408.1  344.04  5509.1  346.04  5591.5  349.85  5649.0  354.00
  5692.5  353.04  5729.1  354.52  5810.9  353.43  5876.9  356.90  5882.6  355.72
  5920.6  359.38  5949.0  361.60  5980.0  362.68  6067.0  370.39  6102.9  371.51
#Mann=15,-1,0
  4204.3    0.16       0  4296.6    0.12       0  4593.1    0.05       0
  4825.1    0.16       0  4991.3    0.07       0  4997.3    0.16       0
  5166.3    0.05       0  5253.3    0.16       0  5408.1    0.05       0
  5509.1    0.08       0  5591.5    0.05       0  5729.1    0.07       0
  5810.9    0.12       0  5920.6    0.08       0  5949.0    0.12       0
Bank Sta=4991.3,4997.3
Exp/Cntr=0.3,0.1

Type RM Length L Ch R = 1,1213,639,639,639
BEGIN DESCRIPTION:
Mapping XS 6c277741
END DESCRIPTION:
XS GIS Cut Line= 4
      3626382.07     10591475.91      3625731.00     10591481.12
      3625048.71     10591778.00      3624835.17     10592705.05
#Sta/Elev= 30
  3820.9  389.80  3852.0  389.64  3950.9  386.42  4049.8  382.85  4112.0  379.86
  4283.4  367.65  4343.4  356.18  4409.8  350.64  4579.8  340.51  4881.7  341.03
  4939.5  340.92  4975.2  341.43  4991.4  334.69  4994.0  333.43  4996.7  332.93
  5000.0  333.43  5005.5  333.78  5010.9  340.60  5063.3  341.27  5110.1  346.90
  5180.4  364.76  5209.3  367.36  5466.3  352.24  5592.5  348.56  5721.7  347.84
  5792.0  347.97  5891.8  346.80  5926.4  347.84  5991.5  356.61  6167.4  369.84
#Mann=17,-1,0
  3820.9     0.1       0  3852.0    0.05       0  3950.9    0.12       0
  4049.8    0.16       0  4112.0    0.12       0  4409.8    0.05       0
  4881.7    0.16       0  4939.5    0.05       0  4991.4    0.12       0
  4994.0    0.07       0  5000.0    0.12       0  5466.3    0.05       0
  5592.5     0.1       0  5721.7    0.15       0  5792.0     0.1       0
  5891.8    0.07       0  5991.5    0.12       0
Bank Sta=4994,5000
Exp/Cntr=0.3,0.1

Type RM Length L Ch R = 1,574,0,0,0
BEGIN DESCRIPTION:
DOWDY BRANCH 1.0
END DESCRIPTION:
XS GIS Cut Line= 5
      3626517.44     10591356.12      3625647.67     10591100.91
      3625007.04     10591288.41      3624897.67     10591439.46
      3624751.87     10592725.59
#Sta/Elev= 30
  3493.3  388.90  3607.0  383.14  3640.4  377.74  3772.4  376.07  3897.7  365.72
  3928.7  356.81  3956.6  357.52  3961.8  354.65  4028.6  364.03  4100.6  362.86
  4169.5  366.87  4416.9  349.50  4519.6  340.41  4645.0  336.66  4798.2  336.75
  4985.2  338.40  4999.0  331.80  5001.8  331.30  5005.0  331.80  5012.5  337.34
  5045.4  337.73  5270.0  338.65  5363.4  337.76  5766.4  342.32  5957.9  345.07
  6154.4  346.95  6252.7  346.85  6281.0  345.56  6331.3  354.10  6548.1  369.77
#Mann=16,-1,0
  3493.3    0.05       0  3897.7    0.07       0  4169.5    0.16       0
  4416.9    0.05       0  4645.0    0.16       0  4798.2    0.12       0
  4985.2    0.16       0  4999.0    0.07       0  5005.0    0.16       0
  5045.4    0.12       0  5270.0    0.16       0  5363.4    0.12       0
  5766.4    0.05       0  5957.9    0.15       0  6154.4     0.1       0
  6252.7    0.12       0
Bank Sta=4999,5005
Exp/Cntr=0.3,0.1

Chan Stop Cuts=-1