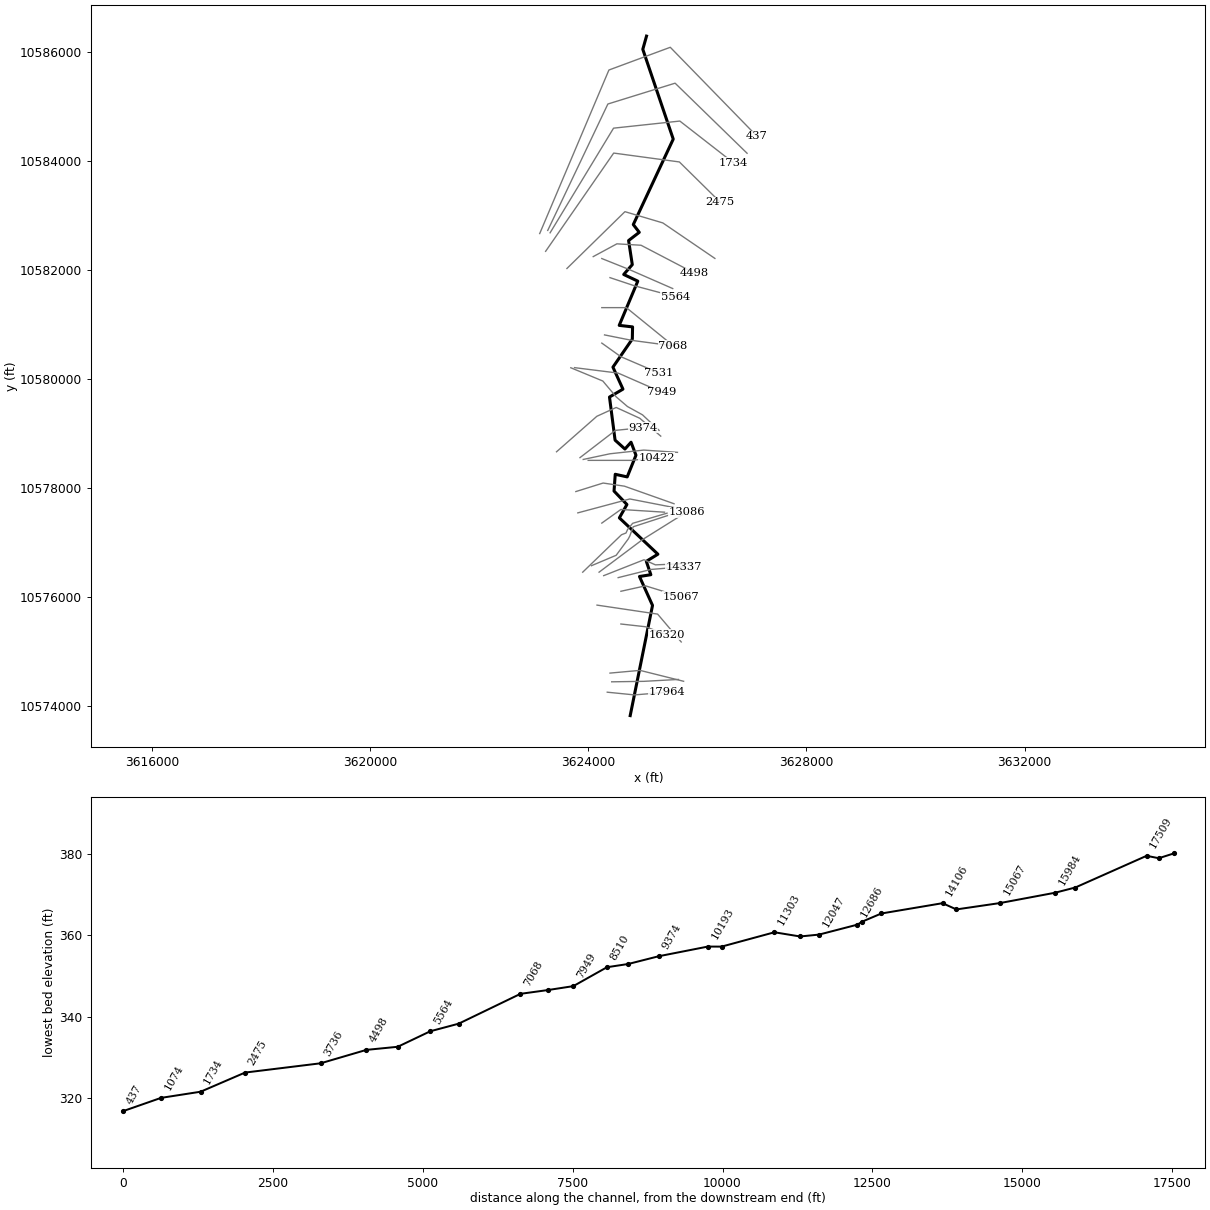
--- FOLSOM CREEK.prj (project) ---

Proj Title=FOLSOM CREEK Base Level Engineering
Current Plan=p01
Default Exp/Contr=0.3,0.1
English Units
Geom File=g01
Flow File=f01
Plan File=p01
BEGIN DESCRIPTION:
FOLSOM CREEK
END DESCRIPTION:

--- FOLSOM CREEK.p01 (plan) ---

Plan Title=Multiple Run
Short Identifier=Multiple
Geom File=g01
Flow File=f01
Subcritical Flow
K Sum by GR= 0
Std Step Tol= 0.01
Critical Tol= 0.01
Num of Std Step Trials= 20
Max Error Tol= 0.3
Flow Tol Ratio= 0.001
Split Flow NTrial= 30
Split Flow Tol= 0.02
Split Flow Ratio= 0.02
Log Output Level= 0
Friction Slope Method= 1
Unsteady Friction Slope Method= 2
Unsteady Bridges Friction Slope Method= 1
Parabolic Critical Depth
Global Vel Dist=  1 , 1 , 1
Global Log Level= 0
CheckData=True
Encroach Param= -1, 0, 0, 0
BEGIN DESCRIPTION:
Multiple Run
END DESCRIPTION:

--- FOLSOM CREEK.f01 (steady flow) ---

Flow Title=Multiple
Number of Profiles=7
Profile Names=10-year,25-year,50-year,1pct_min,100-year,1pct_plu,500-year
River Rch & RM= FOLSOM CREEK,Reach-1,17964
    1488    2124    2671    2455    3320    4491    5111
River Rch & RM= FOLSOM CREEK,Reach-1,17712
    1810    2589    3259    2993    4047    5474    6223
River Rch & RM= FOLSOM CREEK,Reach-1,8510
    2854    4160    5303    4921    6655    9000   10454
Boundary for River Rch & Prof#=FOLSOM CREEK,Reach-1,1
Up Type=0
Dn Type=3
Dn Slope=0.005
Boundary for River Rch & Prof#=FOLSOM CREEK,Reach-1,2
Up Type=0
Dn Type=3
Dn Slope=0.005
Boundary for River Rch & Prof#=FOLSOM CREEK,Reach-1,3
Up Type=0
Dn Type=3
Dn Slope=0.005
Boundary for River Rch & Prof#=FOLSOM CREEK,Reach-1,4
Up Type=0
Dn Type=3
Dn Slope=0.005
Boundary for River Rch & Prof#=FOLSOM CREEK,Reach-1,5
Up Type=0
Dn Type=3
Dn Slope=0.005
Boundary for River Rch & Prof#=FOLSOM CREEK,Reach-1,6
Up Type=0
Dn Type=3
Dn Slope=0.005
Boundary for River Rch & Prof#=FOLSOM CREEK,Reach-1,7
Up Type=0
Dn Type=3
Dn Slope=0.005

--- FOLSOM CREEK.g01 (geometry) ---

Geom Title=Existing Conditions

River Reach=FOLSOM CREEK,Reach-1
Reach XY= 30
      3624770.25     10573831.00      3625179.50     10575851.00
      3624940.50     10576381.00      3625148.75     10576414.00
      3625066.00     10576659.00      3625278.00     10576790.00
      3624571.50     10577456.00      3624710.25     10577701.00
      3624474.00     10577947.00      3624496.00     10578255.00
      3624715.50     10578207.00      3624876.00     10578605.00
      3624785.75     10578843.00      3624673.75     10578718.00
      3624493.00     10578881.00      3624390.75     10579671.00
      3624637.50     10579816.00      3624453.75     10580219.00
      3624809.25     10580735.00      3624813.75     10580957.00
      3624568.75     10580985.00      3624909.50     10581796.00
      3624651.50     10581918.00      3624808.50     10582099.00
      3624740.75     10582540.00      3624936.50     10582691.00
      3624827.00     10582833.00      3625559.25     10584400.00
      3625001.25     10586046.00      3625069.50     10586288.00

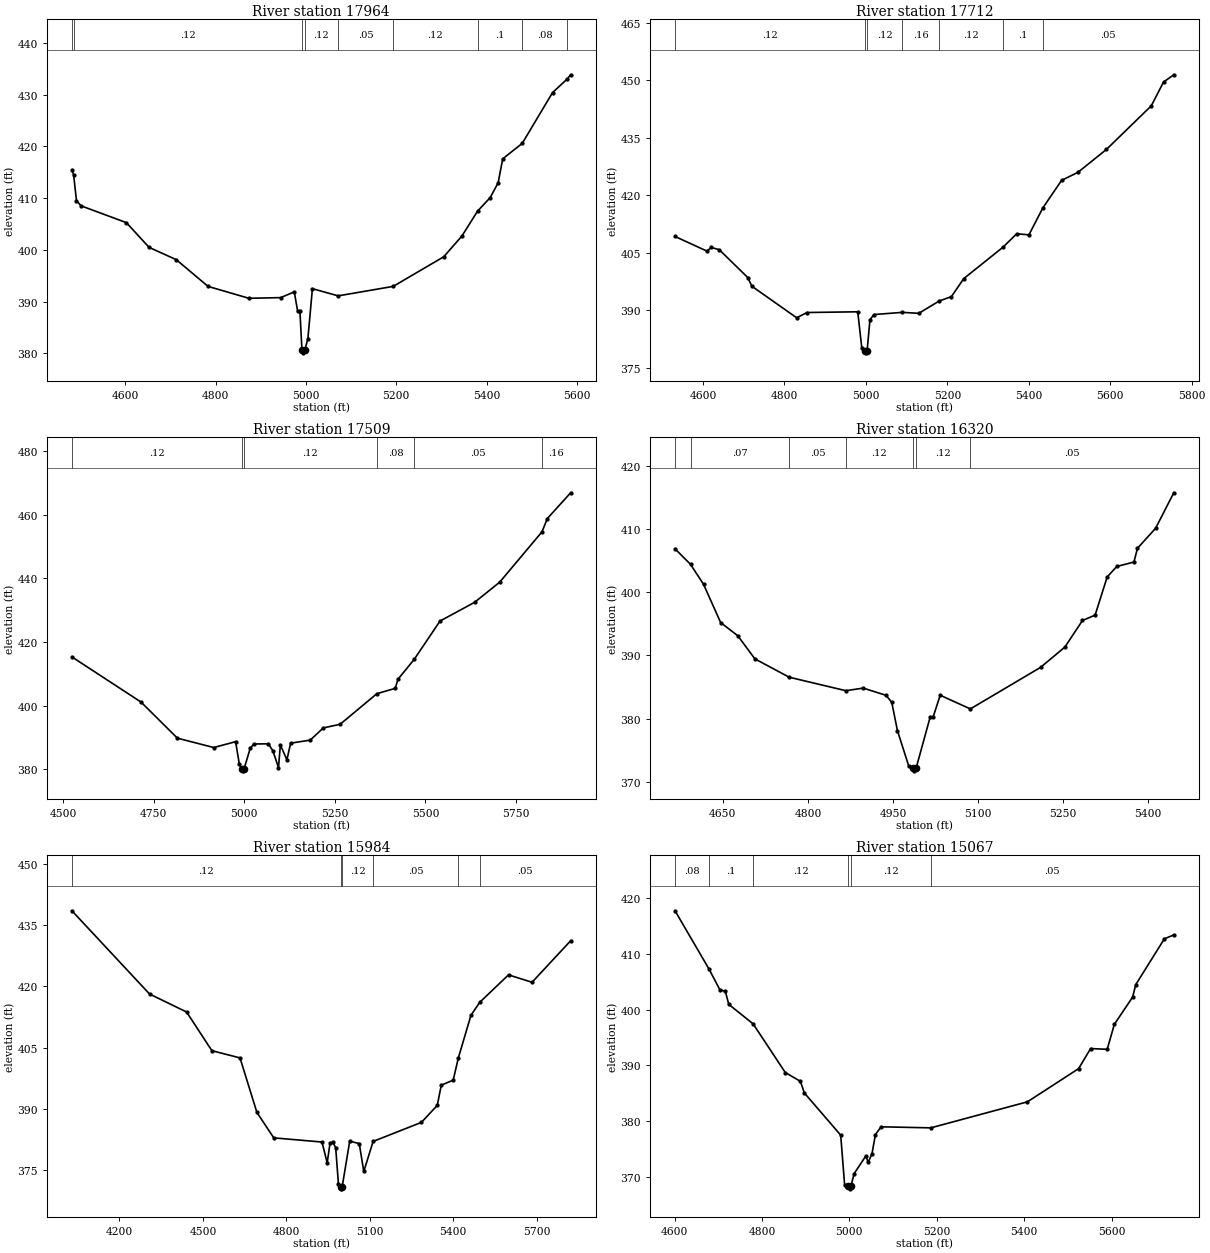
Type RM Length L Ch R = 1,17964,252,252,252
BEGIN DESCRIPTION:
FOLSOM CREEK 25.0
END DESCRIPTION:
XS GIS Cut Line= 3
      3624349.59     10574260.19      3624849.61     10574210.19
      3625449.62     10574260.19
#Sta/Elev= 30
  4481.8  415.49  4485.5  414.55  4491.9  409.54  4501.9  408.52  4602.4  405.27
  4652.7  400.49  4713.0  398.11  4783.3  392.95  4873.8  390.65  4944.1  390.78
  4974.3  391.89  4981.8  388.12  4986.8  388.12  4991.3  380.61  4994.1  380.11
  4997.3  380.61  5004.4  382.83  5014.4  392.51  5071.5  391.12  5193.4  392.95
  5305.4  398.68  5345.6  402.69  5380.1  407.48  5408.3  410.12  5425.8  412.97
  5435.9  417.60  5479.1  420.58  5546.3  430.40  5578.0  432.96  5586.4  433.84
#Mann=9,-1,0
  4481.8    0.05       0  4485.5    0.12       0  4991.3    0.07       0
  4997.3    0.12       0  5071.5    0.05       0  5193.4    0.12       0
  5380.1     0.1       0  5479.1    0.08       0  5578.0    0.05       0
Bank Sta=4991.3,4997.3
Exp/Cntr=0.3,0.1

Type RM Length L Ch R = 1,17712,203,203,203
BEGIN DESCRIPTION:
FOLSOM CREEK 23.0
END DESCRIPTION:
XS GIS Cut Line= 3
      3624430.94     10574450.41      3625021.26     10574459.09
      3625654.73     10574493.81
#Sta/Elev= 30
  4531.3  409.26  4610.0  405.43  4620.0  406.41  4640.0  405.81  4710.0  398.55
  4720.0  396.29  4830.0  388.07  4855.5  389.44  4980.0  389.63  4990.0  380.16
  4997.0  379.43  4999.8  378.93  5003.0  379.43  5010.0  387.59  5020.0  388.91
  5089.2  389.48  5130.0  389.23  5179.6  392.42  5210.2  393.60  5240.2  398.27
  5335.9  406.40  5370.4  409.96  5400.4  409.69  5434.8  416.75  5480.6  423.89
  5520.6  425.97  5590.7  431.95  5700.9  443.32  5730.9  449.51  5756.1  451.41
#Mann=7,-1,0
  4531.3    0.12       0  4997.0    0.07       0  5003.0    0.12       0
  5089.2    0.16       0  5179.6    0.12       0  5335.9     0.1       0
  5434.8    0.05       0
Bank Sta=4997,5003
Exp/Cntr=0.3,0.1

Type RM Length L Ch R = 1,17509,1189,1189,1189
BEGIN DESCRIPTION:
FOLSOM CREEK 24.0
END DESCRIPTION:
XS GIS Cut Line= 3
      3624399.57     10574610.18      3624949.61     10574660.19
      3625749.58     10574460.20
#Sta/Elev= 30
  4523.9  415.30  4714.7  401.12  4815.1  389.78  4915.5  386.84  4975.8  388.68
  4985.8  381.82  4992.9  380.02  4995.6  379.52  4998.9  380.02  5016.0  386.56
  5026.0  387.95  5066.2  388.01  5078.8  385.80  5094.2  380.52  5099.4  387.66
  5117.4  382.97  5127.7  388.21  5181.9  389.17  5217.9  393.00  5264.3  394.14
  5365.8  403.75  5416.4  405.42  5424.1  408.29  5468.7  414.51  5540.1  426.56
  5635.4  432.43  5705.0  438.79  5821.8  454.61  5836.4  458.77  5900.8  466.85
#Mann=6,-1,0
  4523.9    0.12       0  4992.9    0.07       0  4998.9    0.12       0
  5365.8    0.08       0  5468.7    0.05       0  5821.8    0.16       0
Bank Sta=4992.9,4998.9
Exp/Cntr=0.3,0.1

Type RM Length L Ch R = 1,16320,336,336,336
BEGIN DESCRIPTION:
FOLSOM CREEK 22.0
END DESCRIPTION:
XS GIS Cut Line= 3
      3624599.58     10575510.19      3625049.61     10575460.19
      3625449.61     10575310.19
#Sta/Elev= 30
  4565.6  406.84  4592.9  404.39  4615.9  401.23  4646.1  395.18  4676.3  393.10
  4706.5  389.44  4767.1  386.54  4867.0  384.41  4897.7  384.82  4937.9  383.68
  4948.0  382.57  4958.0  378.10  4978.2  372.43  4985.2  372.24  4988.0  371.74
  4991.2  372.24  5015.9  380.29  5021.1  380.29  5033.5  383.69  5086.7  381.53
  5210.6  388.10  5253.4  391.30  5284.5  395.51  5306.8  396.36  5328.1  402.39
  5345.0  404.05  5375.3  404.75  5381.5  406.92  5413.6  410.10  5445.6  415.70
#Mann=7,-1,0
  4565.6    0.12       0  4592.9    0.07       0  4767.1    0.05       0
  4867.0    0.12       0  4985.2    0.07       0  4991.2    0.12       0
  5086.7    0.05       0
Bank Sta=4985.2,4991.2
Exp/Cntr=0.3,0.1

Type RM Length L Ch R = 1,15984,917,917,917
BEGIN DESCRIPTION:
FOLSOM CREEK 21.0
END DESCRIPTION:
XS GIS Cut Line= 3
      3624161.92     10575856.66      3625272.99     10575691.73
      3625705.81     10575181.01
#Sta/Elev= 30
  4029.2  438.53  4308.3  418.15  4441.4  413.75  4532.3  404.28  4633.4  402.51
  4694.1  389.17  4754.7  382.94  4928.1  381.92  4946.8  376.81  4956.9  381.65
  4967.1  381.84  4977.2  380.58  4987.3  371.55  4994.6  370.96  4997.3  370.46
  5000.6  370.96  5027.7  382.13  5062.0  381.54  5078.3  374.72  5111.9  382.07
  5285.5  386.73  5342.5  390.89  5356.8  395.84  5399.7  397.07  5417.8  402.41
  5463.4  412.92  5494.9  416.11  5598.5  422.84  5683.1  421.03  5821.9  431.19
#Mann=6,-1,0
  4029.2    0.12       0  4994.6    0.07       0  5000.6    0.12       0
  5111.9    0.05       0  5417.8    0.08       0  5494.9    0.05       0
Bank Sta=4994.6,5000.6
Exp/Cntr=0.3,0.1

Type RM Length L Ch R = 1,15067,730,730,730
BEGIN DESCRIPTION:
FOLSOM CREEK 20.0
END DESCRIPTION:
XS GIS Cut Line= 3
      3624599.62     10576110.19      3625049.61     10576210.19
      3625699.57     10576010.20
#Sta/Elev= 30
  4601.2  417.68  4679.4  407.19  4703.6  403.57  4716.4  403.25  4724.1  400.94
  4779.8  397.45  4853.4  388.74  4888.0  387.17  4897.0  385.09  4980.2  377.54
  4989.2  368.60  4997.7  368.43  5000.4  367.93  5003.7  368.43  5010.9  370.64
  5037.8  373.83  5043.0  372.66  5051.9  374.25  5059.6  377.63  5072.6  379.03
  5186.3  378.84  5407.4  383.50  5524.5  389.44  5551.9  393.03  5589.9  392.89
  5606.2  397.36  5648.1  402.24  5655.3  404.48  5720.7  412.67  5742.2  413.35
#Mann=6,-1,0
  4601.2    0.08       0  4679.4     0.1       0  4779.8    0.12       0
  4997.7    0.07       0  5003.7    0.12       0  5186.3    0.05       0
Bank Sta=4997.7,5003.7
Exp/Cntr=0.3,0.1

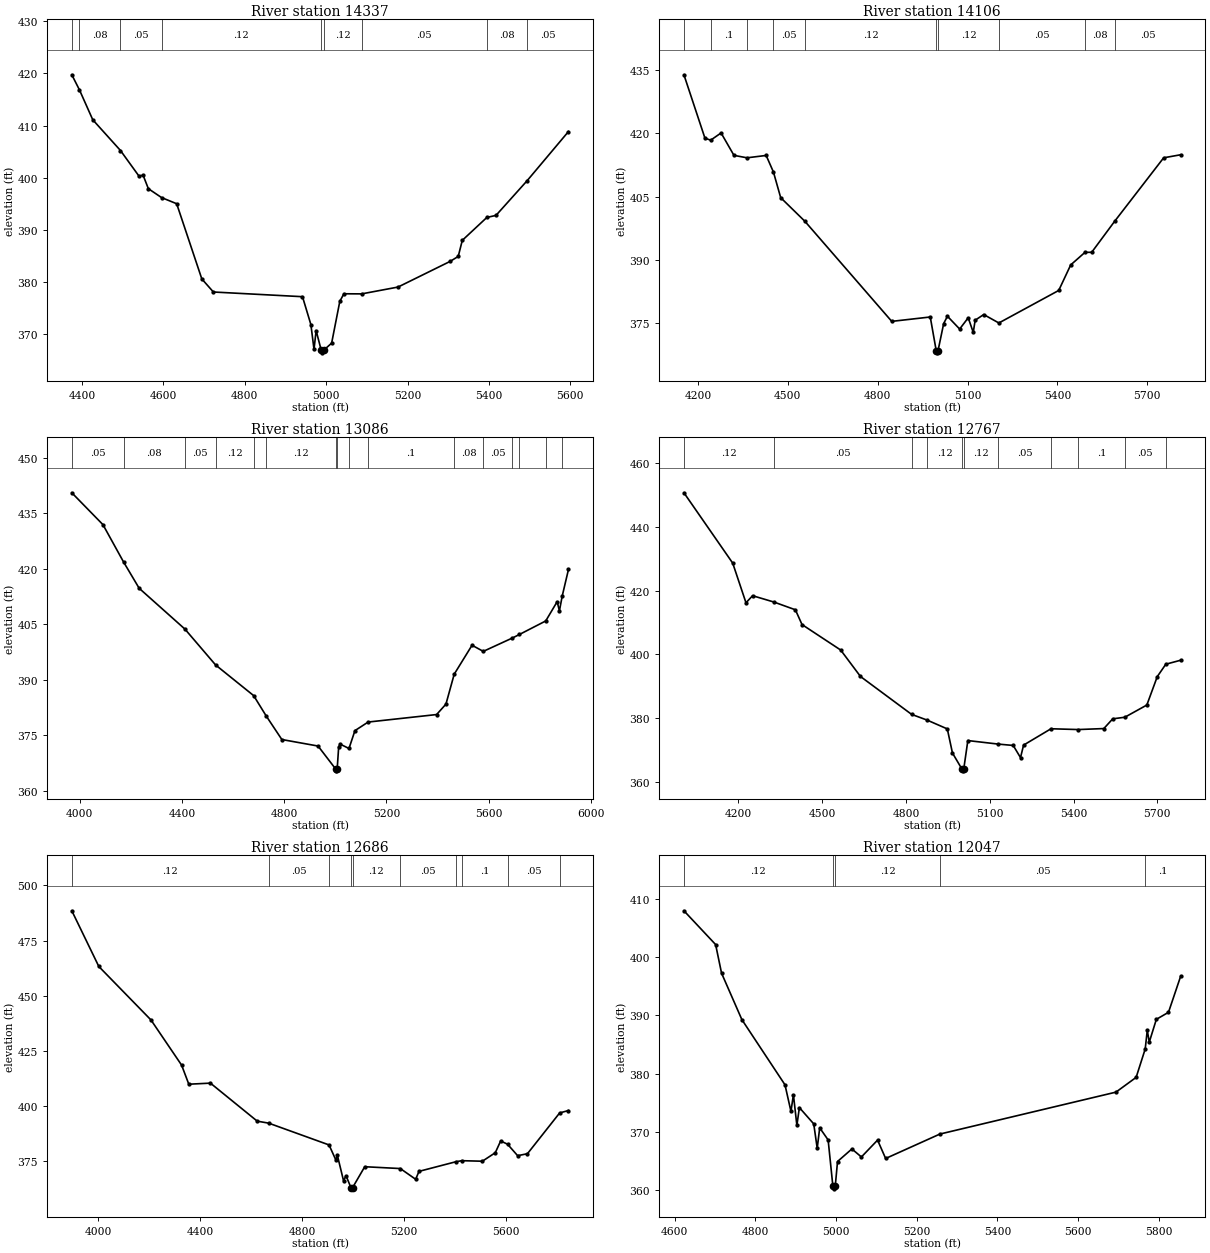
Type RM Length L Ch R = 1,14337,231,231,231
BEGIN DESCRIPTION:
FOLSOM CREEK 19.0
END DESCRIPTION:
XS GIS Cut Line= 3
      3624549.63     10576360.19      3625149.61     10576510.19
      3625749.59     10576560.19
#Sta/Elev= 30
  4375.0  419.75  4393.7  416.86  4426.5  411.11  4494.6  405.21  4539.9  400.31
  4550.2  400.46  4563.1  397.88  4595.6  396.17  4632.7  394.99  4694.5  380.55
  4722.9  378.04  4941.9  377.14  4962.5  371.79  4970.2  367.04  4975.4  370.64
  4987.9  366.86  4990.6  366.36  4993.9  366.86  5013.5  368.22  5033.6  376.25
  5043.6  377.70  5087.3  377.68  5176.6  378.99  5304.5  383.91  5324.6  384.87
  5334.6  387.96  5395.0  392.36  5417.4  392.75  5493.9  399.41  5595.5  408.85
#Mann=9,-1,0
  4375.0     0.1       0  4393.7    0.08       0  4494.6    0.05       0
  4595.6    0.12       0  4987.9    0.07       0  4993.9    0.12       0
  5087.3    0.05       0  5395.0    0.08       0  5493.9    0.05       0
Bank Sta=4987.9,4993.9
Exp/Cntr=0.3,0.1

Type RM Length L Ch R = 1,14106,1020,1020,1020
BEGIN DESCRIPTION:
FOLSOM CREEK 18.0
END DESCRIPTION:
XS GIS Cut Line= 4
      3624284.28     10576396.60      3625023.86     10576688.26
      3625232.19     10576594.51      3625866.09     10576620.49
#Sta/Elev= 30
  4153.3  433.90  4223.5  418.84  4242.7  418.38  4277.3  420.09  4320.3  414.77
  4363.9  414.19  4427.8  414.75  4452.1  410.81  4476.3  404.73  4556.8  399.14
  4847.0  375.36  4975.6  376.40  4995.5  368.39  4998.2  367.89  5001.5  368.39
  5020.4  374.85  5032.9  376.58  5073.7  373.54  5102.3  376.21  5119.1  372.75
  5125.5  375.64  5154.1  376.98  5204.6  374.98  5404.4  382.70  5444.4  388.76
  5492.1  391.75  5514.5  391.76  5591.0  399.11  5754.7  414.19  5811.2  414.91
#Mann=10,-1,0
  4153.3    0.05       0  4242.7     0.1       0  4363.9    0.08       0
  4452.1    0.05       0  4556.8    0.12       0  4995.5    0.07       0
  5001.5    0.12       0  5204.6    0.05       0  5492.1    0.08       0
  5591.0    0.05       0
Bank Sta=4995.5,5001.5
Exp/Cntr=0.3,0.1

Type RM Length L Ch R = 1,13086,319,319,319
BEGIN DESCRIPTION:
FOLSOM CREEK 17.0
END DESCRIPTION:
XS GIS Cut Line= 3
      3624199.60     10576460.18      3624999.61     10577060.19
      3625799.60     10577560.18
#Sta/Elev= 30
  3969.0  440.59  4090.9  431.96  4171.3  421.89  4232.6  414.75  4411.6  403.71
  4531.7  394.00  4680.6  385.71  4729.7  380.20  4790.9  373.83  4932.6  372.07
  5001.4  365.86  5004.1  365.36  5007.4  365.86  5013.2  371.79  5019.1  372.58
  5053.6  371.41  5076.9  376.24  5128.5  378.56  5396.5  380.59  5433.0  383.41
  5465.3  391.51  5535.1  399.34  5579.1  397.68  5693.0  401.30  5720.7  402.26
  5823.4  405.91  5868.2  411.13  5877.0  408.64  5888.1  412.70  5912.4  419.84
#Mann=16,-1,0
  3969.0    0.05       0  4171.3    0.08       0  4411.6    0.05       0
  4531.7    0.12       0  4680.6    0.07       0  4729.7    0.12       0
  5001.4    0.07       0  5007.4    0.12       0  5053.6    0.05       0
  5128.5     0.1       0  5465.3    0.08       0  5579.1    0.05       0
  5693.0    0.08       0  5720.7    0.05       0  5823.4    0.08       0
  5888.1    0.05       0
Bank Sta=5001.4,5007.4
Exp/Cntr=0.3,0.1

Type RM Length L Ch R = 1,12767,81,81,81
BEGIN DESCRIPTION:
Mapping XS db5db949
END DESCRIPTION:
XS GIS Cut Line= 6
      3624059.86     10576578.99      3624513.00     10576769.97
      3624735.23     10577070.32      3624763.00     10577124.14
      3624825.50     10577292.54      3625464.41     10577500.88
#Sta/Elev= 30
  4005.4  450.79  4180.0  428.68  4227.5  416.21  4251.2  418.43  4327.5  416.44
  4404.4  414.00  4428.1  409.36  4566.5  401.35  4637.4  393.03  4820.4  381.12
  4876.3  379.31  4948.2  376.55  4966.6  368.98  5000.9  363.87  5003.7  363.37
  5006.9  363.87  5021.7  372.89  5130.4  371.78  5184.1  371.35  5210.2  367.52
  5221.2  371.46  5319.4  376.60  5416.8  376.35  5508.4  376.66  5540.3  379.72
  5583.5  380.22  5662.4  384.06  5699.8  393.00  5730.3  396.89  5783.2  398.14
#Mann=11,-1,0
  4005.4    0.12       0  4327.5    0.05       0  4820.4    0.07       0
  4876.3    0.12       0  5000.9    0.07       0  5006.9    0.12       0
  5130.4    0.05       0  5319.4    0.15       0  5416.8     0.1       0
  5583.5    0.05       0  5730.3    0.08       0
Bank Sta=5000.9,5006.9
Exp/Cntr=0.3,0.1

Type RM Length L Ch R = 1,12686,639,639,639
BEGIN DESCRIPTION:
FOLSOM CREEK 16.0
END DESCRIPTION:
XS GIS Cut Line= 6
      3623899.61     10576460.19      3624610.23     10577146.27
      3624693.56     10577178.82      3624722.20     10577242.63
      3624814.65     10577355.91      3625445.42     10577541.89
#Sta/Elev= 30
  3896.1  488.46  4002.2  463.25  4207.2  439.03  4327.4  418.61  4355.7  409.97
  4440.6  410.46  4624.5  393.25  4669.5  392.35  4906.6  382.49  4933.7  375.57
  4939.1  377.88  4963.5  366.29  4973.3  368.54  4992.8  363.12  4995.5  362.62
  4998.8  363.12  5046.8  372.63  5186.6  371.80  5246.8  366.95  5260.0  370.53
  5404.8  374.88  5427.7  375.36  5508.9  375.12  5559.6  378.96  5580.8  384.28
  5607.8  382.82  5647.4  377.63  5685.9  378.51  5812.5  396.97  5847.1  398.06
#Mann=10,-1,0
  3896.1    0.12       0  4669.5    0.05       0  4906.6    0.12       0
  4992.8    0.07       0  4998.8    0.12       0  5186.6    0.05       0
  5404.8    0.15       0  5427.7     0.1       0  5607.8    0.05       0
  5812.5    0.08       0
Bank Sta=4992.8,4998.8
Exp/Cntr=0.3,0.1

Type RM Length L Ch R = 1,12047,316,316,316
BEGIN DESCRIPTION:
FOLSOM CREEK 15.0
END DESCRIPTION:
XS GIS Cut Line= 3
      3624249.65     10577360.22      3624599.61     10577610.19
      3625399.58     10577560.19
#Sta/Elev= 30
  4622.8  408.00  4701.4  402.19  4716.1  397.27  4766.5  389.28  4873.4  378.07
  4888.2  373.50  4894.3  376.36  4902.9  371.09  4909.1  374.15  4944.7  371.35
  4953.3  367.15  4959.5  370.67  4980.4  368.59  4992.1  360.68  4994.9  360.18
  4998.1  360.68  5003.7  364.88  5039.3  367.04  5062.9  365.66  5103.0  368.56
  5123.0  365.40  5257.5  369.60  5694.1  376.81  5744.2  379.35  5766.7  384.24
  5771.8  387.44  5776.8  385.42  5794.3  389.33  5824.4  390.54  5854.4  396.70
#Mann=5,-1,0
  4622.8    0.12       0  4992.1    0.07       0  4998.1    0.12       0
  5257.5    0.05       0  5766.7     0.1       0
Bank Sta=4992.1,4998.1
Exp/Cntr=0.3,0.1

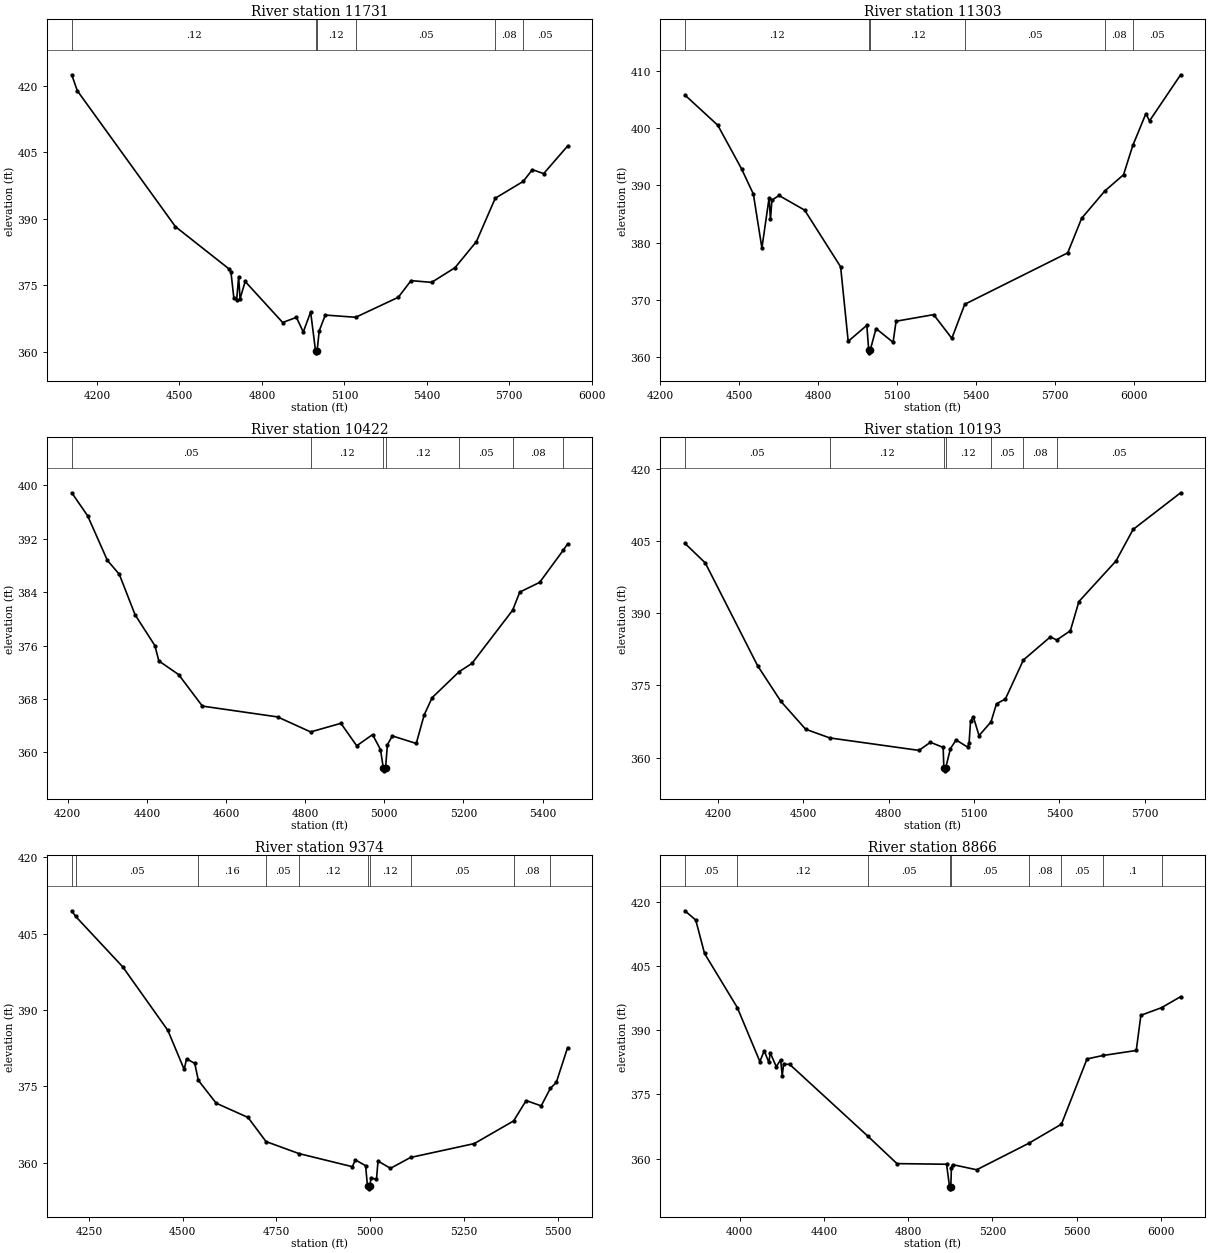
Type RM Length L Ch R = 1,11731,428,428,428
BEGIN DESCRIPTION:
FOLSOM CREEK 14.0
END DESCRIPTION:
XS GIS Cut Line= 3
      3623810.28     10577547.63      3624763.44     10577802.84
      3625565.04     10577646.69
#Sta/Elev= 30
  4108.4  422.43  4128.4  418.84  4485.6  388.17  4680.6  378.64  4687.4  377.95
  4697.8  372.18  4708.1  371.65  4715.4  376.84  4720.6  371.92  4739.2  375.81
  4875.6  366.56  4925.5  367.72  4950.5  364.42  4977.3  368.92  4995.0  360.22
  4997.7  359.72  5001.0  360.22  5008.4  364.66  5030.6  368.24  5141.1  367.74
  5296.1  372.25  5342.6  376.01  5417.2  375.61  5502.6  378.93  5580.3  384.82
  5648.8  394.59  5750.4  398.38  5784.0  401.04  5824.8  400.13  5911.8  406.35
#Mann=6,-1,0
  4108.4    0.12       0  4995.0    0.07       0  5001.0    0.12       0
  5141.1    0.05       0  5648.8    0.08       0  5750.4    0.05       0
Bank Sta=4995,5001
Exp/Cntr=0.3,0.1

Type RM Length L Ch R = 1,11303,881,881,881
BEGIN DESCRIPTION:
FOLSOM CREEK 13.0
END DESCRIPTION:
XS GIS Cut Line= 4
      3623773.83     10577938.25      3624273.86     10578094.51
      3624664.49     10578037.22      3625574.01     10577714.99
#Sta/Elev= 30
  4294.0  405.77  4419.2  400.48  4509.6  392.86  4554.3  388.47  4586.8  379.04
  4614.1  387.80  4619.3  384.05  4624.8  387.40  4651.8  388.22  4749.2  385.66
  4885.8  375.77  4914.6  362.76  4985.4  365.55  4992.5  361.25  4995.3  360.75
  4998.5  361.25  5020.4  364.99  5085.1  362.59  5096.6  366.27  5239.3  367.42
  5308.4  363.28  5357.5  369.23  5748.6  378.20  5801.6  384.24  5889.5  389.00
  5960.7  391.84  5995.9  396.95  6045.6  402.50  6059.4  401.24  6177.6  409.29
#Mann=6,-1,0
  4294.0    0.12       0  4992.5    0.07       0  4998.5    0.12       0
  5357.5    0.05       0  5889.5    0.08       0  5995.9    0.05       0
Bank Sta=4992.5,4998.5
Exp/Cntr=0.3,0.1

Type RM Length L Ch R = 1,10422,229,229,229
BEGIN DESCRIPTION:
FOLSOM CREEK 12.0
END DESCRIPTION:
XS GIS Cut Line= 3
      3623999.66     10578510.19      3624799.61     10578510.19
      3625249.59     10578560.19
#Sta/Elev= 30
  4210.3  398.89  4250.3  395.45  4300.3  388.76  4330.3  386.69  4370.3  380.61
  4420.3  375.99  4430.3  373.70  4480.3  371.65  4540.3  366.93  4730.3  365.31
  4813.8  363.06  4890.3  364.35  4930.3  360.98  4970.3  362.66  4990.3  360.42
  4997.3  357.73  5000.0  357.23  5003.3  357.73  5007.8  361.14  5020.3  362.46
  5080.7  361.33  5100.8  365.62  5120.9  368.20  5189.4  372.10  5221.5  373.33
  5324.3  381.30  5342.3  384.01  5392.6  385.47  5452.5  390.32  5463.0  391.23
#Mann=7,-1,0
  4210.3    0.05       0  4813.8    0.12       0  4997.3    0.07       0
  5003.3    0.12       0  5189.4    0.05       0  5324.3    0.08       0
  5452.5    0.05       0
Bank Sta=4997.3,5003.3
Exp/Cntr=0.3,0.1

Type RM Length L Ch R = 1,10193,819,819,819
BEGIN DESCRIPTION:
FOLSOM CREEK 11.0
END DESCRIPTION:
XS GIS Cut Line= 4
      3623909.24     10578526.80      3624398.86     10578630.97
      3625018.65     10578698.68      3625636.50     10578657.14
#Sta/Elev= 30
  4082.9  404.53  4154.8  400.44  4338.9  379.07  4420.7  371.67  4507.6  365.89
  4592.3  364.08  4906.1  361.49  4946.4  363.17  4991.2  362.11  4993.7  357.74
  4996.4  357.24  4999.7  357.74  5016.8  361.87  5036.9  363.66  5077.1  362.17
  5082.5  363.09  5087.5  367.58  5097.3  368.46  5117.4  364.56  5159.3  367.40
  5178.8  371.18  5209.9  372.15  5273.3  380.27  5368.3  385.08  5390.4  384.43
  5438.4  386.34  5468.5  392.42  5598.8  400.84  5658.9  407.39  5826.2  415.02
#Mann=7,-1,0
  4082.9    0.05       0  4592.3    0.12       0  4993.7    0.07       0
  4999.7    0.12       0  5159.3    0.05       0  5273.3    0.08       0
  5390.4    0.05       0
Bank Sta=4993.7,4999.7
Exp/Cntr=0.3,0.1

Type RM Length L Ch R = 1,9374,508,508,508
BEGIN DESCRIPTION:
FOLSOM CREEK 10.0
END DESCRIPTION:
XS GIS Cut Line= 3
      3623849.65     10578560.22      3624499.61     10579060.19
      3624999.60     10579110.19
#Sta/Elev= 30
  4204.2  409.49  4214.2  408.41  4340.1  398.48  4460.6  385.98  4504.1  378.32
  4510.4  380.40  4532.2  379.52  4541.8  376.19  4589.3  371.70  4674.4  368.89
  4722.3  364.16  4810.0  361.80  4952.6  359.22  4960.8  360.55  4987.9  359.42
  4993.1  355.37  4995.9  354.87  4999.1  355.37  5002.4  357.03  5017.0  356.73
  5021.1  360.33  5054.4  358.90  5107.8  361.03  5278.0  363.76  5382.8  368.21
  5416.2  372.21  5456.4  371.17  5480.7  374.60  5496.6  375.76  5526.7  382.60
#Mann=10,-1,0
  4204.2    0.16       0  4214.2    0.05       0  4541.8    0.16       0
  4722.3    0.05       0  4810.0    0.12       0  4993.1    0.07       0
  4999.1    0.12       0  5107.8    0.05       0  5382.8    0.08       0
  5480.7    0.05       0
Bank Sta=4993.1,4999.1
Exp/Cntr=0.3,0.1

Type RM Length L Ch R = 1,8866,356,356,356
BEGIN DESCRIPTION:
FOLSOM CREEK 9.0
END DESCRIPTION:
XS GIS Cut Line= 5
      3623419.72     10578667.45      3624159.28     10579318.47
      3624513.44     10579479.93      3624945.74     10579282.01
      3625330.37     10578954.55
#Sta/Elev= 30
  3739.3  417.88  3791.1  415.72  3832.9  407.91  3988.4  395.30  4095.7  382.69
  4116.5  385.20  4138.3  382.48  4145.0  384.72  4173.5  381.49  4194.3  383.09
  4201.9  379.41  4208.6  382.05  4237.0  382.04  4609.4  365.23  4746.9  358.86
  4982.5  358.71  4996.7  353.47  4999.4  352.97  5002.7  353.47  5005.6  357.91
  5011.1  358.63  5125.6  357.42  5373.7  363.62  5528.3  368.07  5649.8  383.30
  5727.0  384.11  5883.6  385.27  5905.6  393.48  6003.8  395.26  6094.4  397.83
#Mann=9,-1,0
  3739.3    0.05       0  3988.4    0.12       0  4609.4    0.05       0
  4996.7    0.03       0  5002.7    0.05       0  5373.7    0.08       0
  5528.3    0.05       0  5727.0     0.1       0  6003.8    0.05       0
Bank Sta=4996.7,5002.7
Exp/Cntr=0.3,0.1

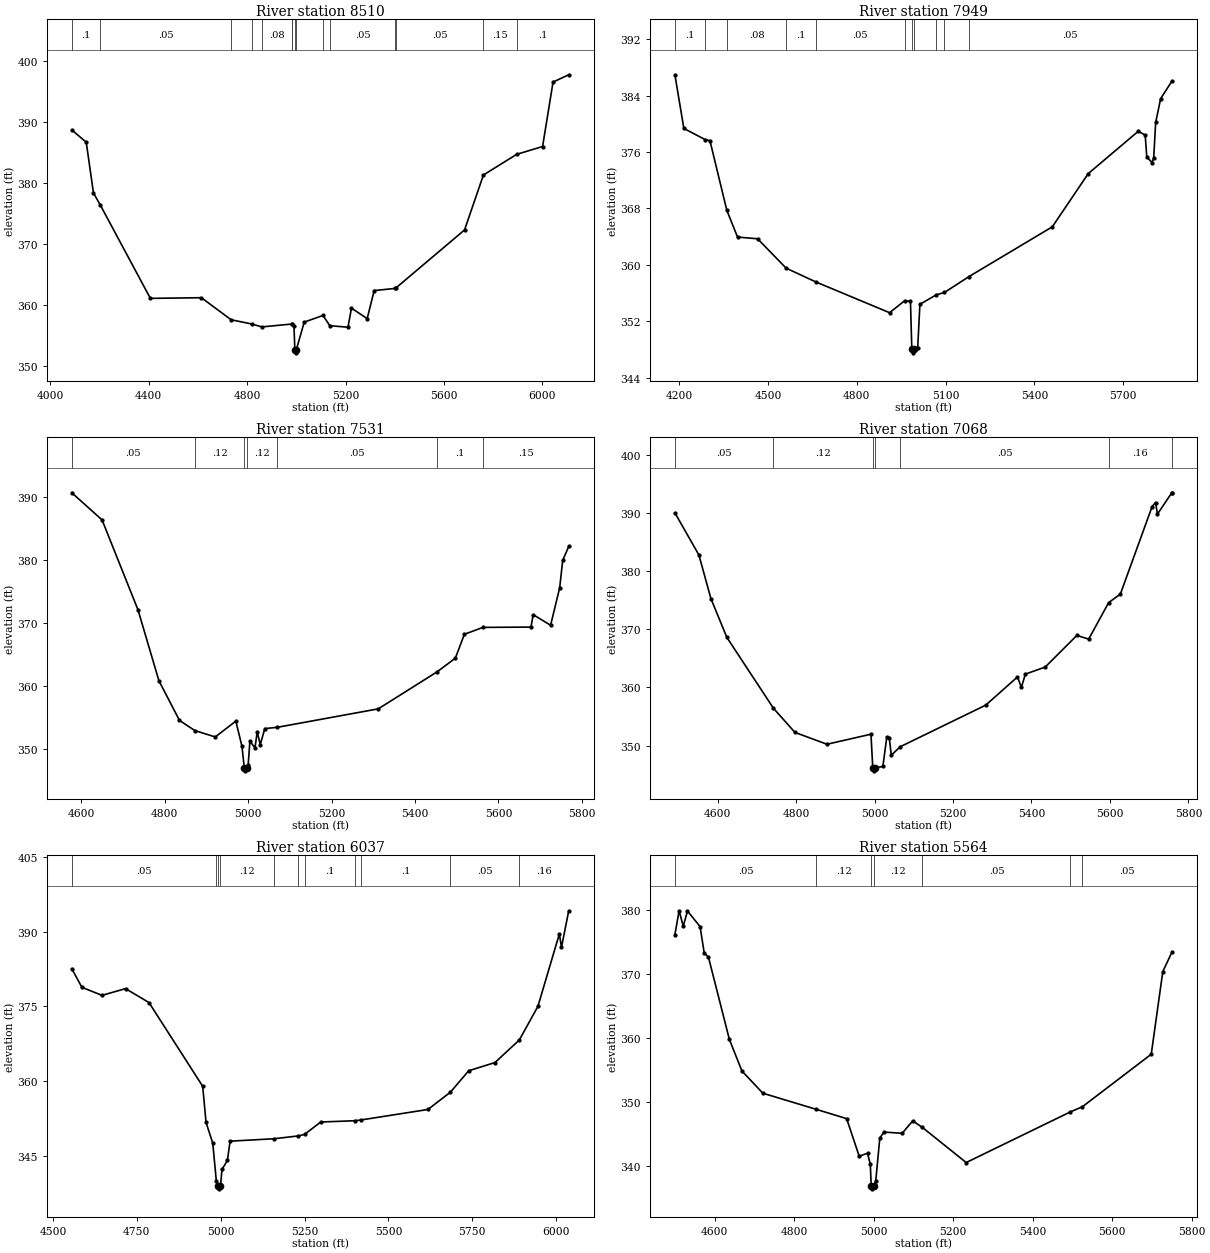
Type RM Length L Ch R = 1,8510,561,561,561
BEGIN DESCRIPTION:
FOLSOM CREEK 8.0
END DESCRIPTION:
XS GIS Cut Line= 6
      3623681.43     10580208.03      3624268.69     10579964.53
      3624514.87     10579672.87      3624719.74     10579497.52
      3624995.78     10579344.74      3625299.57     10579060.22
#Sta/Elev= 30
  4087.9  388.71  4146.5  386.70  4175.8  378.38  4204.2  376.36  4407.0  361.10
  4614.2  361.21  4735.3  357.59  4820.3  356.89  4859.5  356.42  4981.1  356.89
  4983.8  356.90  4990.4  356.61  4994.0  352.67  4996.7  352.17  5000.0  352.67
  5032.1  357.21  5108.5  358.30  5135.9  356.62  5209.8  356.37  5224.1  359.50
  5287.8  357.78  5316.3  362.38  5401.0  362.73  5403.8  362.78  5683.4  372.32
  5760.1  381.33  5895.0  384.71  6000.5  386.00  6043.0  396.57  6106.7  397.76
#Mann=15,-1,0
  4087.9     0.1       0  4204.2    0.05       0  4735.3    0.08       0
  4820.3    0.05       0  4859.5    0.08       0  4981.1    0.16       0
  4983.8    0.05       0  4994.0    0.04       0  5000.0    0.05       0
  5108.5    0.08       0  5135.9    0.05       0  5401.0    0.16       0
  5403.8    0.05       0  5760.1    0.15       0  5895.0     0.1       0
Bank Sta=4994,5000
Exp/Cntr=0.3,0.1

Type RM Length L Ch R = 1,7949,418,418,418
BEGIN DESCRIPTION:
FOLSOM CREEK 7.0
END DESCRIPTION:
XS GIS Cut Line= 3
      3623749.64     10580210.18      3624549.61     10580110.19
      3625349.60     10579760.19
#Sta/Elev= 30
  4185.1  386.96  4215.3  379.35  4287.4  377.77  4303.5  377.61  4360.6  367.73
  4396.7  363.95  4464.7  363.70  4560.9  359.54  4661.1  357.59  4910.7  353.22
  4961.6  354.92  4981.2  354.83  4985.8  348.03  4988.5  347.53  4991.8  348.03
  5005.7  348.28  5013.1  354.41  5068.6  355.76  5096.1  356.09  5178.4  358.33
  5460.6  365.40  5581.9  372.94  5751.1  378.95  5774.5  378.41  5779.9  375.32
  5797.8  374.50  5803.3  375.19  5809.9  380.20  5826.7  383.57  5864.5  386.04
#Mann=11,-1,0
  4185.1     0.1       0  4287.4    0.05       0  4360.6    0.08       0
  4560.9     0.1       0  4661.1    0.05       0  4961.6    0.16       0
  4985.8    0.07       0  4991.8    0.16       0  5068.6    0.05       0
  5096.1    0.16       0  5178.4    0.05       0
Bank Sta=4985.8,4991.8
Exp/Cntr=0.3,0.1

Type RM Length L Ch R = 1,7531,463,463,463
BEGIN DESCRIPTION:
FOLSOM CREEK 6.0
END DESCRIPTION:
XS GIS Cut Line= 3
      3624249.59     10580660.20      3624599.61     10580410.19
      3625299.60     10580110.19
#Sta/Elev= 30
  4577.0  390.64  4649.5  386.34  4735.5  372.13  4785.9  360.85  4835.1  354.58
  4872.0  352.96  4921.1  351.95  4970.3  354.46  4985.0  350.48  4990.6  347.08
  4993.4  346.58  4996.6  347.08  4999.8  347.46  5004.1  351.27  5016.2  350.22
  5021.6  352.74  5028.9  350.74  5039.8  353.27  5070.0  353.48  5311.8  356.40
  5453.6  362.29  5496.7  364.43  5518.5  368.22  5563.0  369.31  5678.1  369.36
  5683.5  371.33  5725.2  369.65  5747.0  375.58  5754.2  379.91  5768.7  382.15
#Mann=7,-1,0
  4577.0    0.05       0  4872.0    0.12       0  4990.6    0.07       0
  4996.6    0.12       0  5070.0    0.05       0  5453.6     0.1       0
  5563.0    0.15       0
Bank Sta=4990.6,4996.6
Exp/Cntr=0.3,0.1

Type RM Length L Ch R = 1,7068,1031,1031,1031
BEGIN DESCRIPTION:
FOLSOM CREEK 5.0
END DESCRIPTION:
XS GIS Cut Line= 3
      3624299.64     10580810.18      3624799.61     10580710.19
      3625549.60     10580610.19
#Sta/Elev= 30
  4491.2  390.07  4552.4  382.81  4582.9  375.31  4623.7  368.61  4742.3  356.42
  4797.1  352.26  4878.7  350.22  4990.9  351.95  4995.5  346.14  4998.3  345.64
  5001.5  346.14  5021.2  346.40  5031.3  351.46  5037.6  351.32  5042.7  348.33
  5065.2  349.78  5283.5  356.96  5364.3  361.81  5374.3  360.02  5384.4  362.30
  5434.9  363.51  5515.6  368.96  5545.8  368.33  5596.7  374.61  5626.6  376.09
  5707.3  391.13  5716.1  391.85  5721.1  389.86  5757.6  393.53  5757.7  393.53
#Mann=7,-1,0
  4491.2    0.05       0  4742.3    0.12       0  4995.5    0.07       0
  5001.5    0.12       0  5065.2    0.05       0  5596.7    0.16       0
  5757.6    0.05       0
Bank Sta=4995.5,5001.5
Exp/Cntr=0.3,0.1

Type RM Length L Ch R = 1,6037,473,473,473
BEGIN DESCRIPTION:
FOLSOM CREEK 4.0
END DESCRIPTION:
XS GIS Cut Line= 3
      3624249.60     10581310.19      3624699.61     10581310.19
      3625499.62     10580660.18
#Sta/Elev= 30
  4556.4  382.53  4586.4  378.81  4646.4  377.19  4716.4  378.55  4786.4  375.74
  4946.4  358.92  4956.4  351.65  4976.4  347.48  4987.0  339.91  4993.4  338.81
  4996.2  338.31  4999.4  338.81  5003.9  342.22  5020.0  344.01  5028.0  347.89
  5159.8  348.38  5231.8  348.95  5250.0  349.25  5298.1  351.74  5401.1  352.00
  5419.0  352.16  5617.7  354.26  5684.7  357.74  5739.1  362.04  5817.4  363.69
  5889.9  368.22  5945.3  374.97  6009.2  389.52  6015.6  386.86  6037.2  394.19
#Mann=11,-1,0
  4556.4    0.05       0  4987.0    0.12       0  4993.4    0.07       0
  4999.4    0.12       0  5159.8    0.16       0  5231.8    0.05       0
  5250.0     0.1       0  5401.1    0.15       0  5419.0     0.1       0
  5684.7    0.05       0  5889.9    0.16       0
Bank Sta=4993.4,4999.4
Exp/Cntr=0.3,0.1

Type RM Length L Ch R = 1,5564,543,543,543
BEGIN DESCRIPTION:
FOLSOM CREEK 3.0
END DESCRIPTION:
XS GIS Cut Line= 3
      3624399.60     10581860.19      3624849.61     10581710.19
      3625599.65     10581510.18
#Sta/Elev= 30
  4499.5  376.18  4510.0  379.90  4520.6  377.49  4531.1  379.87  4562.8  377.43
  4573.3  373.30  4583.8  372.68  4636.5  359.81  4668.2  354.86  4720.9  351.39
  4855.8  348.86  4931.7  347.42  4963.3  341.55  4984.2  342.01  4991.3  340.28
  4993.5  336.95  4996.2  336.45  4999.5  336.95  5004.9  337.66  5015.2  344.39
  5025.6  345.32  5071.5  345.13  5098.0  347.07  5122.4  346.04  5232.6  340.56
  5495.0  348.48  5524.8  349.27  5698.3  357.48  5727.4  370.40  5750.1  373.40
#Mann=7,-1,0
  4499.5    0.05       0  4855.8    0.12       0  4993.5    0.07       0
  4999.5    0.12       0  5122.4    0.05       0  5495.0    0.08       0
  5524.8    0.05       0
Bank Sta=4993.5,4999.5
Exp/Cntr=0.3,0.1

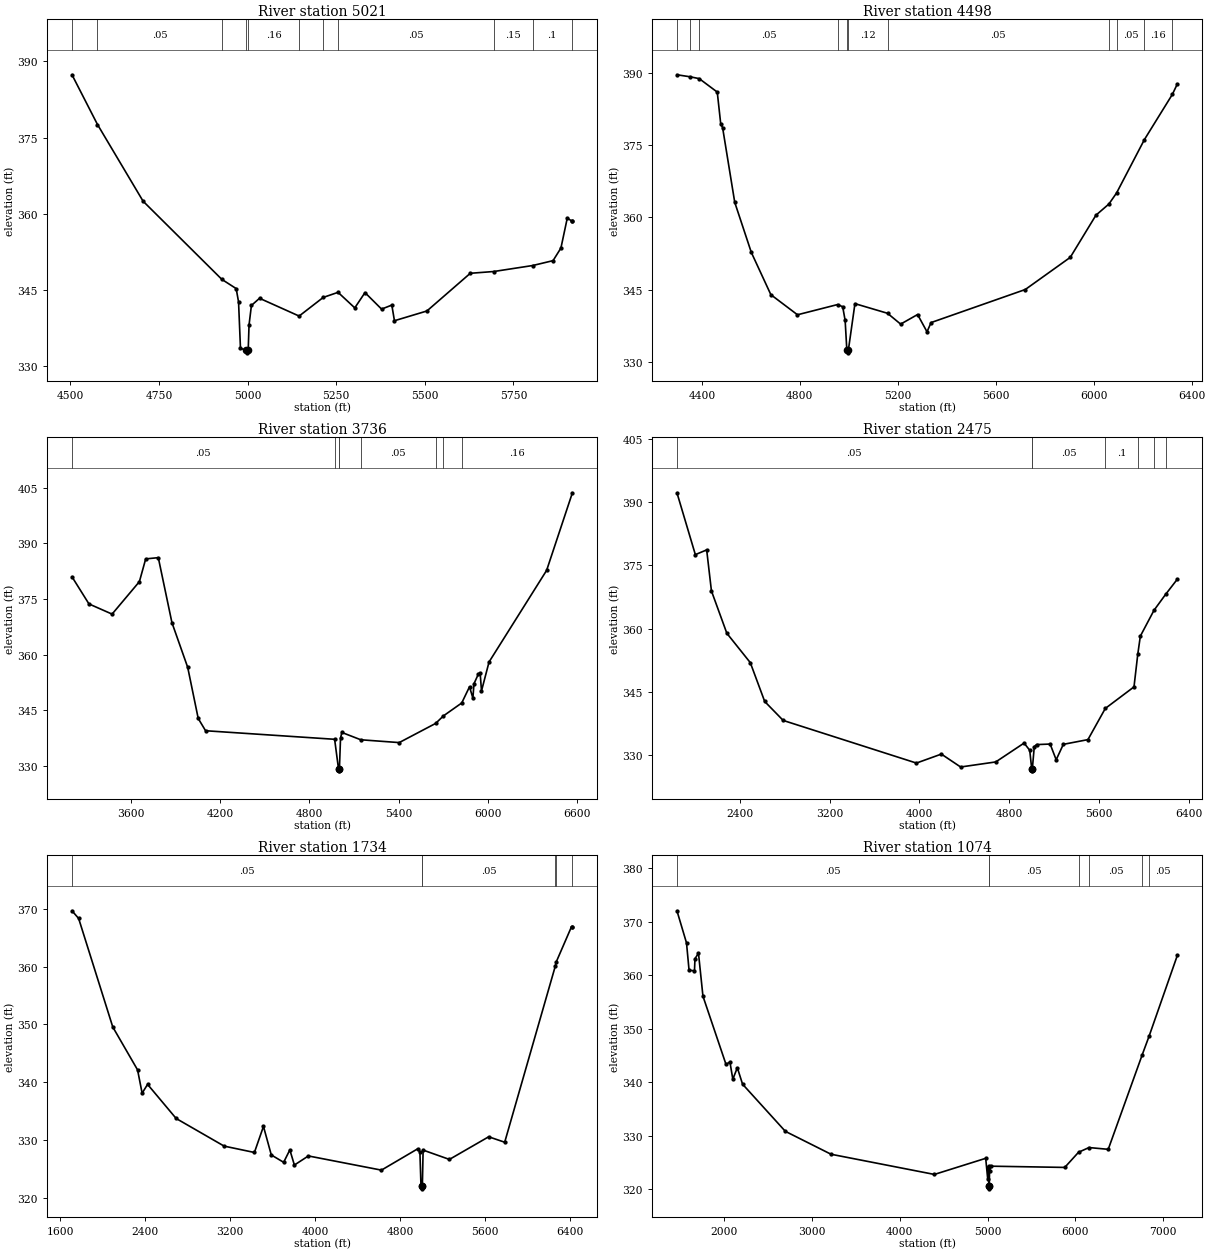
Type RM Length L Ch R = 1,5021,523,523,523
BEGIN DESCRIPTION:
FOLSOM CREEK 2.0
END DESCRIPTION:
XS GIS Cut Line= 3
      3624249.58     10582210.20      3624749.61     10582010.19
      3625549.64     10581660.17
#Sta/Elev= 30
  4504.6  387.38  4576.5  377.59  4705.2  362.49  4927.4  347.10  4967.8  345.29
  4974.5  342.66  4979.9  333.55  4995.7  333.14  4998.5  332.64  5001.7  333.14
  5004.1  338.14  5010.8  341.97  5033.7  343.38  5145.4  339.88  5213.4  343.55
  5255.2  344.55  5302.4  341.49  5331.2  344.50  5378.0  341.25  5406.9  342.04
  5414.3  338.96  5505.9  340.88  5628.3  348.30  5694.5  348.65  5804.4  349.83
  5861.8  350.79  5884.0  353.27  5901.9  359.16  5914.2  358.61  5916.4  358.61
#Mann=11,-1,0
  4504.6     0.1       0  4576.5    0.05       0  4927.4    0.16       0
  4995.7    0.07       0  5001.7    0.16       0  5145.4    0.12       0
  5213.4    0.16       0  5255.2    0.05       0  5694.5    0.15       0
  5804.4     0.1       0  5914.2    0.05       0
Bank Sta=4995.7,5001.7
Exp/Cntr=0.3,0.1

Type RM Length L Ch R = 1,4498,762,762,762
BEGIN DESCRIPTION:
Mapping XS ba6757a2
END DESCRIPTION:
XS GIS Cut Line= 4
      3624092.41     10582245.54      3624526.46     10582479.93
      3624969.17     10582453.89      3625950.05     10581941.75
#Sta/Elev= 30
  4298.1  389.59  4351.2  389.18  4389.1  388.79  4462.7  386.00  4476.8  379.43
  4484.6  378.60  4534.1  363.11  4601.8  352.72  4681.6  343.95  4790.3  339.78
  4953.9  341.90  4974.9  341.45  4984.9  338.60  4991.9  332.38  4994.6  331.88
  4997.9  332.38  5024.9  342.09  5157.9  340.09  5211.5  337.84  5280.7  339.83
  5319.2  336.24  5335.7  338.16  5720.4  345.02  5904.2  351.70  6009.0  360.45
  6061.8  362.76  6093.1  365.05  6207.0  376.15  6320.9  385.51  6341.4  387.69
#Mann=11,-1,0
  4298.1    0.15       0  4351.2     0.1       0  4389.1    0.05       0
  4953.9    0.12       0  4991.9    0.07       0  4997.9    0.12       0
  5157.9    0.05       0  6061.8    0.08       0  6093.1    0.05       0
  6207.0    0.16       0  6320.9    0.05       0
Bank Sta=4991.9,4997.9
Exp/Cntr=0.3,0.1

Type RM Length L Ch R = 1,3736,1261,1261,1261
BEGIN DESCRIPTION:
Mapping XS 9c126714
END DESCRIPTION:
XS GIS Cut Line= 4
      3623610.34     10582027.89      3624673.71     10583069.56
      3625368.15     10582863.39      3626323.05     10582212.32
#Sta/Elev= 30
  3201.7  380.99  3315.9  373.67  3471.5  370.92  3655.4  379.69  3697.8  385.83
  3782.7  386.17  3874.5  368.61  3980.7  356.53  4051.4  342.73  4100.9  339.42
  4969.7  337.11  4995.9  329.09  4998.7  328.59  5001.9  329.09  5009.4  337.40
  5018.2  338.96  5145.8  336.98  5404.4  336.22  5649.7  341.40  5702.4  343.44
  5825.4  346.92  5877.7  351.30  5900.6  348.21  5907.6  352.10  5936.9  354.69
  5949.5  354.95  5958.4  350.17  6009.2  357.99  6396.8  382.73  6570.4  403.69
#Mann=8,-1,0
  3201.7    0.05       0  4969.7    0.16       0  4995.9    0.07       0
  5001.9    0.16       0  5145.8    0.05       0  5649.7     0.1       0
  5702.4    0.08       0  5825.4    0.16       0
Bank Sta=4995.9,5001.9
Exp/Cntr=0.3,0.1

Type RM Length L Ch R = 1,2475,741,741,741
BEGIN DESCRIPTION:
Mapping XS 7f5428d8
END DESCRIPTION:
XS GIS Cut Line= 4
      3623219.74     10582342.59      3624467.55     10584143.77
      3625671.97     10583981.01      3626419.65     10583244.17
#Sta/Elev= 30
  1841.1  392.22  2005.0  377.56  2105.8  378.68  2148.3  368.95  2285.4  358.92
  2494.2  351.96  2622.6  342.75  2787.1  338.26  3973.8  328.15  4195.8  330.28
  4367.4  327.22  4680.2  328.42  4932.5  332.89  4982.9  331.18  5000.1  326.81
  5002.8  326.31  5006.1  326.81  5023.3  332.04  5043.5  332.53  5164.5  332.66
  5218.3  328.93  5281.9  332.59  5501.1  333.71  5655.8  341.10  5911.3  346.21
  5944.7  353.90  5967.8  358.24  6089.1  364.35  6192.0  368.11  6297.4  371.74
#Mann=7,-1,0
  1841.1    0.05       0  5000.1    0.03       0  5006.1    0.05       0
  5655.8     0.1       0  5944.7    0.05       0  6089.1    0.12       0
  6192.0    0.16       0
Bank Sta=5000.1,5006.1
Exp/Cntr=0.3,0.1

Type RM Length L Ch R = 1,1734,660,660,660
BEGIN DESCRIPTION:
Mapping XS 1d4e59f5
END DESCRIPTION:
XS GIS Cut Line= 4
      3623301.88     10582682.05      3624465.07     10584600.46
      3625680.35     10584730.66      3626661.26     10583966.77
#Sta/Elev= 30
  1710.5  369.63  1773.1  368.30  2094.2  349.56  2327.6  342.15  2370.3  338.13
  2421.7  339.65  2690.7  333.76  3142.0  328.99  3427.0  327.89  3512.3  332.39
  3586.0  327.46  3702.3  326.19  3760.5  328.34  3803.2  325.72  3935.0  327.29
  4622.3  324.84  4964.3  328.53  4984.4  327.93  4994.5  322.17  5001.5  322.11
  5004.3  321.61  5007.5  322.11  5014.6  328.30  5262.1  326.69  5631.6  330.60
  5782.3  329.66  6259.0  360.10  6268.2  360.83  6411.1  366.88  6419.5  366.90
#Mann=6,-1,0
  1710.5    0.05       0  5001.5    0.03       0  5007.5    0.05       0
  6259.0    0.16       0  6268.2    0.05       0  6411.1    0.16       0
Bank Sta=5001.5,5007.5
Exp/Cntr=0.3,0.1

Type RM Length L Ch R = 1,1074,637,637,637
BEGIN DESCRIPTION:
Mapping XS 6136f0b0
END DESCRIPTION:
XS GIS Cut Line= 4
      3623258.49     10582725.49      3624360.90     10585043.16
      3625593.54     10585425.11      3626912.96     10584140.42
#Sta/Elev= 30
  1462.3  372.03  1571.2  366.03  1600.4  360.91  1662.0  360.83  1667.6  363.07
  1707.5  364.12  1758.4  356.08  2021.2  343.33  2065.5  343.80  2098.7  340.58
  2150.1  342.72  2209.4  339.65  2696.7  330.84  3217.1  326.56  4393.9  322.79
  4978.3  325.80  5001.1  321.98  5010.9  324.41  5013.1  320.60  5015.9  320.10
  5019.1  320.60  5022.0  323.52  5042.9  324.33  5878.6  324.10  6035.3  326.93
  6154.6  327.81  6373.7  327.48  6761.3  345.16  6838.3  348.58  7160.8  363.70
#Mann=7,-1,0
  1462.3    0.05       0  5013.1    0.03       0  5019.1    0.05       0
  6035.3    0.16       0  6154.6    0.05       0  6761.3     0.1       0
  6838.3    0.05       0
Bank Sta=5013.1,5019.1
Exp/Cntr=0.3,0.1

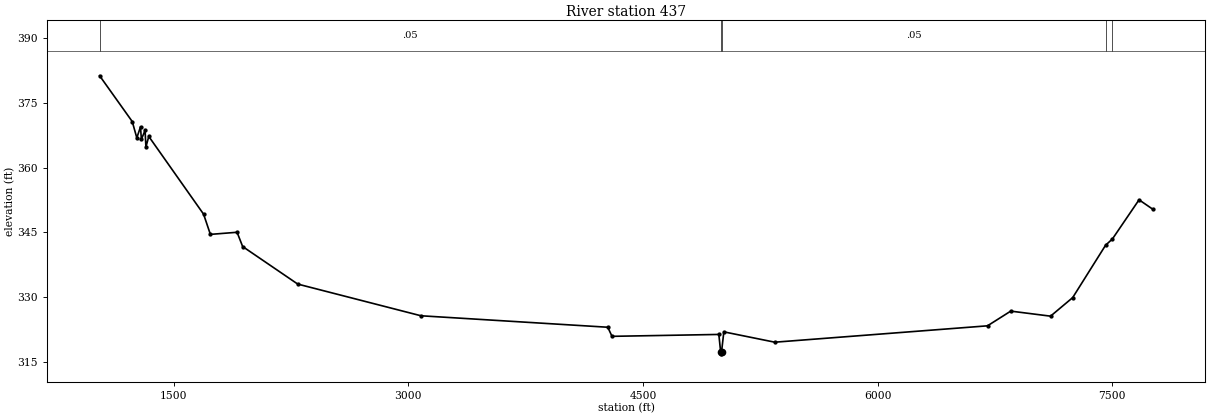
Type RM Length L Ch R = 1,437,0,0,0
BEGIN DESCRIPTION:
FOLSOM CREEK 1.0
END DESCRIPTION:
XS GIS Cut Line= 4
      3623111.21     10582668.09      3624380.00     10585666.43
      3625505.00     10586083.09      3627094.95     10584451.48
#Sta/Elev= 30
  1026.2  381.32  1234.8  370.70  1263.9  366.92  1287.6  369.48  1293.0  366.55
  1316.7  368.67  1322.1  364.81  1340.4  367.25  1690.8  349.22  1734.3  344.53
  1905.0  345.02  1940.6  341.71  2292.9  333.00  3080.7  325.65  4275.2  322.99
  4302.3  320.88  4985.3  321.32  4996.8  317.32  4999.5  316.82  5002.8  317.32
  5017.3  321.92  5343.1  319.52  6703.2  323.32  6851.8  326.73  7106.3  325.56
  7247.7  329.86  7458.1  342.01  7501.9  343.47  7672.1  352.55  7759.8  350.37
#Mann=5,-1,0
  1026.2    0.05       0  4996.8    0.03       0  5002.8    0.05       0
  7458.1     0.1       0  7501.9    0.05       0
Bank Sta=4996.8,5002.8
Exp/Cntr=0.3,0.1

Chan Stop Cuts=-1