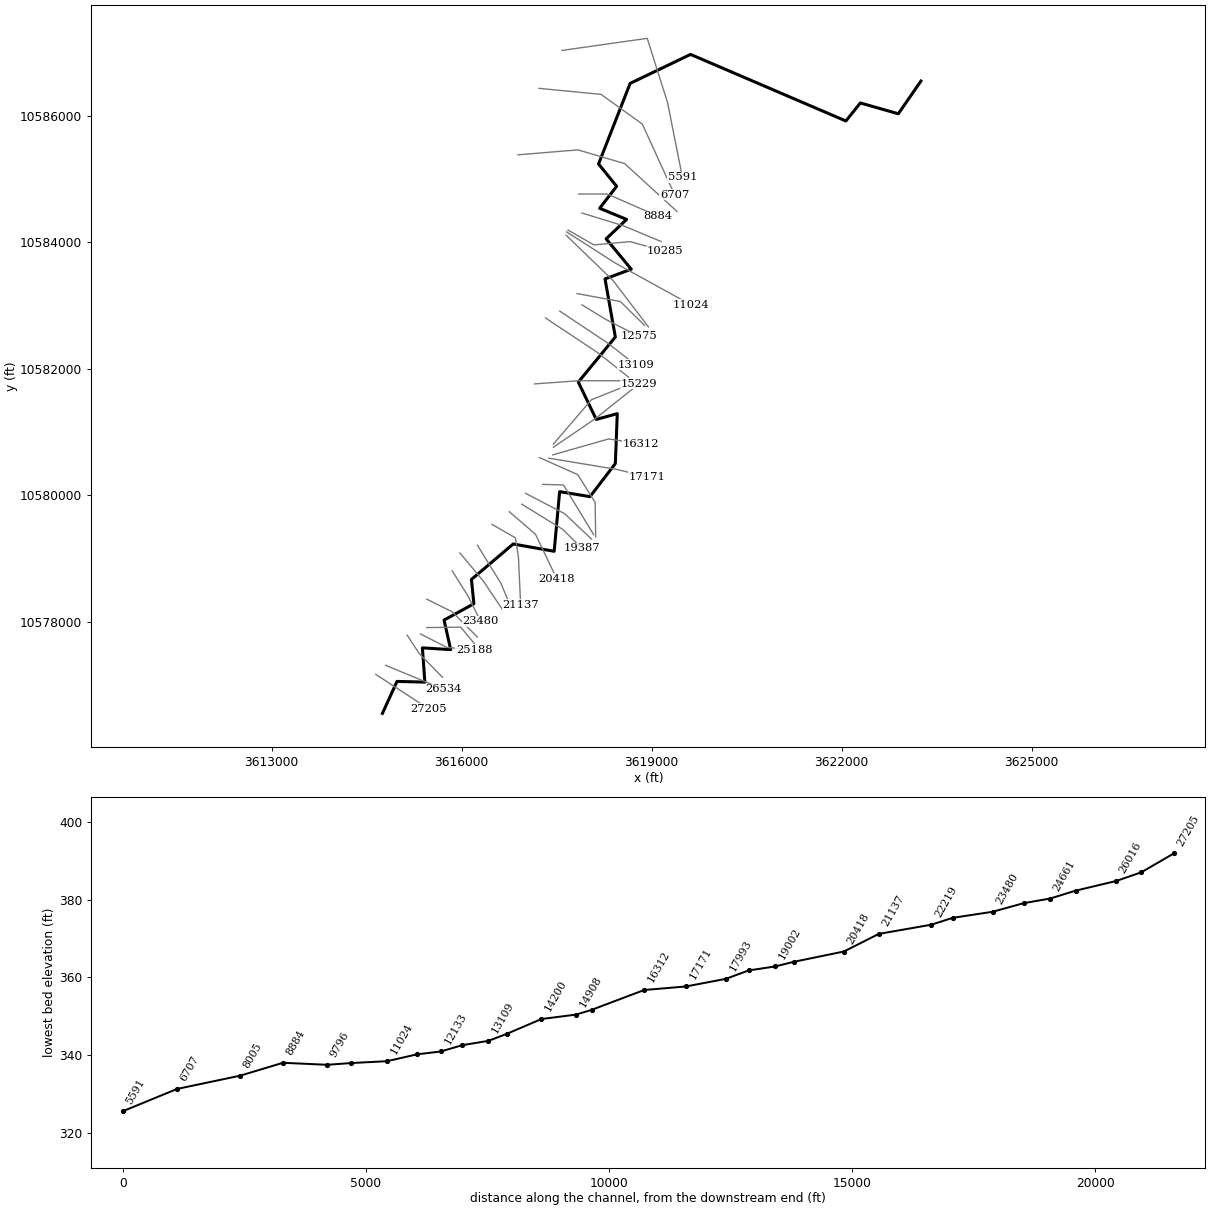
--- HOG CREEK 1.prj (project) ---

Proj Title=HOG CREEK 1 Base Level Engineering
Current Plan=p01
Default Exp/Contr=0.3,0.1
English Units
Geom File=g01
Flow File=f01
Plan File=p01
BEGIN DESCRIPTION:
HOG CREEK 1
END DESCRIPTION:

--- HOG CREEK 1.p01 (plan) ---

Plan Title=Multiple Run
Short Identifier=Multiple
Geom File=g01
Flow File=f01
Subcritical Flow
K Sum by GR= 0
Std Step Tol= 0.01
Critical Tol= 0.01
Num of Std Step Trials= 20
Max Error Tol= 0.3
Flow Tol Ratio= 0.001
Split Flow NTrial= 30
Split Flow Tol= 0.02
Split Flow Ratio= 0.02
Log Output Level= 0
Friction Slope Method= 1
Unsteady Friction Slope Method= 2
Unsteady Bridges Friction Slope Method= 1
Parabolic Critical Depth
Global Vel Dist=  1 , 1 , 1
Global Log Level= 0
CheckData=True
Encroach Param= -1, 0, 0, 0
BEGIN DESCRIPTION:
Multiple Run
END DESCRIPTION:

--- HOG CREEK 1.f01 (steady flow) ---

Flow Title=Multiple
Number of Profiles=7
Profile Names=10-year,25-year,50-year,1pct_min,100-year,1pct_plu,500-year
River Rch & RM= HOG CREEK 1,Reach-1,27205
    1875    2679    3370    3092    4181    5654    6414
River Rch & RM= HOG CREEK 1,Reach-1,17171
    2267    3268    4134    3811    5154    6970    7987
River Rch & RM= HOG CREEK 1,Reach-1,13487
    2580    3716    4698    4323    5847    7907    9030
Boundary for River Rch & Prof#=HOG CREEK 1,Reach-1,1
Up Type=0
Dn Type=3
Dn Slope=0.005
Boundary for River Rch & Prof#=HOG CREEK 1,Reach-1,2
Up Type=0
Dn Type=3
Dn Slope=0.005
Boundary for River Rch & Prof#=HOG CREEK 1,Reach-1,3
Up Type=0
Dn Type=3
Dn Slope=0.005
Boundary for River Rch & Prof#=HOG CREEK 1,Reach-1,4
Up Type=0
Dn Type=3
Dn Slope=0.005
Boundary for River Rch & Prof#=HOG CREEK 1,Reach-1,5
Up Type=0
Dn Type=3
Dn Slope=0.005
Boundary for River Rch & Prof#=HOG CREEK 1,Reach-1,6
Up Type=0
Dn Type=3
Dn Slope=0.005
Boundary for River Rch & Prof#=HOG CREEK 1,Reach-1,7
Up Type=0
Dn Type=3
Dn Slope=0.005

--- HOG CREEK 1.g01 (geometry) ---

Geom Title=Existing Conditions

River Reach=HOG CREEK 1,Reach-1
Reach XY= 30
      3614749.75     10576555.00      3614979.50     10577060.00
      3615419.50     10577049.00      3615380.50     10577590.00
      3615827.50     10577562.00      3615722.50     10578029.00
      3616193.50     10578287.00      3616155.00     10578671.00
      3616814.25     10579231.00      3617461.25     10579116.00
      3617547.50     10580058.00      3618027.25     10579979.00
      3618427.25     10580502.00      3618457.25     10581290.00
      3618125.75     10581199.00      3617842.50     10581789.00
      3618427.00     10582501.00      3618264.00     10583419.00
      3618678.50     10583573.00      3618281.75     10584052.00
      3618605.00     10584359.00      3618179.25     10584535.00
      3618447.50     10584882.00      3618162.00     10585235.00
      3618660.75     10586508.00      3619614.75     10586966.00
      3622067.25     10585914.00      3622295.25     10586199.00
      3622894.75     10586028.00      3623252.00     10586545.00

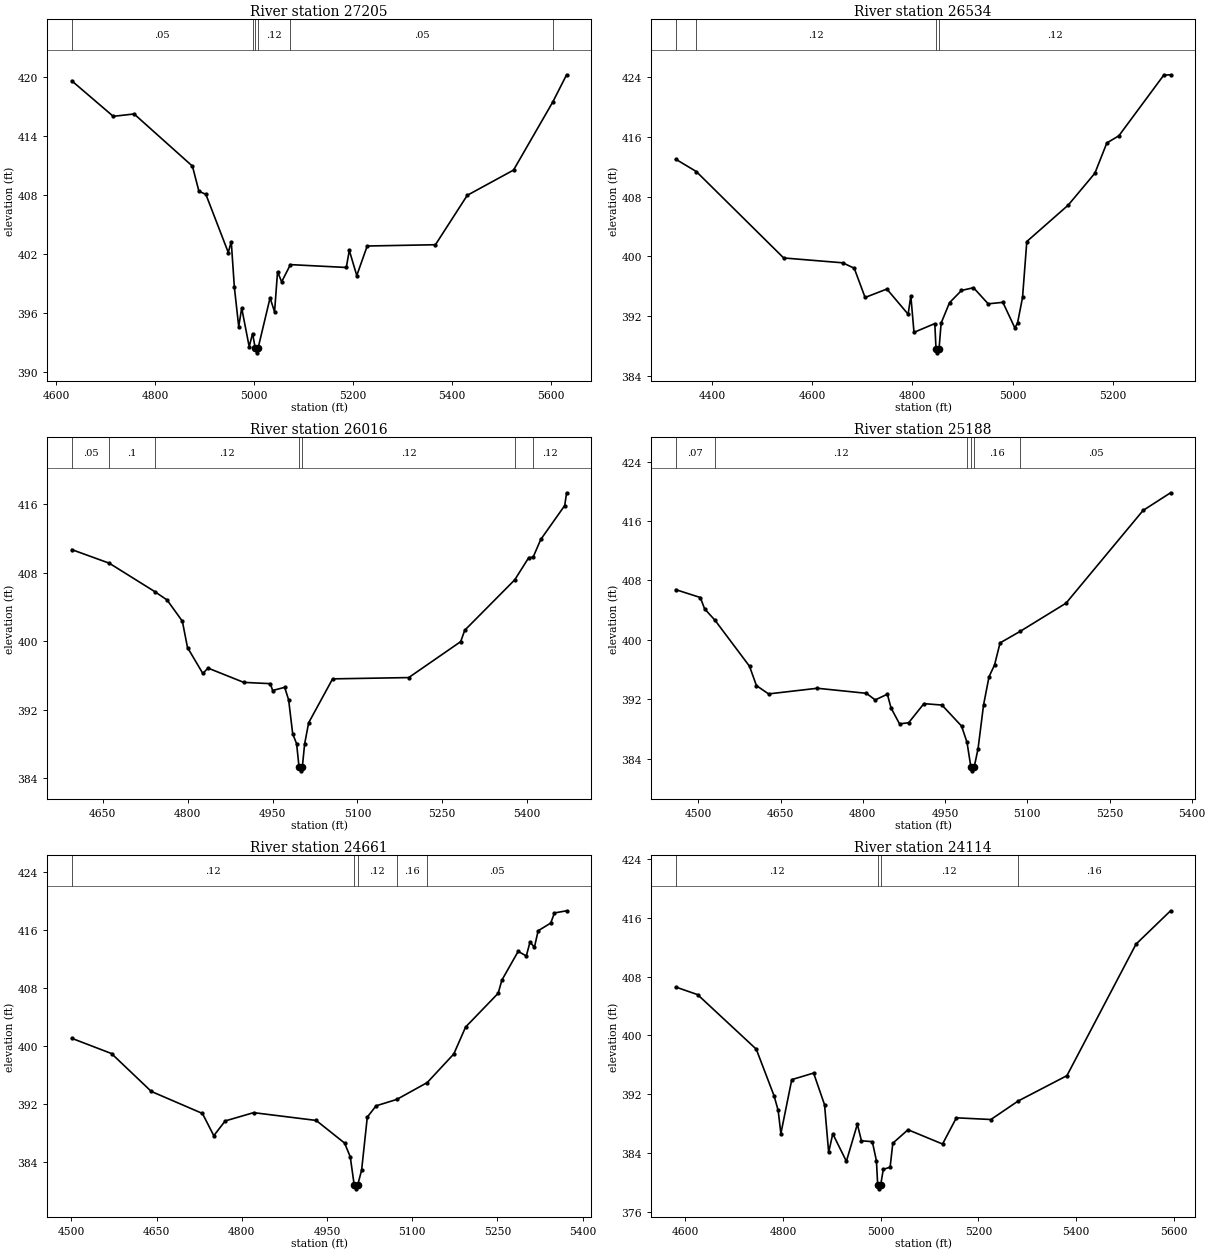
Type RM Length L Ch R = 1,27205,671,671,671
BEGIN DESCRIPTION:
HOG CREEK 1 30.0
END DESCRIPTION:
XS GIS Cut Line= 3
      3614644.48     10577171.08      3615156.64     10576836.88
      3615481.42     10576624.69
#Sta/Elev= 30
  4631.8  419.61  4715.7  416.00  4757.8  416.24  4875.6  410.94  4888.7  408.39
  4902.7  408.08  4948.0  402.17  4954.0  403.28  4960.3  398.63  4969.1  394.64
  4975.1  396.53  4990.2  392.61  4997.1  393.94  5002.3  392.48  5005.1  391.98
  5008.3  392.48  5032.4  397.56  5041.5  396.14  5047.5  400.22  5055.8  399.19
  5073.5  400.94  5186.4  400.65  5192.4  402.39  5207.5  399.83  5228.6  402.83
  5366.4  402.96  5430.7  407.98  5524.1  410.54  5603.2  417.44  5631.3  420.22
#Mann=6,-1,0
  4631.8    0.05       0  4997.1    0.12       0  5002.3    0.07       0
  5008.3    0.12       0  5073.5    0.05       0  5603.2     0.1       0
Bank Sta=5002.3,5008.3
Exp/Cntr=0.3,0.1

Type RM Length L Ch R = 1,26534,518,518,518
BEGIN DESCRIPTION:
HOG CREEK 1 29.0
END DESCRIPTION:
XS GIS Cut Line= 2
      3614800.73     10577314.31      3615712.21     10576936.70
#Sta/Elev= 30
  4327.9  413.02  4369.0  411.37  4543.2  399.80  4661.0  399.15  4683.9  398.42
  4705.5  394.51  4748.9  395.64  4791.3  392.27  4796.7  394.72  4803.0  389.84
  4844.5  391.02  4846.9  387.60  4849.7  387.10  4852.9  387.60  4857.1  391.08
  4873.8  393.81  4897.7  395.45  4921.6  395.82  4950.9  393.66  4980.2  393.86
  5004.1  390.43  5009.5  391.11  5019.4  394.52  5027.9  402.00  5110.4  406.87
  5163.6  411.14  5187.5  415.20  5211.4  416.15  5300.9  424.27  5314.5  424.32
#Mann=4,-1,0
  4327.9    0.05       0  4369.0    0.12       0  4846.9    0.07       0
  4852.9    0.12       0
Bank Sta=4846.9,4852.9
Exp/Cntr=0.3,0.1

Type RM Length L Ch R = 1,26016,828,828,828
BEGIN DESCRIPTION:
HOG CREEK 1 28.0
END DESCRIPTION:
XS GIS Cut Line= 3
      3615139.29     10577791.71      3615330.25     10577500.94
      3615698.28     10577124.25
#Sta/Elev= 30
  4595.2  410.72  4661.5  409.13  4741.9  405.81  4763.7  404.83  4790.7  402.35
  4799.8  399.27  4826.9  396.24  4836.0  396.87  4899.2  395.20  4946.2  395.05
  4950.2  394.25  4971.5  394.62  4978.5  393.16  4985.7  389.18  4992.6  388.03
  4996.8  385.36  4999.6  384.86  5002.8  385.36  5006.8  388.02  5013.9  390.48
  5056.2  395.61  5190.7  395.76  5282.5  399.96  5289.7  401.29  5378.0  407.18
  5402.9  409.79  5410.5  409.83  5424.0  411.90  5466.4  415.87  5469.7  417.36
#Mann=7,-1,0
  4595.2    0.05       0  4661.5     0.1       0  4741.9    0.12       0
  4996.8    0.07       0  5002.8    0.12       0  5378.0    0.16       0
  5410.5    0.12       0
Bank Sta=4996.8,5002.8
Exp/Cntr=0.3,0.1

Type RM Length L Ch R = 1,25188,527,527,527
BEGIN DESCRIPTION:
HOG CREEK 1 27.0
END DESCRIPTION:
XS GIS Cut Line= 3
      3615349.61     10577810.19      3615768.62     10577596.43
      3616199.62     10577560.19
#Sta/Elev= 30
  4458.5  406.77  4503.4  405.71  4511.3  404.18  4530.1  402.66  4593.2  396.46
  4605.8  393.86  4628.0  392.74  4716.9  393.50  4806.5  392.82  4822.5  391.93
  4844.7  392.70  4851.4  390.85  4866.9  388.71  4883.5  388.86  4911.4  391.43
  4944.3  391.24  4980.1  388.41  4990.0  386.23  4997.1  382.89  4999.9  382.39
  5003.1  382.89  5010.2  385.38  5020.2  391.25  5030.2  395.05  5040.3  396.64
  5050.3  399.60  5087.1  401.16  5170.7  404.95  5311.2  417.42  5361.4  419.80
#Mann=6,-1,0
  4458.5    0.07       0  4530.1    0.12       0  4990.0    0.16       0
  4997.1    0.07       0  5003.1    0.16       0  5087.1    0.05       0
Bank Sta=4997.1,5003.1
Exp/Cntr=0.3,0.1

Type RM Length L Ch R = 1,24661,547,547,547
BEGIN DESCRIPTION:
HOG CREEK 1 26.0
END DESCRIPTION:
XS GIS Cut Line= 3
      3615449.59     10577910.19      3615985.63     10577917.61
      3616199.58     10577660.22
#Sta/Elev= 30
  4500.8  401.06  4570.8  398.96  4640.8  393.75  4730.8  390.72  4750.8  387.66
  4770.8  389.69  4820.9  390.83  4930.9  389.76  4980.9  386.65  4990.9  384.76
  4997.9  380.85  5000.6  380.35  5003.9  380.85  5010.9  382.92  5020.9  390.22
  5036.4  391.77  5072.8  392.65  5126.4  394.97  5173.1  398.90  5193.9  402.61
  5251.2  407.25  5257.7  409.06  5286.4  413.02  5300.7  412.38  5307.2  414.30
  5315.0  413.58  5321.5  415.85  5343.7  416.91  5350.2  418.30  5371.6  418.60
#Mann=5,-1,0
  4500.8    0.12       0  4997.9    0.07       0  5003.9    0.12       0
  5072.8    0.16       0  5126.4    0.05       0
Bank Sta=4997.9,5003.9
Exp/Cntr=0.3,0.1

Type RM Length L Ch R = 1,24114,634,634,634
BEGIN DESCRIPTION:
HOG CREEK 1 25.0
END DESCRIPTION:
XS GIS Cut Line= 3
      3615449.58     10578360.20      3615849.61     10578160.19
      3616249.59     10577760.21
#Sta/Elev= 30
  4580.4  406.57  4625.2  405.54  4745.3  398.13  4781.7  391.80  4790.1  389.82
  4795.7  386.66  4818.0  393.99  4862.7  394.88  4885.1  390.57  4893.5  384.10
  4901.9  386.63  4929.8  382.89  4952.2  387.93  4960.6  385.68  4982.9  385.56
  4991.3  382.94  4993.9  379.65  4996.6  379.15  4999.9  379.65  5005.3  381.79
  5019.3  382.10  5024.8  385.35  5055.9  387.18  5126.6  385.24  5154.9  388.80
  5225.6  388.57  5281.3  391.08  5381.2  394.53  5522.6  412.40  5593.3  416.93
#Mann=4,-1,0
  4580.4    0.12       0  4993.9    0.07       0  4999.9    0.12       0
  5281.3    0.16       0
Bank Sta=4993.9,4999.9
Exp/Cntr=0.3,0.1

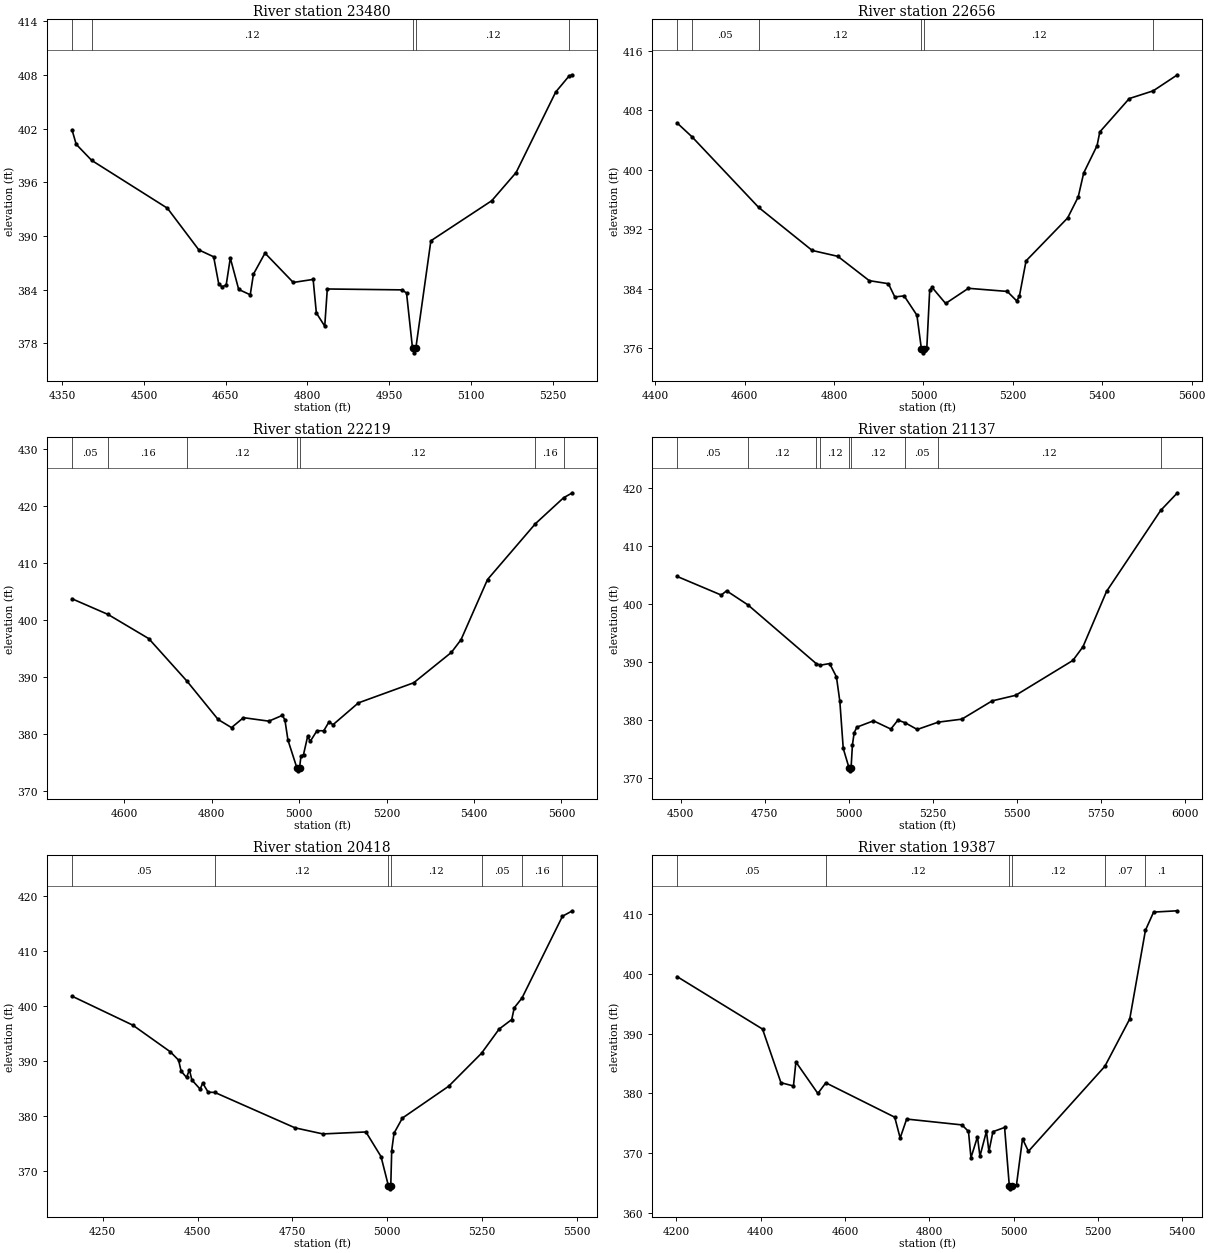
Type RM Length L Ch R = 1,23480,824,824,824
BEGIN DESCRIPTION:
HOG CREEK 1 24.0
END DESCRIPTION:
XS GIS Cut Line= 3
      3615849.59     10578810.22      3616099.61     10578410.19
      3616299.63     10578010.15
#Sta/Elev= 30
  4367.6  401.88  4375.3  400.26  4403.7  398.46  4542.8  393.11  4600.5  388.45
  4627.7  387.68  4637.1  384.63  4643.0  384.33  4650.7  384.51  4658.3  387.54
  4673.7  384.03  4694.9  383.43  4700.8  385.74  4722.0  388.09  4773.9  384.81
  4810.4  385.15  4816.3  381.40  4831.7  379.92  4836.4  384.08  4973.5  383.98
  4981.9  383.63  4992.9  377.44  4995.6  376.94  4998.9  377.44  5026.6  389.47
  5138.4  393.95  5183.1  397.10  5255.8  406.10  5280.6  407.91  5286.6  408.03
#Mann=5,-1,0
  4367.6    0.16       0  4403.7    0.12       0  4992.9    0.07       0
  4998.9    0.12       0  5280.6    0.16       0
Bank Sta=4992.9,4998.9
Exp/Cntr=0.3,0.1

Type RM Length L Ch R = 1,22656,437,437,437
BEGIN DESCRIPTION:
HOG CREEK 1 23.0
END DESCRIPTION:
XS GIS Cut Line= 3
      3615972.58     10579089.52      3616341.53     10578646.78
      3616645.00     10578195.92
#Sta/Elev= 30
  4448.5  406.30  4482.0  404.43  4631.4  394.92  4751.0  389.14  4808.3  388.35
  4878.6  385.08  4921.5  384.67  4935.8  382.89  4956.7  383.03  4985.3  380.43
  4995.4  375.87  4998.1  375.37  5001.4  375.87  5007.4  375.96  5013.9  383.80
  5019.4  384.16  5049.5  382.01  5100.5  384.05  5187.5  383.63  5208.5  382.36
  5214.5  382.96  5229.5  387.74  5322.5  393.51  5346.2  396.34  5358.5  399.57
  5388.4  403.24  5394.5  405.08  5460.4  409.57  5514.0  410.61  5568.3  412.77
#Mann=6,-1,0
  4448.5     0.1       0  4482.0    0.05       0  4631.4    0.12       0
  4995.4    0.07       0  5001.4    0.12       0  5514.0    0.16       0
Bank Sta=4995.4,5001.4
Exp/Cntr=0.3,0.1

Type RM Length L Ch R = 1,22219,1082,1082,1082
BEGIN DESCRIPTION:
HOG CREEK 1 22.0
END DESCRIPTION:
XS GIS Cut Line= 3
      3616250.38     10579211.03      3616623.65     10578603.37
      3616788.36     10578204.60
#Sta/Elev= 30
  4480.7  403.74  4563.0  401.00  4656.3  396.76  4743.5  389.33  4814.9  382.60
  4845.5  381.18  4872.9  382.92  4930.9  382.31  4961.7  383.32  4967.6  382.54
  4974.6  378.99  4995.1  374.11  4997.8  373.61  5001.1  374.11  5004.3  376.15
  5010.2  376.47  5019.7  379.67  5025.6  378.77  5041.0  380.64  5056.4  380.62
  5068.5  382.18  5077.7  381.69  5135.7  385.51  5262.2  389.03  5348.4  394.35
  5370.4  396.57  5431.0  407.11  5540.6  416.89  5605.0  421.43  5625.3  422.30
#Mann=7,-1,0
  4480.7    0.05       0  4563.0    0.16       0  4743.5    0.12       0
  4995.1    0.07       0  5001.1    0.12       0  5540.6    0.16       0
  5605.0    0.12       0
Bank Sta=4995.1,5001.1
Exp/Cntr=0.3,0.1

Type RM Length L Ch R = 1,21137,719,719,719
BEGIN DESCRIPTION:
HOG CREEK 1 21.0
END DESCRIPTION:
XS GIS Cut Line= 4
      3616480.38     10579540.90      3616849.35     10579328.20
      3616897.09     10579024.38      3616931.81     10578269.21
#Sta/Elev= 30
  4489.1  404.75  4620.8  401.53  4636.6  402.26  4700.5  399.82  4903.9  389.69
  4915.7  389.44  4943.3  389.72  4963.6  387.43  4973.7  383.21  4983.8  375.10
  5001.1  371.73  5003.8  371.23  5007.1  371.73  5011.2  375.74  5016.3  377.79
  5024.3  378.76  5073.8  379.85  5125.5  378.43  5146.5  379.97  5167.9  379.52
  5204.0  378.36  5266.3  379.62  5336.8  380.14  5426.9  383.29  5497.0  384.25
  5667.2  390.26  5697.2  392.61  5767.3  402.15  5928.5  416.12  5978.5  419.16
#Mann=9,-1,0
  4489.1    0.05       0  4700.5    0.12       0  4903.9    0.05       0
  4915.7    0.12       0  5001.1    0.07       0  5007.1    0.12       0
  5167.9    0.05       0  5266.3    0.12       0  5928.5    0.16       0
Bank Sta=5001.1,5007.1
Exp/Cntr=0.3,0.1

Type RM Length L Ch R = 1,20418,1031,1031,1031
BEGIN DESCRIPTION:
HOG CREEK 1 20.0
END DESCRIPTION:
XS GIS Cut Line= 3
      3616753.88     10579740.51      3617166.19     10579384.62
      3617500.41     10578685.80
#Sta/Elev= 30
  4168.8  401.78  4329.1  396.50  4427.9  391.65  4449.8  390.13  4456.4  388.13
  4470.7  386.98  4478.3  388.35  4484.9  386.51  4506.6  384.85  4513.4  385.94
  4527.7  384.29  4545.2  384.25  4756.7  377.80  4830.2  376.69  4943.6  377.05
  4983.4  372.57  5003.1  367.19  5005.8  366.69  5009.1  367.19  5011.6  373.67
  5017.7  376.82  5039.8  379.58  5161.8  385.38  5248.3  391.38  5294.8  395.79
  5328.0  397.52  5334.6  399.66  5355.1  401.45  5461.8  416.34  5488.1  417.33
#Mann=7,-1,0
  4168.8    0.05       0  4545.2    0.12       0  5003.1    0.07       0
  5009.1    0.12       0  5248.3    0.05       0  5355.1    0.16       0
  5461.8    0.12       0
Bank Sta=5003.1,5009.1
Exp/Cntr=0.3,0.1

Type RM Length L Ch R = 1,19387,385,385,385
BEGIN DESCRIPTION:
HOG CREEK 1 19.0
END DESCRIPTION:
XS GIS Cut Line= 3
      3616949.63     10579860.17      3617599.61     10579460.19
      3617899.64     10579160.16
#Sta/Elev= 30
  4201.3  399.53  4404.2  390.75  4447.9  381.78  4477.6  381.23  4483.4  385.25
  4535.5  379.98  4554.4  381.76  4717.9  376.01  4730.8  372.53  4746.2  375.70
  4877.5  374.72  4892.9  373.63  4898.8  369.23  4914.2  372.73  4920.1  369.49
  4935.5  373.64  4941.4  370.28  4950.9  373.59  4978.6  374.29  4989.8  364.53
  4992.5  364.03  4995.8  364.53  5006.9  364.73  5021.1  372.39  5035.2  370.31
  5216.5  384.52  5275.6  392.45  5312.8  407.27  5332.2  410.31  5388.8  410.53
#Mann=6,-1,0
  4201.3    0.05       0  4554.4    0.12       0  4989.8    0.07       0
  4995.8    0.12       0  5216.5    0.07       0  5312.8     0.1       0
Bank Sta=4989.8,4995.8
Exp/Cntr=0.3,0.1

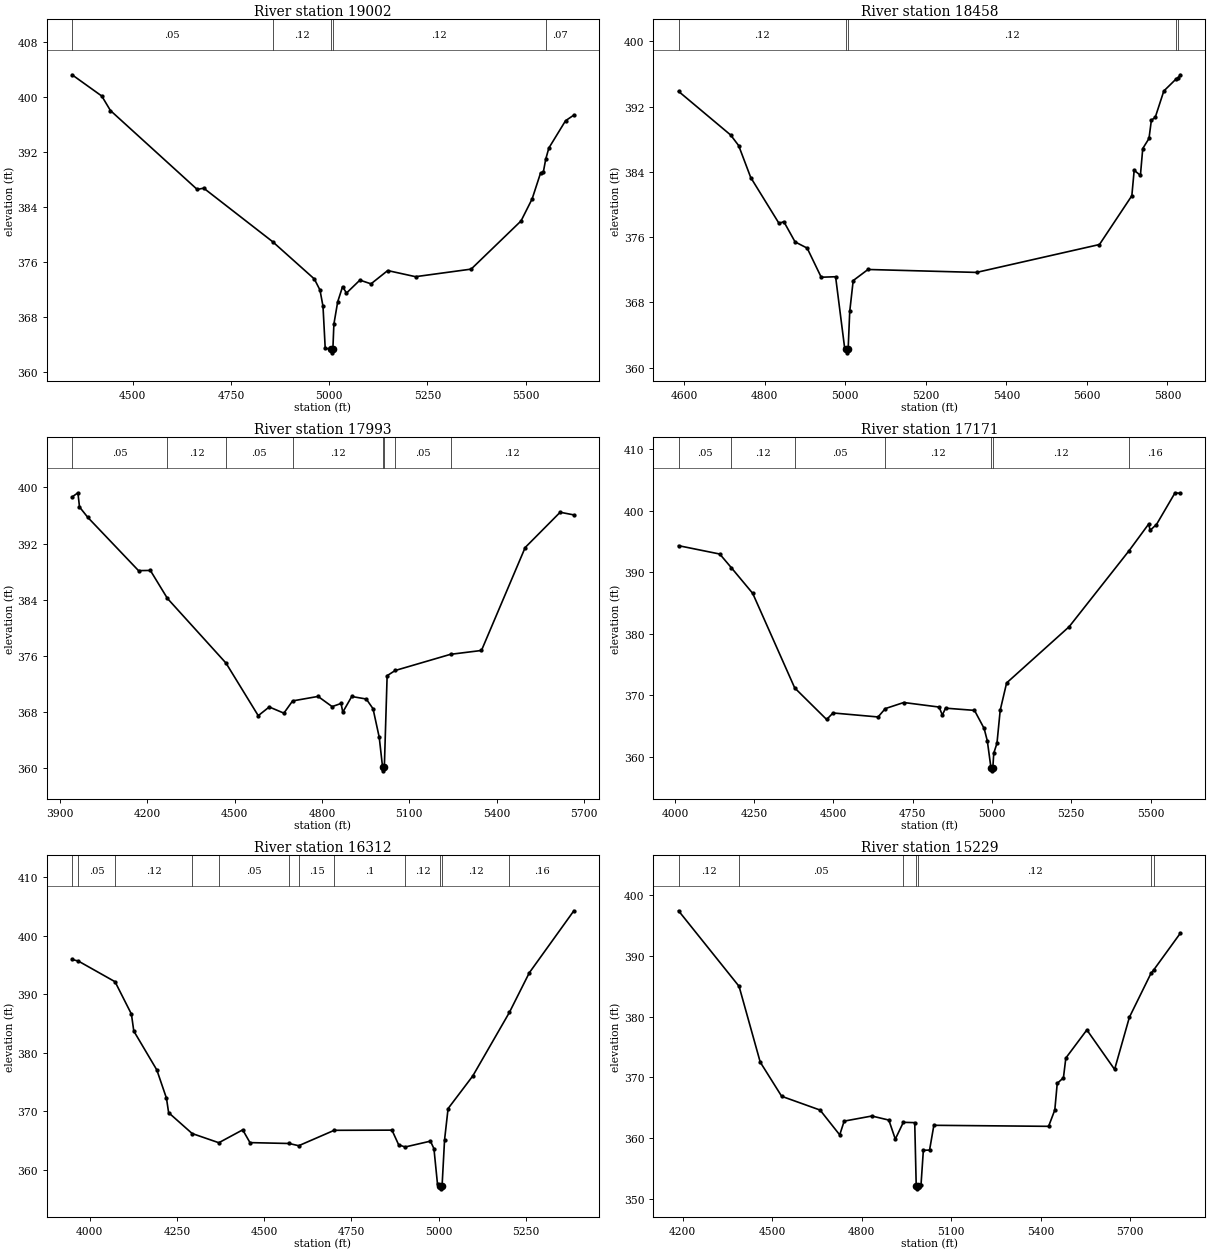
Type RM Length L Ch R = 1,19002,544,544,544
BEGIN DESCRIPTION:
HOG CREEK 1 18.0
END DESCRIPTION:
XS GIS Cut Line= 3
      3617009.91     10580031.34      3617626.25     10579710.14
      3618049.60     10579310.20
#Sta/Elev= 30
  4345.4  403.25  4421.0  400.16  4443.1  398.05  4664.0  386.58  4680.5  386.77
  4855.7  379.00  4962.1  373.57  4976.5  371.96  4984.2  369.59  4989.8  363.52
  5003.3  363.33  5006.0  362.83  5009.3  363.33  5011.9  367.00  5021.6  370.25
  5034.0  372.45  5044.0  371.52  5078.1  373.40  5106.4  372.86  5148.9  374.79
  5219.7  373.90  5361.3  375.00  5488.3  382.00  5516.6  385.21  5538.1  388.98
  5544.9  389.05  5551.1  390.96  5559.1  392.60  5601.6  396.57  5622.8  397.39
#Mann=5,-1,0
  4345.4    0.05       0  4855.7    0.12       0  5003.3    0.07       0
  5009.3    0.12       0  5551.1    0.07       0
Bank Sta=5003.3,5009.3
Exp/Cntr=0.3,0.1

Type RM Length L Ch R = 1,18458,465,465,465
BEGIN DESCRIPTION:
HOG CREEK 1 17.0
END DESCRIPTION:
XS GIS Cut Line= 3
      3617280.36     10580173.02      3617608.30     10580163.08
      3618084.94     10579378.62
#Sta/Elev= 30
  4585.9  393.87  4715.2  388.52  4735.2  387.22  4765.2  383.30  4835.3  377.69
  4847.4  377.89  4875.3  375.41  4905.3  374.65  4940.2  371.08  4975.9  371.14
  4998.3  362.43  5001.1  362.31  5003.9  361.81  5007.1  362.31  5011.0  366.88
  5019.6  370.67  5056.4  372.03  5325.8  371.67  5631.1  375.09  5711.5  381.07
  5717.3  384.19  5732.8  383.57  5738.6  386.86  5754.1  388.09  5760.0  390.33
  5769.6  390.68  5790.9  393.91  5820.7  395.35  5826.1  395.50  5831.9  395.90
#Mann=5,-1,0
  4585.9    0.12       0  5001.1    0.07       0  5007.1    0.12       0
  5820.7    0.07       0  5826.1    0.12       0
Bank Sta=5001.1,5007.1
Exp/Cntr=0.3,0.1

Type RM Length L Ch R = 1,17993,822,822,822
BEGIN DESCRIPTION:
HOG CREEK 1 16.0
END DESCRIPTION:
XS GIS Cut Line= 4
      3617231.25     10580595.58      3617834.59     10580326.46
      3618108.03     10579888.10      3618116.68     10579343.16
#Sta/Elev= 30
  3942.3  398.62  3962.4  399.22  3967.8  397.20  3996.5  395.71  4170.4  388.14
  4211.0  388.17  4269.7  384.18  4470.7  374.98  4581.3  367.50  4619.0  368.74
  4669.3  367.86  4699.3  369.60  4786.6  370.24  4834.9  368.79  4865.6  369.24
  4871.5  368.00  4902.2  370.23  4952.1  369.87  4975.3  368.49  4996.6  364.42
  5008.1  360.15  5010.8  359.65  5014.1  360.15  5023.7  373.19  5051.4  373.93
  5241.2  376.23  5347.5  376.78  5497.5  391.43  5617.6  396.45  5664.6  396.07
#Mann=8,-1,0
  3942.3    0.05       0  4269.7    0.12       0  4470.7    0.05       0
  4699.3    0.12       0  5008.1    0.07       0  5014.1    0.12       0
  5051.4    0.05       0  5241.2    0.12       0
Bank Sta=5008.1,5014.1
Exp/Cntr=0.3,0.1

Type RM Length L Ch R = 1,17171,859,859,859
BEGIN DESCRIPTION:
HOG CREEK 1 15.0
END DESCRIPTION:
XS GIS Cut Line= 3
      3617378.84     10580586.88      3618450.91     10580408.93
      3618932.72     10580291.73
#Sta/Elev= 30
  4011.4  394.29  4141.4  392.93  4177.9  390.71  4245.3  386.54  4377.8  371.16
  4478.5  366.03  4498.7  367.09  4640.7  366.44  4663.5  367.80  4721.8  368.79
  4833.3  368.05  4843.4  366.74  4853.5  367.87  4944.8  367.51  4975.2  364.57
  4985.3  362.55  4996.7  358.18  4999.4  357.68  5002.7  358.18  5005.6  360.55
  5015.7  362.16  5025.9  367.53  5046.1  371.97  5243.5  381.12  5432.3  393.47
  5493.9  397.79  5499.0  396.80  5518.8  397.73  5577.4  402.89  5594.0  402.80
#Mann=7,-1,0
  4011.4    0.05       0  4177.9    0.12       0  4377.8    0.05       0
  4663.5    0.12       0  4996.7    0.07       0  5002.7    0.12       0
  5432.3    0.16       0
Bank Sta=4996.7,5002.7
Exp/Cntr=0.3,0.1

Type RM Length L Ch R = 1,16312,1083,1083,1083
BEGIN DESCRIPTION:
HOG CREEK 1 14.0
END DESCRIPTION:
XS GIS Cut Line= 3
      3617439.58     10580638.95      3618320.70     10580890.70
      3618835.86     10580812.78
#Sta/Elev= 30
  3949.6  395.92  3967.5  395.65  4072.7  392.12  4119.6  386.60  4126.4  383.70
  4192.4  377.06  4220.0  372.24  4226.2  369.77  4293.6  366.21  4370.0  364.64
  4438.4  366.84  4459.2  364.66  4571.3  364.51  4598.8  364.13  4700.5  366.76
  4866.0  366.79  4885.1  364.29  4903.6  363.91  4976.1  364.91  4986.2  363.63
  4996.4  357.55  5003.5  357.27  5006.2  356.77  5009.5  357.27  5016.6  365.12
  5026.7  370.47  5097.5  376.04  5202.2  386.87  5259.3  393.64  5387.0  404.23
#Mann=12,-1,0
  3949.6    0.08       0  3967.5    0.05       0  4072.7    0.12       0
  4293.6    0.08       0  4370.0    0.05       0  4571.3     0.1       0
  4598.8    0.15       0  4700.5     0.1       0  4903.6    0.12       0
  5003.5    0.07       0  5009.5    0.12       0  5202.2    0.16       0
Bank Sta=5003.5,5009.5
Exp/Cntr=0.3,0.1

Type RM Length L Ch R = 1,15229,321,321,321
BEGIN DESCRIPTION:
HOG CREEK 1 13.0
END DESCRIPTION:
XS GIS Cut Line= 3
      3617449.64     10580760.21      3618099.35     10581203.20
      3618799.60     10581760.18
#Sta/Elev= 30
  4186.3  397.46  4389.1  385.01  4460.0  372.52  4531.8  366.89  4660.5  364.62
  4726.3  360.53  4741.2  362.80  4834.0  363.64  4890.9  362.97  4912.5  359.83
  4939.4  362.60  4977.6  362.55  4982.6  352.14  4985.4  351.64  4988.6  352.14
  4998.5  352.20  5006.5  357.99  5027.3  358.03  5041.7  362.11  5426.1  361.94
  5446.9  364.64  5455.0  369.02  5475.8  369.94  5483.8  373.19  5554.3  377.83
  5647.2  371.32  5696.8  379.92  5769.0  387.14  5778.5  387.73  5867.4  393.76
#Mann=7,-1,0
  4186.3    0.12       0  4389.1    0.05       0  4939.4    0.12       0
  4982.6    0.07       0  4988.6    0.12       0  5769.0    0.16       0
  5778.5    0.05       0
Bank Sta=4982.6,4988.6
Exp/Cntr=0.3,0.1

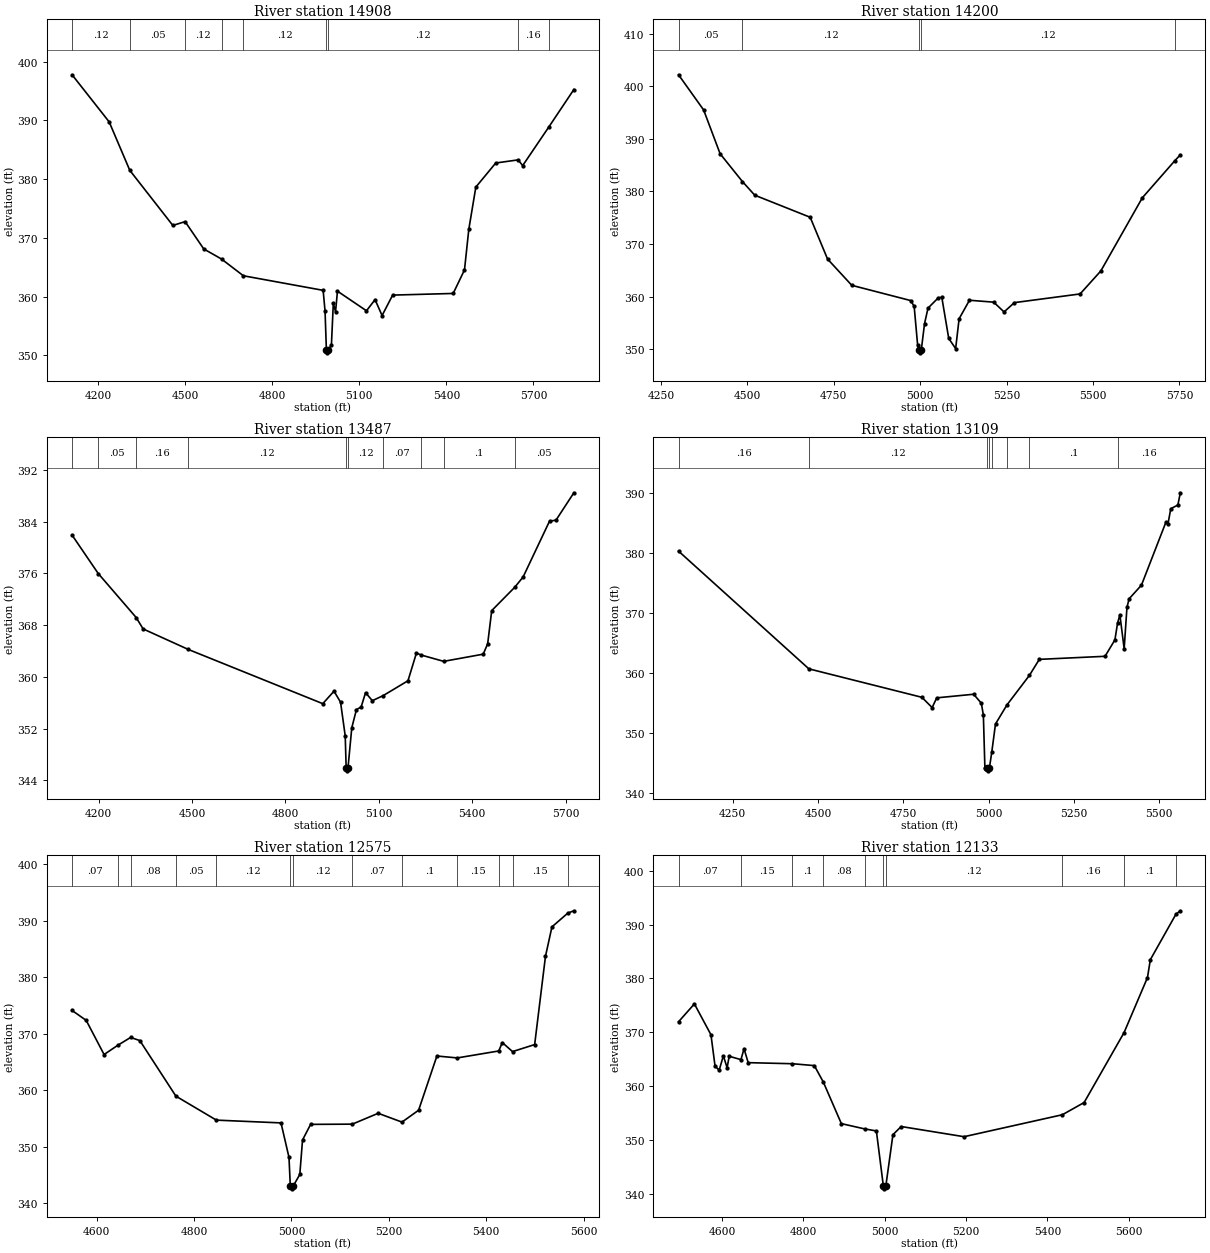
Type RM Length L Ch R = 1,14908,708,708,708
BEGIN DESCRIPTION:
HOG CREEK 1 12.0
END DESCRIPTION:
XS GIS Cut Line= 3
      3617449.58     10580810.15      3618049.61     10581510.19
      3618799.63     10581810.20
#Sta/Elev= 30
  4109.7  397.76  4237.6  389.74  4308.7  381.49  4457.1  372.11  4499.4  372.76
  4563.6  368.11  4624.9  366.39  4700.3  363.54  4975.2  361.06  4981.8  357.53
  4986.4  350.92  4989.2  350.42  4992.4  350.92  5003.7  351.72  5010.3  358.83
  5018.0  357.43  5024.6  360.92  5124.6  357.58  5154.2  359.48  5178.4  356.77
  5214.8  360.25  5423.5  360.53  5462.5  364.54  5477.3  371.43  5501.6  378.64
  5570.2  382.74  5647.3  383.27  5663.1  382.30  5752.2  388.80  5839.5  395.25
#Mann=9,-1,0
  4109.7    0.12       0  4308.7    0.05       0  4499.4    0.12       0
  4624.9    0.05       0  4700.3    0.12       0  4986.4    0.07       0
  4992.4    0.12       0  5647.3    0.16       0  5752.2    0.05       0
Bank Sta=4986.4,4992.4
Exp/Cntr=0.3,0.1

Type RM Length L Ch R = 1,14200,713,713,713
BEGIN DESCRIPTION:
HOG CREEK 1 11.0
END DESCRIPTION:
XS GIS Cut Line= 3
      3617149.65     10581760.19      3617849.61     10581810.19
      3618599.57     10581810.19
#Sta/Elev= 30
  4301.0  402.17  4373.6  395.48  4421.3  387.15  4485.9  381.86  4521.5  379.27
  4681.9  375.07  4732.1  367.13  4802.2  362.13  4972.7  359.23  4982.7  358.12
  4992.7  350.77  4997.2  349.79  5000.0  349.29  5003.2  349.79  5012.7  354.84
  5022.7  357.79  5052.7  359.77  5062.7  359.83  5082.7  352.03  5102.7  350.10
  5112.7  355.77  5142.7  359.29  5212.7  358.93  5242.7  357.07  5272.7  358.84
  5462.7  360.49  5522.7  364.86  5642.7  378.77  5736.8  385.83  5752.7  386.95
#Mann=5,-1,0
  4301.0    0.05       0  4485.9    0.12       0  4997.2    0.07       0
  5003.2    0.12       0  5736.8    0.05       0
Bank Sta=4997.2,5003.2
Exp/Cntr=0.3,0.1

Type RM Length L Ch R = 1,13487,378,378,378
BEGIN DESCRIPTION:
HOG CREEK 1 10.0
END DESCRIPTION:
XS GIS Cut Line= 3
      3617324.57     10582801.53      3618164.45     10582243.06
      3618636.04     10581866.65
#Sta/Elev= 30
  4114.5  381.90  4198.6  375.96  4320.5  369.16  4342.7  367.40  4487.9  364.23
  4919.9  355.85  4956.0  357.78  4977.0  356.08  4992.0  350.87  4995.0  345.97
  4997.8  345.47  5001.0  345.97  5013.1  352.13  5028.1  354.94  5043.1  355.33
  5057.3  357.55  5079.2  356.31  5114.5  357.11  5193.6  359.39  5220.8  363.68
  5236.4  363.36  5308.4  362.39  5435.3  363.50  5449.6  365.10  5462.6  370.23
  5536.2  373.82  5563.4  375.42  5648.3  384.05  5669.1  384.21  5726.5  388.44
#Mann=10,-1,0
  4114.5     0.1       0  4198.6    0.05       0  4320.5    0.16       0
  4487.9    0.12       0  4995.0    0.07       0  5001.0    0.12       0
  5114.5    0.07       0  5236.4    0.08       0  5308.4     0.1       0
  5536.2    0.05       0
Bank Sta=4995,5001
Exp/Cntr=0.3,0.1

Type RM Length L Ch R = 1,13109,534,534,534
BEGIN DESCRIPTION:
HOG CREEK 1 9.0
END DESCRIPTION:
XS GIS Cut Line= 3
      3617549.58     10582910.21      3618299.61     10582410.19
      3618749.60     10582060.20
#Sta/Elev= 30
  4091.0  380.26  4473.2  360.65  4804.6  355.91  4834.7  354.20  4848.2  355.82
  4956.4  356.42  4978.9  354.93  4984.9  352.97  4989.4  344.17  4996.7  344.16
  4999.4  343.66  5002.7  344.16  5009.5  346.75  5020.5  351.47  5054.2  354.65
  5119.8  359.55  5149.0  362.23  5341.7  362.74  5370.7  365.48  5378.3  368.22
  5385.2  369.67  5397.8  364.00  5406.0  370.89  5412.3  372.32  5448.5  374.59
  5520.0  385.05  5526.3  384.80  5534.5  387.33  5555.3  387.94  5562.5  389.98
#Mann=8,-1,0
  4091.0    0.16       0  4473.2    0.12       0  4996.7    0.07       0
  5002.7    0.12       0  5009.5    0.07       0  5054.2    0.12       0
  5119.8     0.1       0  5378.3    0.16       0
Bank Sta=4996.7,5002.7
Exp/Cntr=0.3,0.1

Type RM Length L Ch R = 1,12575,442,442,442
BEGIN DESCRIPTION:
HOG CREEK 1 8.0
END DESCRIPTION:
XS GIS Cut Line= 3
      3617899.64     10583010.17      3618268.31     10582783.54
      3618799.65     10582510.17
#Sta/Elev= 30
  4549.5  374.10  4578.5  372.35  4615.2  366.31  4643.8  367.97  4669.7  369.33
  4688.6  368.78  4762.7  358.95  4845.8  354.71  4978.5  354.22  4994.9  348.12
  4997.6  343.06  5000.3  342.56  5003.6  343.06  5017.1  345.10  5022.7  351.20
  5039.3  353.96  5125.0  354.00  5178.0  355.92  5226.9  354.36  5261.0  356.46
  5298.6  366.05  5340.4  365.71  5425.6  366.94  5432.8  368.43  5453.9  366.83
  5499.3  368.07  5521.5  383.67  5534.8  388.88  5567.4  391.32  5579.8  391.73
#Mann=13,-1,0
  4549.5    0.07       0  4643.8     0.1       0  4669.7    0.08       0
  4762.7    0.05       0  4845.8    0.12       0  4997.6    0.07       0
  5003.6    0.12       0  5125.0    0.07       0  5226.9     0.1       0
  5340.4    0.15       0  5425.6     0.1       0  5453.9    0.15       0
  5567.4    0.16       0
Bank Sta=4997.6,5003.6
Exp/Cntr=0.3,0.1

Type RM Length L Ch R = 1,12133,490,490,490
BEGIN DESCRIPTION:
HOG CREEK 1 7.0
END DESCRIPTION:
XS GIS Cut Line= 3
      3617821.27     10583187.50      3618506.99     10583061.64
      3618888.32     10582684.65
#Sta/Elev= 30
  4493.4  371.95  4532.4  375.27  4573.1  369.54  4583.2  363.69  4593.4  362.98
  4603.6  365.63  4612.8  363.42  4617.9  365.55  4646.8  364.92  4654.4  366.95
  4664.6  364.36  4773.5  364.16  4827.2  363.81  4849.4  360.74  4893.6  353.04
  4950.7  352.06  4979.7  351.68  4996.9  341.43  4999.6  340.93  5002.9  341.43
  5020.4  350.99  5040.7  352.50  5195.2  350.61  5436.9  354.69  5490.4  356.96
  5588.5  369.94  5646.0  380.15  5653.1  383.48  5716.0  391.92  5726.8  392.56
#Mann=10,-1,0
  4493.4    0.07       0  4646.8    0.15       0  4773.5     0.1       0
  4849.4    0.08       0  4950.7    0.12       0  4996.9    0.07       0
  5002.9    0.12       0  5436.9    0.16       0  5588.5     0.1       0
  5716.0    0.16       0
Bank Sta=4996.9,5002.9
Exp/Cntr=0.3,0.1

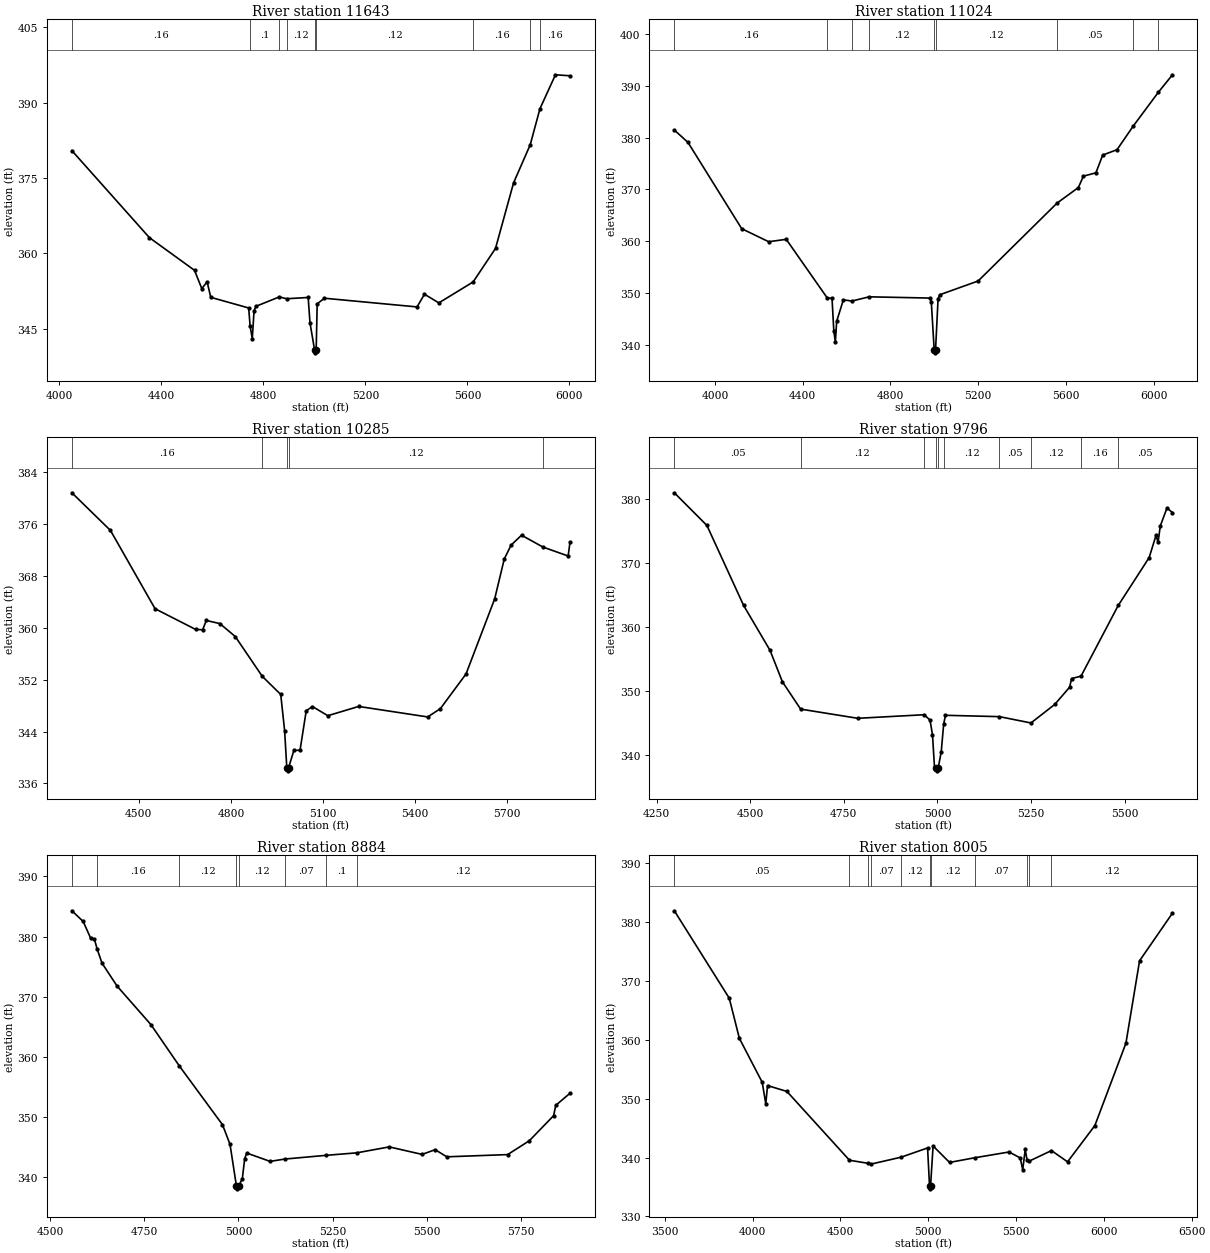
Type RM Length L Ch R = 1,11643,619,619,619
BEGIN DESCRIPTION:
HOG CREEK 1 6.0
END DESCRIPTION:
XS GIS Cut Line= 3
      3617649.64     10584110.16      3618392.31     10583391.78
      3618949.58     10582660.22
#Sta/Elev= 30
  4049.4  380.44  4353.5  363.11  4530.3  356.61  4558.6  352.98  4579.7  354.31
  4593.8  351.24  4742.5  349.12  4748.1  345.52  4756.6  343.02  4763.6  348.51
  4770.8  349.45  4862.5  351.32  4891.1  350.96  4975.8  351.21  4982.8  346.19
  5001.1  340.69  5003.9  340.19  5007.1  340.69  5011.1  349.94  5039.4  351.06
  5402.6  349.33  5431.7  351.86  5487.9  350.13  5622.4  354.30  5710.2  360.98
  5781.0  374.03  5846.2  381.60  5884.5  388.80  5945.2  395.54  6002.3  395.34
#Mann=9,-1,0
  4049.4    0.16       0  4748.1     0.1       0  4862.5    0.16       0
  4891.1    0.12       0  5001.1    0.07       0  5007.1    0.12       0
  5622.4    0.16       0  5846.2     0.1       0  5884.5    0.16       0
Bank Sta=5001.1,5007.1
Exp/Cntr=0.3,0.1

Type RM Length L Ch R = 1,11024,739,739,739
BEGIN DESCRIPTION:
HOG CREEK 1 5.0
END DESCRIPTION:
XS GIS Cut Line= 3
      3617657.16     10584161.61      3618430.63     10583666.80
      3619615.18     10583012.59
#Sta/Elev= 30
  3815.0  381.45  3877.0  379.08  4122.2  362.40  4245.3  359.88  4325.2  360.35
  4512.1  349.03  4534.1  348.95  4542.1  342.70  4549.3  340.53  4555.2  344.50
  4585.7  348.66  4624.4  348.42  4703.1  349.24  4981.2  349.00  4986.9  348.15
  5000.0  338.92  5002.7  338.42  5006.0  338.92  5017.6  348.83  5024.7  349.63
  5200.4  352.30  5560.6  367.36  5657.4  370.35  5680.2  372.55  5737.3  373.19
  5768.3  376.62  5833.6  377.66  5907.0  382.19  6022.5  388.78  6086.4  392.13
#Mann=9,-1,0
  3815.0    0.16       0  4512.1    0.12       0  4624.4     0.1       0
  4703.1    0.12       0  5000.0    0.07       0  5006.0    0.12       0
  5560.6    0.05       0  5907.0    0.16       0  6022.5    0.12       0
Bank Sta=5000,5006
Exp/Cntr=0.3,0.1

Type RM Length L Ch R = 1,10285,489,489,489
BEGIN DESCRIPTION:
HOG CREEK 1 4.0
END DESCRIPTION:
XS GIS Cut Line= 4
      3617680.47     10584190.42      3618088.49     10583956.02
      3618661.41     10584008.10      3619215.76     10583852.19
#Sta/Elev= 30
  4282.4  380.86  4407.9  375.05  4553.2  362.96  4685.1  359.77  4708.1  359.71
  4720.0  361.15  4764.1  360.67  4814.3  358.67  4902.3  352.52  4962.3  349.73
  4975.0  344.13  4982.0  338.44  4984.8  337.94  4988.0  338.44  5005.1  341.09
  5025.2  341.13  5045.3  347.21  5065.4  347.87  5115.6  346.45  5216.0  347.88
  5440.6  346.26  5481.9  347.53  5565.6  352.90  5658.8  364.48  5690.0  370.63
  5712.1  372.77  5746.2  374.31  5816.1  372.48  5898.0  371.10  5904.1  373.26
#Mann=5,-1,0
  4282.4    0.16       0  4902.3    0.12       0  4982.0    0.07       0
  4988.0    0.12       0  5816.1    0.05       0
Bank Sta=4982,4988
Exp/Cntr=0.3,0.1

Type RM Length L Ch R = 1,9796,912,912,912
BEGIN DESCRIPTION:
HOG CREEK 1 3.0
END DESCRIPTION:
XS GIS Cut Line= 3
      3617899.63     10584460.18      3618549.61     10584260.19
      3619149.65     10584010.17
#Sta/Elev= 30
  4297.3  381.05  4384.3  375.93  4482.3  363.40  4553.0  356.35  4585.7  351.46
  4634.5  347.16  4787.1  345.72  4964.6  346.28  4980.1  345.43  4986.6  343.14
  4992.0  338.02  4996.0  337.99  4998.8  337.49  5002.0  337.99  5009.9  340.43
  5016.5  344.81  5021.2  346.19  5165.4  345.98  5249.6  344.99  5313.2  347.90
  5352.7  350.59  5358.1  351.94  5383.3  352.33  5482.7  363.41  5565.1  370.89
  5583.5  374.38  5588.9  373.27  5594.9  375.85  5612.7  378.66  5627.4  377.95
#Mann=10,-1,0
  4297.3    0.05       0  4634.5    0.12       0  4964.6    0.05       0
  4996.0    0.04       0  5002.0    0.05       0  5016.5    0.12       0
  5165.4    0.05       0  5249.6    0.12       0  5383.3    0.16       0
  5482.7    0.05       0
Bank Sta=4996,5002
Exp/Cntr=0.3,0.1

Type RM Length L Ch R = 1,8884,879,879,879
BEGIN DESCRIPTION:
HOG CREEK 1 2.0
END DESCRIPTION:
XS GIS Cut Line= 3
      3617849.60     10584760.19      3618299.61     10584760.19
      3619099.59     10584410.20
#Sta/Elev= 30
  4557.5  384.29  4587.5  382.51  4607.5  379.71  4617.5  379.54  4624.5  377.93
  4637.5  375.58  4677.5  371.76  4767.5  365.34  4843.3  358.43  4957.5  348.69
  4977.5  345.43  4994.5  338.51  4997.3  338.01  5000.5  338.51  5010.2  339.67
  5016.5  343.03  5021.9  343.97  5083.9  342.58  5123.6  342.97  5233.4  343.59
  5314.1  344.00  5400.5  344.99  5487.8  343.74  5522.5  344.53  5553.3  343.34
  5715.0  343.71  5772.7  346.02  5837.1  350.19  5842.9  351.91  5880.7  353.92
#Mann=8,-1,0
  4557.5    0.12       0  4624.5    0.16       0  4843.3    0.12       0
  4994.5    0.07       0  5000.5    0.12       0  5123.6    0.07       0
  5233.4     0.1       0  5314.1    0.12       0
Bank Sta=4994.5,5000.5
Exp/Cntr=0.3,0.1

Type RM Length L Ch R = 1,8005,1298,1298,1298
BEGIN DESCRIPTION:
Mapping XS ac33b423
END DESCRIPTION:
XS GIS Cut Line= 4
      3616890.62     10585379.64      3617836.76     10585457.76
      3618574.61     10585240.74      3619399.28     10584485.51
#Sta/Elev= 30
  3554.0  381.86  3866.8  367.03  3924.2  360.23  4054.7  352.75  4074.8  349.10
  4084.8  352.21  4195.2  351.21  4551.4  339.54  4655.7  339.03  4676.2  338.90
  4846.8  340.07  4996.2  341.63  5007.2  335.19  5010.0  334.69  5013.2  335.19
  5027.5  341.96  5121.3  339.17  5264.2  339.96  5460.3  340.94  5523.8  339.93
  5538.0  337.91  5552.2  341.37  5562.6  339.59  5572.6  339.36  5701.7  341.18
  5793.3  339.27  5948.7  345.42  6125.7  359.40  6203.4  373.38  6390.7  381.46
#Mann=11,-1,0
  3554.0    0.05       0  4551.4    0.07       0  4655.7     0.1       0
  4676.2    0.07       0  4846.8    0.12       0  5007.2    0.07       0
  5013.2    0.12       0  5264.2    0.07       0  5562.6    0.08       0
  5572.6    0.07       0  5701.7    0.12       0
Bank Sta=5007.2,5013.2
Exp/Cntr=0.3,0.1

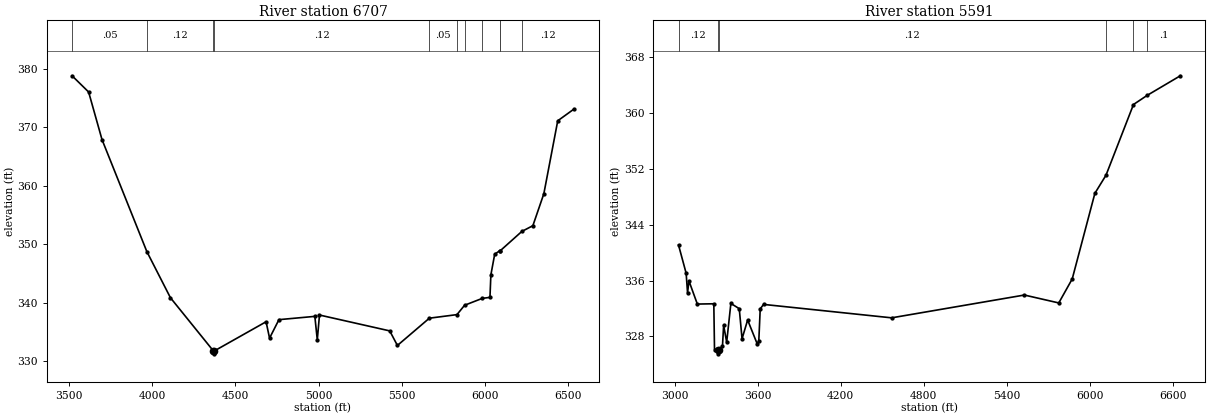
Type RM Length L Ch R = 1,6707,1116,1116,1116
BEGIN DESCRIPTION:
Mapping XS ced851cb
END DESCRIPTION:
XS GIS Cut Line= 4
      3617220.46     10586429.98      3618201.34     10586334.49
      3618852.38     10585865.74      3619364.53     10584745.96
#Sta/Elev= 30
  3517.3  378.77  3616.9  376.00  3697.3  367.88  3967.0  348.75  4109.2  340.85
  4367.5  331.77  4370.2  331.27  4373.5  331.77  4684.6  336.75  4705.5  333.95
  4762.0  337.11  4978.0  337.67  4992.7  333.65  5005.9  337.90  5428.6  335.19
  5474.7  332.70  5667.0  337.36  5833.1  337.97  5879.0  339.57  5984.9  340.74
  6031.6  340.92  6037.1  344.76  6060.1  348.29  6090.9  348.89  6093.1  348.87
  6223.4  352.18  6289.8  353.16  6355.8  358.62  6439.4  371.08  6536.4  373.07
#Mann=11,-1,0
  3517.3    0.05       0  3967.0    0.12       0  4367.5    0.07       0
  4373.5    0.12       0  5667.0    0.05       0  5833.1    0.08       0
  5879.0     0.1       0  5984.9    0.15       0  6090.9     0.1       0
  6093.1    0.05       0  6223.4    0.12       0
Bank Sta=4367.5,4373.5
Exp/Cntr=0.3,0.1

Type RM Length L Ch R = 1,5591,0,0,0
BEGIN DESCRIPTION:
HOG CREEK 1 1.0
END DESCRIPTION:
XS GIS Cut Line= 4
      3617585.06     10587028.94      3618930.51     10587219.91
      3619251.69     10586204.28      3619485.92     10585024.45
#Sta/Elev= 30
  3028.9  341.08  3084.0  337.04  3094.1  334.22  3104.2  335.95  3164.8  332.64
  3283.9  332.68  3288.9  326.14  3313.3  326.02  3316.1  325.52  3319.3  326.02
  3346.6  326.65  3354.8  329.61  3376.9  327.18  3407.2  332.73  3467.8  331.98
  3488.0  327.68  3528.4  330.36  3599.1  326.87  3609.2  327.42  3619.3  331.95
  3643.6  332.59  4569.2  330.67  5528.6  333.93  5777.3  332.80  5874.5  336.23
  6038.3  348.48  6118.7  351.07  6317.2  361.18  6416.4  362.49  6655.9  365.29
#Mann=6,-1,0
  3028.9    0.12       0  3313.3    0.07       0  3319.3    0.12       0
  6118.7    0.05       0  6317.2    0.08       0  6416.4     0.1       0
Bank Sta=3313.3,3319.3
Exp/Cntr=0.3,0.1

Chan Stop Cuts=-1