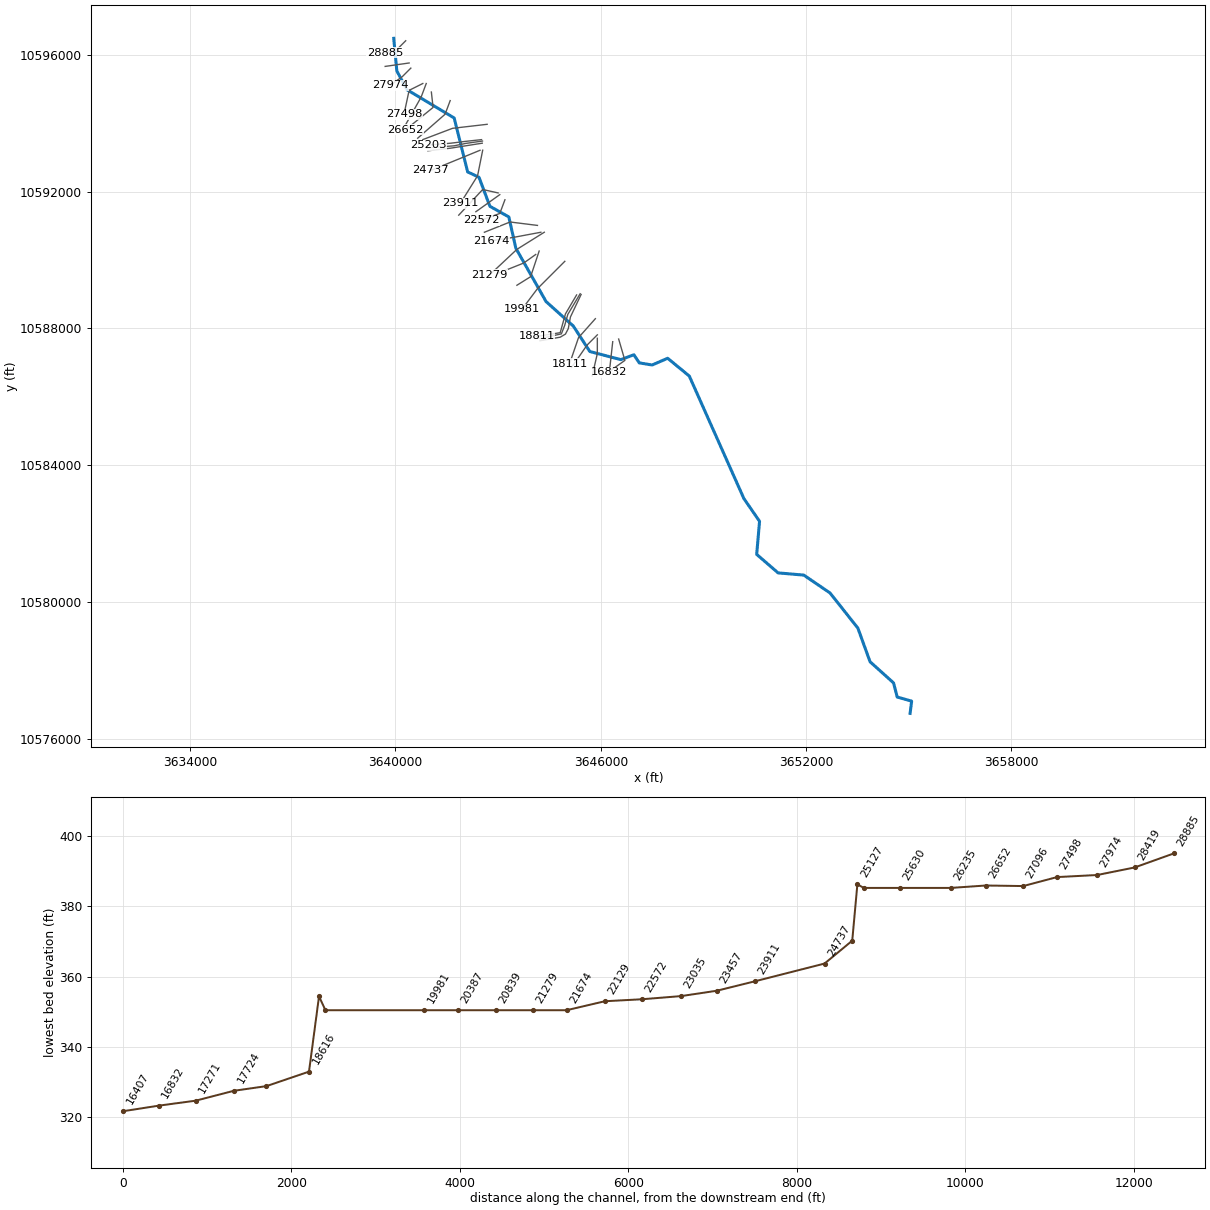
--- HOLLY BRANCH.prj (project) ---

Proj Title=HOLLY BRANCH Base Level Engineering
Current Plan=p01
Default Exp/Contr=0.3,0.1
English Units
Geom File=g01
Flow File=f01
Plan File=p01
Y Axis Title=Elevation
X Axis Title(PF)=Main Channel Distance
X Axis Title(XS)=Station
BEGIN DESCRIPTION:
HOLLY BRANCH
END DESCRIPTION:
DSS Export Rating Curves= 0
DSS Export Rating Curve Sorted= 0
DSS Export Volume Flow Curves= 0
DXF OffsetX= 0
DXF OffsetY= 0
DXF ScaleX= 1
DXF ScaleY= 10

--- HOLLY BRANCH.p01 (plan) ---

Plan Title=Multiple Run
Short Identifier=Multiple
Geom File=g01
Flow File=f01
Subcritical Flow
K Sum by GR= 0
Std Step Tol= 0.01
Critical Tol= 0.01
Num of Std Step Trials= 20
Max Error Tol= 0.3
Flow Tol Ratio= 0.001
Split Flow NTrial= 30
Split Flow Tol= 0.02
Split Flow Ratio= 0.02
Log Output Level= 0
Friction Slope Method= 1
Unsteady Friction Slope Method= 2
Unsteady Bridges Friction Slope Method= 1
Parabolic Critical Depth
Global Vel Dist=  1 , 1 , 1
Global Log Level= 0
CheckData=True
Encroach Param= -1, 0, 0, 0
BEGIN DESCRIPTION:
Multiple Run
END DESCRIPTION:

--- HOLLY BRANCH.f01 (steady flow) ---

Flow Title=Multiple
Number of Profiles=7
Profile Names=10-year,25-year,50-year,1pct_min,100-year,1pct_plu,500-year
River Rch & RM= HOLLY BRANCH,Reach-1,28885
    1213    1684    2079    1873    2533    3426    3748
River Rch & RM= HOLLY BRANCH,Reach-1,25630
    1888    2688    3372    3084    4170    5640    6359
River Rch & RM= HOLLY BRANCH,Reach-1,22572
    2159    3092    3896    3577    4838    6542    7446
River Rch & RM= HOLLY BRANCH,Reach-1,17724
    2279    3272    4129    3798    5137    6947    7943
River Rch & RM= HOLLY BRANCH,Reach-1,14694
    2348    3375    4263    3929    5313    7185    8263
River Rch & RM= HOLLY BRANCH,Reach-1,8787
    2503    3599    4548    4194    5672    7671    8844
Boundary for River Rch & Prof#=HOLLY BRANCH,Reach-1,1
Up Type=0
Dn Type=3
Dn Slope=0.005
Boundary for River Rch & Prof#=HOLLY BRANCH,Reach-1,2
Up Type=0
Dn Type=3
Dn Slope=0.005
Boundary for River Rch & Prof#=HOLLY BRANCH,Reach-1,3
Up Type=0
Dn Type=3
Dn Slope=0.005
Boundary for River Rch & Prof#=HOLLY BRANCH,Reach-1,4
Up Type=0
Dn Type=3
Dn Slope=0.005
Boundary for River Rch & Prof#=HOLLY BRANCH,Reach-1,5
Up Type=0
Dn Type=3
Dn Slope=0.005
Boundary for River Rch & Prof#=HOLLY BRANCH,Reach-1,6
Up Type=0
Dn Type=3
Dn Slope=0.005
Boundary for River Rch & Prof#=HOLLY BRANCH,Reach-1,7
Up Type=0
Dn Type=3
Dn Slope=0.005

--- HOLLY BRANCH.g01 (geometry) ---

Geom Title=Existing Conditions
Program Version=4.10

River Reach=HOLLY BRANCH    ,Reach-1
Reach XY= 30
       3639949.5       10596481.      3640040.25       10595529.
      3640331.75       10594981.      3641715.75       10594152.
      3642109.75       10592575.       3642441.5       10592417.
      3642759.75       10591569.      3643313.25       10591258.
        3643518.       10590343.        3644402.       10588782.
       3645197.5       10588068.      3645680.25       10587322.
      3646586.75       10587085.       3646967.5       10587227.
      3647125.75       10586990.      3647500.75       10586928.
      3647955.25       10587125.        3648587.       10586605.
        3650183.       10583021.       3650640.5       10582357.
       3650556.5       10581390.      3651182.75       10580848.
      3651932.75       10580784.      3652699.75       10580261.
      3653514.25       10579233.      3653869.75       10578250.
        3654556.       10577631.      3654663.25       10577218.
       3655085.5       10577098.      3655039.75       10576740.

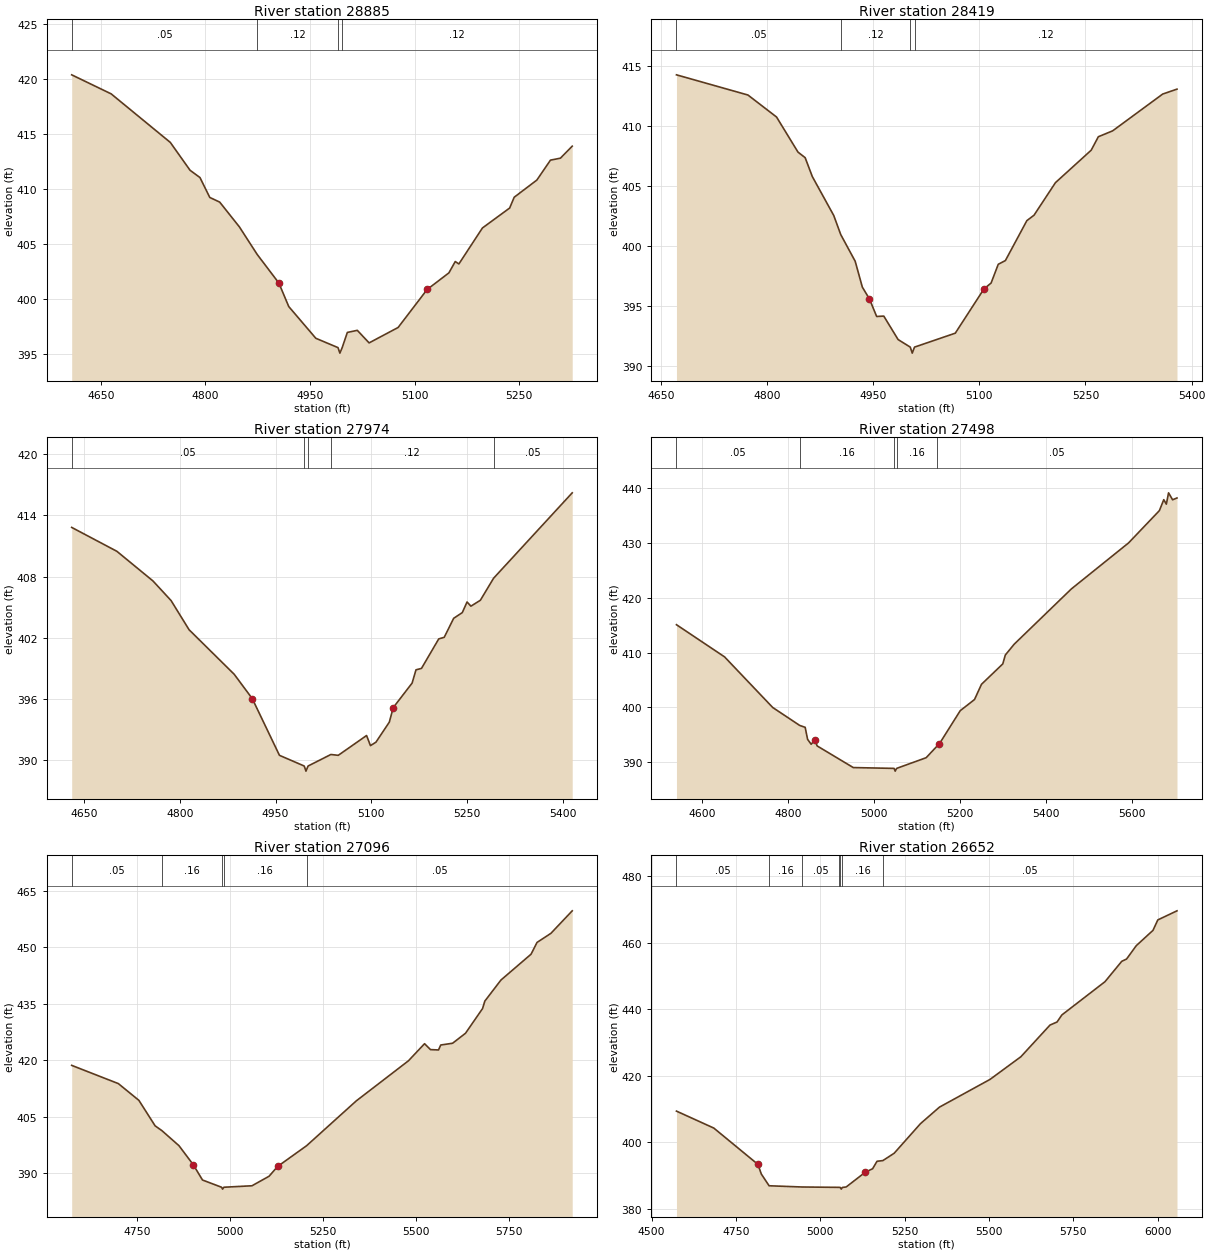
Type RM Length L Ch R = 1 ,28885   ,466,466,466
BEGIN DESCRIPTION:
HOLLY BRANCH 46.0
END DESCRIPTION:
XS GIS Cut Line= 3
      3640299.63     10596410.21      3640049.61     10596160.19
      3639699.59     10596060.18
#Sta/Elev= 30
  4608.4  420.38    4665  418.65  4749.8  414.24  4778.1  411.71  4792.3  411.05
  4806.4  409.24  4820.6  408.82  4848.8  406.57  4874.4  404.06  4905.4  401.47
  4919.6  399.33  4958.4  396.45  4990.2   395.6  4992.9   395.1  4996.2   395.6
  5003.6  396.98  5017.9  397.17  5034.8  396.03  5076.4  397.43    5118  400.88
  5149.2  402.39  5158.3  403.42  5163.5   403.2  5197.3  406.47  5236.3  408.28
  5242.8  409.26  5275.3  410.82  5294.8  412.63  5309.1  412.81    5326   413.9
#Mann= 4 ,-1 , 0
  4608.4     .05       0  4874.4     .12       0  4990.2     .07       0
  4996.2     .12       0
Bank Sta=4905.4,5118
XS Rating Curve= 0 ,0
Exp/Cntr=0.3,0.1

Type RM Length L Ch R = 1 ,28419   ,445,445,445
BEGIN DESCRIPTION:
HOLLY BRANCH 45.0
END DESCRIPTION:
XS GIS Cut Line= 3
      3640399.59     10595760.19      3640049.61     10595710.19
       3639699.6     10595660.19
#Sta/Elev= 30
  4672.2  414.24  4773.2  412.56  4813.6  410.73  4843.9  407.81    4854  407.35
  4864.1  405.78  4894.4  402.54  4904.3  400.95  4924.7  398.73  4934.8  396.58
  4944.9  395.59    4955  394.14  4965.1  394.17  4985.3  392.22  5002.5  391.59
  5005.3  391.09  5008.5  391.59  5066.1  392.75  5106.6  396.43  5116.7  396.92
  5126.8  398.48  5136.9  398.79  5167.2  402.11  5177.3  402.56  5207.6  405.27
  5258.1  407.97  5268.2  409.09  5288.4  409.58  5359.1  412.64  5379.3  413.05
#Mann= 4 ,-1 , 0
  4672.2     .05       0  4904.3     .12       0  5002.5     .07       0
  5008.5     .12       0
Bank Sta=4944.9,5106.6
XS Rating Curve= 0 ,0
Exp/Cntr=0.3,0.1

Type RM Length L Ch R = 1 ,27974   ,476,476,476
BEGIN DESCRIPTION:
HOLLY BRANCH 44.0
END DESCRIPTION:
XS GIS Cut Line= 3
       3640449.6     10595610.18      3640199.61     10595360.19
      3639849.57     10595110.16
#Sta/Elev= 30
  4630.7  412.83  4701.4  410.49    4758  407.58  4786.3  405.66  4814.5   402.8
  4885.2  398.43  4913.5  396.04    4956  390.49  4994.8  389.44  4997.5  388.94
  5000.8  389.44  5036.5  390.57  5048.1  390.49  5092.4  392.43  5098.5  391.44
  5107.1  391.78    5128  393.74  5134.2  395.17  5163.7  397.57  5169.8  398.87
  5178.4  399.01  5205.4   401.9    5214  402.06  5228.8  403.92  5242.3  404.48
  5249.7  405.52  5255.8  405.11  5270.6  405.69  5291.3  407.85  5414.4  416.22
#Mann= 5 ,-1 , 0
  4630.7     .05       0  4994.8     .03       0  5000.8     .05       0
  5036.5     .12       0  5291.3     .05       0
Bank Sta=4913.5,5134.2
XS Rating Curve= 0 ,0
Exp/Cntr=0.3,0.1

Type RM Length L Ch R = 1 ,27498   ,402,402,402
BEGIN DESCRIPTION:
HOLLY BRANCH 43.0
END DESCRIPTION:
XS GIS Cut Line= 3
       3640799.6     10595160.18      3640399.61     10594960.19
      3640249.61     10594260.18
#Sta/Elev= 30
  4541.3   415.1  4653.1  409.22  4764.9  399.98  4827.6   396.7  4840.4  396.35
    4846  394.16  4854.3  393.26  4862.7  394.03  4868.3  392.95  4952.2     389
  5046.9  388.85  5049.6  388.35  5052.9  388.85  5121.5   390.8  5146.7  392.91
  5151.3  393.22  5200.7  399.39  5233.9  401.43  5250.1  404.21  5299.6  407.94
  5305.5  409.56    5326  411.53  5458.9  421.63  5591.9  430.04  5663.5  435.94
  5673.7  437.94  5679.7  437.12  5684.8  439.19  5694.2  437.92  5704.4  438.25
#Mann= 5 ,-1 , 0
  4541.3     .05       0  4827.6     .16       0  5046.9     .07       0
  5052.9     .16       0  5146.7     .05       0
Bank Sta=4862.7,5151.3
XS Rating Curve= 0 ,0
Exp/Cntr=0.3,0.1

Type RM Length L Ch R = 1 ,27096   ,444,444,444
BEGIN DESCRIPTION:
HOLLY BRANCH 42.0
END DESCRIPTION:
XS GIS Cut Line= 3
      3640899.59     10595160.14      3640749.61     10594760.19
      3640299.62     10593960.21
#Sta/Elev= 30
  4574.7  418.64  4700.1   413.8  4755.3  409.35  4798.9  402.59  4817.2  401.31
    4863  397.32  4901.3  392.28  4926.2  388.21  4977.5  386.29  4980.2  385.79
  4983.5  386.29  5059.2  386.68  5105.1  389.21  5128.1  391.81  5205.8   397.3
  5339.4  409.21  5479.6  419.85  5522.9  424.39  5538.9  422.82  5560.5  422.73
  5566.3  424.04  5598.2  424.51  5632.9  427.16  5678.8  433.72  5684.8  435.69
  5728.2  441.29  5809.1  448.15  5825.1  451.27  5862.4  453.68  5919.7  459.66
#Mann= 5 ,-1 , 0
  4574.7     .05       0  4817.2     .16       0  4977.5     .07       0
  4983.5     .16       0  5205.8     .05       0
Bank Sta=4901.3,5128.1
XS Rating Curve= 0 ,0
Exp/Cntr=0.3,0.1

Type RM Length L Ch R = 1 ,26652   ,417,417,417
BEGIN DESCRIPTION:
HOLLY BRANCH 41.0
END DESCRIPTION:
XS GIS Cut Line= 3
      3641049.61      10594910.2      3641099.61     10594460.19
      3640299.58     10593810.16
#Sta/Elev= 30
  4573.5  409.41  4684.2  404.31    4815  393.39  4825.1  390.48  4848.1  386.96
  4946.3  386.59  5056.7  386.48  5059.2  386.45    5062  385.95  5065.2  386.45
  5076.6   386.6  5132.6  390.99  5154.9  392.08    5168  394.33  5185.3  394.53
  5218.8  396.74  5296.9  405.65  5353.1  410.61    5503  418.95  5594.5  425.77
  5680.7  435.29  5701.5   436.2  5715.9  438.33  5843.7  448.33  5893.3  454.45
  5907.6  455.14  5936.4  459.16  5985.9  463.76  6000.3  466.91  6057.1  469.64
#Mann= 7 ,-1 , 0
  4573.5     .05       0  4848.1     .16       0  4946.3     .05       0
  5056.7     .16       0  5059.2    .033       0  5065.2     .16       0
  5185.3     .05       0
Bank Sta=4815,5132.6
XS Rating Curve= 0 ,0
Exp/Cntr=0.3,0.1

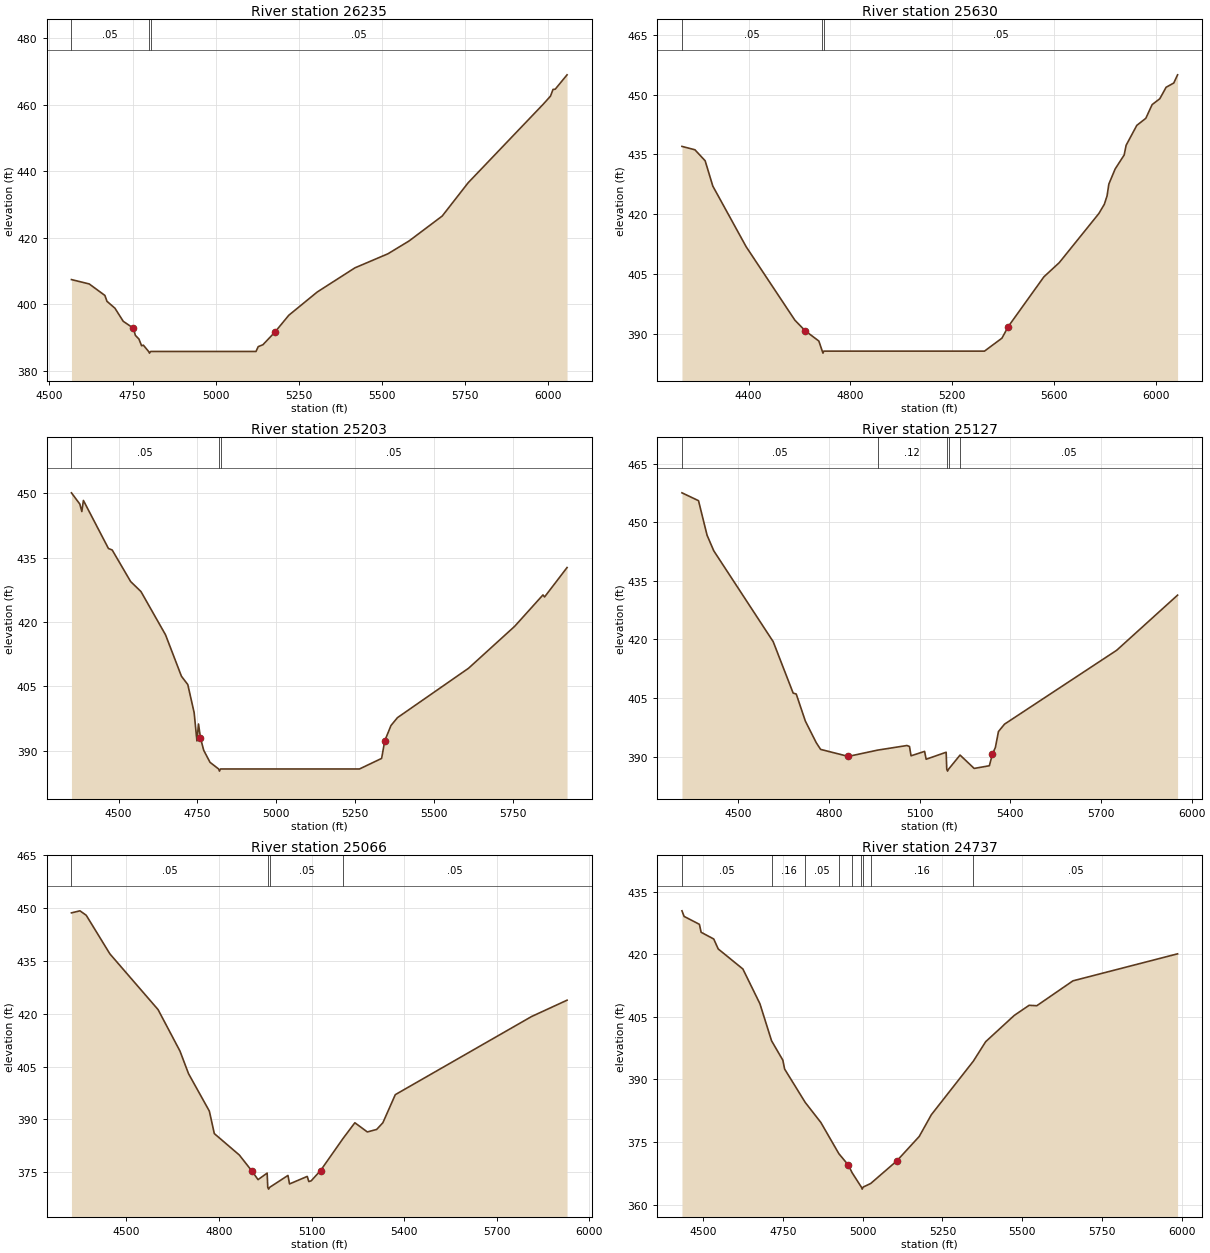
Type RM Length L Ch R = 1 ,26235   ,605,605,605
BEGIN DESCRIPTION:
HOLLY BRANCH 40.0
END DESCRIPTION:
XS GIS Cut Line= 3
      3641599.62     10594660.21      3641449.61     10594260.19
      3640649.63     10593560.21
#Sta/Elev= 30
  4566.4  407.37  4619.8  406.06    4667   402.6  4673.2  400.84  4697.2  398.76
  4722.2  394.82  4752.4  392.77  4758.7  390.59  4769.3   389.5  4777.3  387.48
  4782.7  387.65  4798.4  385.76  4801.1  385.26  4804.4  385.76  5121.3  385.76
  5127.9   387.2  5142.2  387.79  5178.2  391.58    5220  396.65  5305.4  403.63
  5418.8   410.9    5518  415.12  5581.6  418.98  5681.3  426.48  5759.1  436.46
  5985.9  460.19  6006.8  462.52  6014.4  464.53    6021   464.6  6056.6  468.92
#Mann= 3 ,-1 , 0
  4566.4     .05       0  4798.4    .033       0  4804.4     .05       0
Bank Sta=4752.4,5178.2
XS Rating Curve= 0 ,0
Exp/Cntr=0.3,0.1

Type RM Length L Ch R = 1 ,25630   ,427,427,427
BEGIN DESCRIPTION:
HOLLY BRANCH 39.0
END DESCRIPTION:
XS GIS Cut Line= 3
      3642680.04     10593966.92      3641668.76     10593849.73
      3640800.67     10593519.85
#Sta/Elev= 30
  4138.5  437.02  4189.3  436.18  4229.5  433.43  4259.7  427.08  4390.6   411.9
  4581.9  393.52  4622.1  390.88  4676.1  388.29  4689.6  385.76  4692.4  385.26
  4695.6  385.76  5326.8  385.76  5395.4  389.01  5420.2  391.92  5560.1  404.36
  5620.4  407.91  5776.1  420.22  5797.5  422.53  5808.2  424.63  5815.2  427.58
    5840  431.37  5875.4  434.87  5883.1   437.3    5925  442.28  5960.4  444.05
  5985.2  447.48  6015.3  448.95  6040.1  451.82  6070.2  452.89  6085.2  454.94
#Mann= 3 ,-1 , 0
  4138.5     .05       0  4689.6    .033       0  4695.6     .05       0
Bank Sta=4622.1,5420.2
XS Rating Curve= 0 ,0
Exp/Cntr=0.3,0.1

Type RM Length L Ch R = 1 ,25203   ,76,76,76
BEGIN DESCRIPTION:
HOLLY BRANCH 38.0
END DESCRIPTION:
XS GIS Cut Line= 4
      3642516.07     10593518.91       3642009.1     10593463.35
      3641620.21     10593414.74      3640954.04     10593359.22
#Sta/Elev= 30
  4350.6  450.06  4377.2  447.44  4383.5   445.7  4388.5  448.29  4467.8   437.1
  4479.7  436.75  4538.2   429.4  4570.9  427.07  4648.8  416.99  4699.1  407.36
  4719.3  405.41  4739.4  398.87  4748.2  392.29  4753.2  396.24  4759.5  392.97
  4769.6  390.13  4789.7  387.31  4816.9  385.76  4819.6  385.26  4822.9  385.76
  5263.2  385.76  5333.4  388.22  5343.4  392.32    5363  395.87  5383.6  397.71
  5608.8  409.21  5754.9  418.97  5844.7  426.29  5849.7  425.81    5921  432.66
#Mann= 3 ,-1 , 0
  4350.6     .05       0  4816.9    .033       0  4822.9     .05       0
Bank Sta=4759.5,5343.4
XS Rating Curve= 0 ,0
Exp/Cntr=0.3,0.1

Type RM Length L Ch R = 1 ,25127   ,61,61,61
BEGIN DESCRIPTION:
HOLLY BRANCH 37.0
END DESCRIPTION:
XS GIS Cut Line= 5
      3642543.78     10593477.23      3642050.76     10593407.79
      3641717.43     10593338.35       3641634.1      10593331.4
      3640918.84     10593275.85
#Sta/Elev= 30
  4314.1  457.57  4368.8  455.56  4397.2   446.7  4419.3  442.72  4615.9  419.44
  4681.9  406.27  4692.1  406.03  4722.3  399.09  4758.3  393.56  4772.7  391.85
  4864.2  390.05  4961.2  391.66  5058.3  392.84  5066.7   392.6  5071.8   390.2
  5116.7  391.34  5121.8  389.32    5188  391.12    5190  386.78  5192.7  386.28
    5196  386.78    5234  390.39  5280.7  386.97  5330.9  387.66  5340.9  390.59
  5350.9  392.36    5361  396.42    5381  398.31  5752.1  417.24  5953.5  431.36
#Mann= 5 ,-1 , 0
  4314.1     .05       0  4961.2     .12       0    5190     .07       0
    5196     .12       0    5234     .05       0
Bank Sta=4864.2,5340.9
XS Rating Curve= 0 ,0
Exp/Cntr=0.3,0.1

Type RM Length L Ch R = 1 ,25066   ,329,329,329
BEGIN DESCRIPTION:
HOLLY BRANCH 36.0
END DESCRIPTION:
XS GIS Cut Line= 3
      3642536.92     10593414.74      3641613.26      10593268.9
      3640946.62     10593192.52
#Sta/Elev= 30
    4322  448.68  4349.6  449.26  4369.9     448  4446.6  437.03  4602.7  421.21
  4673.6  409.45  4701.4  403.02  4768.9  392.38    4785  385.99    4866  379.91
  4906.5   375.4  4926.7  372.92  4956.2  374.77  4958.2  370.72    4961  370.22
  4964.2  370.72  5023.7  374.11  5028.7  371.69  5086.1  373.83  5091.2  372.37
  5098.8  372.57  5129.2  375.49  5203.4  384.76  5240.5  389.07  5280.9  386.46
  5311.1  387.17  5331.2  389.07  5371.5  397.05  5813.1  419.24  5928.1  423.88
#Mann= 4 ,-1 , 0
    4322     .05       0  4958.2     .07       0  4964.2     .05       0
  5203.4     .05       0
Bank Sta=4906.5,5129.2
XS Rating Curve= 0 ,0
Exp/Cntr=0.3,0.1

Type RM Length L Ch R = 1 ,24737   ,826,826,826
BEGIN DESCRIPTION:
Mapping XS 4c63a313
END DESCRIPTION:
XS GIS Cut Line= 2
      3642471.69     10593207.36      3641036.65     10592617.85
#Sta/Elev= 30
  4434.7  430.47  4441.4  429.13  4489.3  427.23  4494.7  425.32  4534.2  423.71
  4548.1  421.33  4625.4  416.51  4678.7  408.18  4715.2  399.28  4750.5  394.63
    4756  392.51  4820.5   384.5  4869.4  379.69  4925.7  372.21  4955.9  369.42
  4967.2  367.64  4996.1  364.19  4998.9  363.69  5002.1  364.19  5025.6  365.05
  5107.2  370.46  5177.4  376.33  5215.3  381.54  5346.7  394.39  5385.4  399.07
  5474.8  405.37  5521.4   407.8  5545.4   407.7  5658.6  413.67  5986.1  420.15
#Mann= 9 ,-1 , 0
  4434.7     .05       0  4715.2     .16       0  4820.5     .05       0
  4925.7     .16       0  4967.2     .12       0  4996.1     .07       0
  5002.1     .12       0  5025.6     .16       0  5346.7     .05       0
Bank Sta=4955.9,5107.2
XS Rating Curve= 0 ,0
Exp/Cntr=0.3,0.1

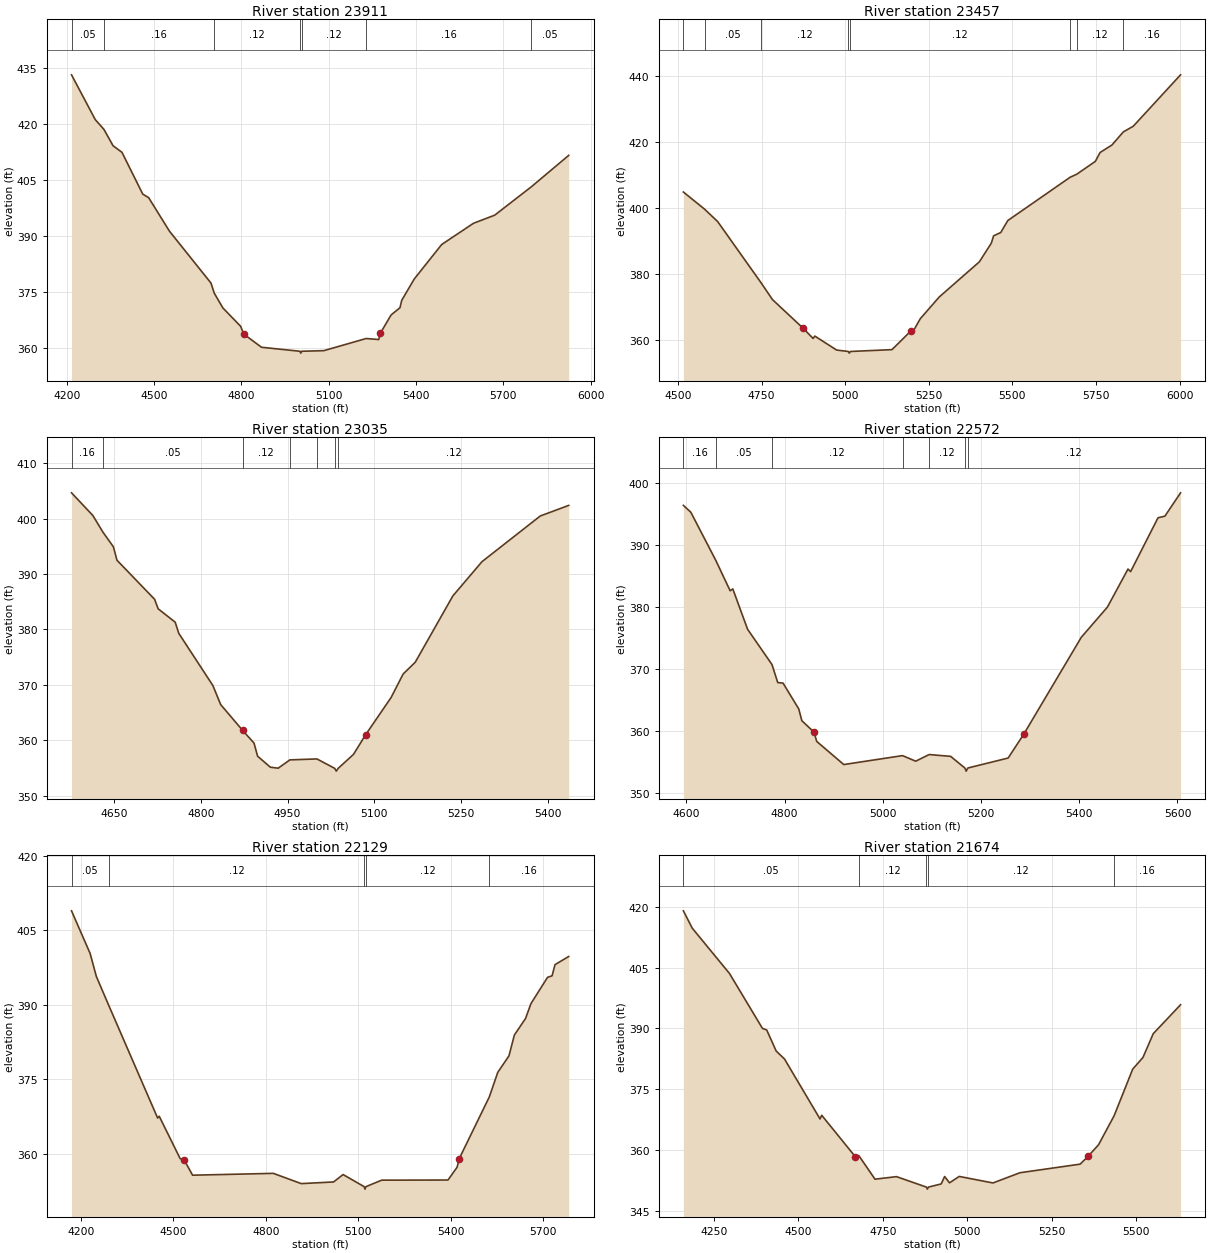
Type RM Length L Ch R = 1 ,23911   ,454,454,454
BEGIN DESCRIPTION:
HOLLY BRANCH 35.0
END DESCRIPTION:
XS GIS Cut Line= 3
      3642549.61     10593210.18      3642399.61     10592460.19
      3641899.63     10591660.22
#Sta/Elev= 30
  4216.6  433.13  4298.2  421.14    4328  418.52  4359.4  414.14    4390  412.38
  4461.3  401.21  4481.7  400.24  4553.1  391.28  4695.9  377.38    4707  374.69
  4736.7  370.73  4797.9   365.8  4808.1  363.76  4869.3  360.21  5001.4  359.14
  5004.2  358.64  5007.4  359.14  5083.4   359.3  5228.9  362.55  5272.1  362.28
    5278  364.01  5314.6  368.86  5345.2   370.8  5351.1  372.77  5394.2  378.49
  5488.5  387.72  5597.6  393.39  5670.7  395.57  5796.9  403.19  5924.8  411.57
#Mann= 7 ,-1 , 0
  4216.6     .05       0    4328     .16       0    4707     .12       0
  5001.4     .07       0  5007.4     .12       0  5228.9     .16       0
  5796.9     .05       0
Bank Sta=4808.1,5278
XS Rating Curve= 0 ,0
Exp/Cntr=0.3,0.1

Type RM Length L Ch R = 1 ,23457   ,422,422,422
BEGIN DESCRIPTION:
HOLLY BRANCH 34.0
END DESCRIPTION:
XS GIS Cut Line= 3
      3642999.59     10591960.19      3642549.61     10592060.19
      3641849.59     10591310.17
#Sta/Elev= 30
  4515.9  404.87  4579.1  399.68  4618.3  395.91  4748.7  377.24  4782.2  372.22
  4874.4  363.46  4903.9  360.39    4909  361.12  4974.3  356.87  5009.3  356.44
    5012  355.94  5015.3  356.44  5139.8     357    5196  362.64  5203.3  362.61
  5224.3  366.38    5281  372.98  5401.1  383.67  5436.8  389.32  5443.7  391.56
  5465.1  392.57  5486.2  396.21  5672.7  409.36  5692.5  410.28    5748  414.18
  5762.2  416.88  5797.6  419.14  5831.7  423.13  5861.3  424.84  6002.8  440.46
#Mann= 8 ,-1 , 0
  4515.9     .16       0  4579.1     .05       0  4748.7     .12       0
  5009.3     .07       0  5015.3     .12       0  5672.7     .16       0
  5692.5     .12       0  5831.7     .16       0
Bank Sta=4874.4,5196
XS Rating Curve= 0 ,0
Exp/Cntr=0.3,0.1

Type RM Length L Ch R = 1 ,23035   ,463,463,463
BEGIN DESCRIPTION:
HOLLY BRANCH 33.0
END DESCRIPTION:
XS GIS Cut Line= 3
      3643049.62      10591910.2      3642699.61     10591660.19
      3642349.57     10591410.16
#Sta/Elev= 30
  4576.1  404.65    4613  400.56  4630.6  397.53  4648.6   394.9  4654.8  392.48
  4719.9  385.43    4726  383.72  4755.5   381.3  4761.7  379.29  4820.7  369.87
  4834.2  366.43  4872.2  361.77  4891.9  359.48  4898.1  357.11  4920.2  355.13
  4933.7  354.95  4953.9  356.45  5000.8  356.62  5031.5  354.92  5034.3  354.42
  5037.5  354.92    5064  357.44  5084.9  360.97  5129.1  367.71    5150  371.96
  5170.9  374.08    5236  386.05  5286.4  392.23  5387.2  400.47  5436.4  402.38
#Mann= 7 ,-1 , 0
  4576.1     .16       0  4630.6     .05       0  4872.2     .12       0
  4953.9     .16       0  5000.8     .12       0  5031.5     .07       0
  5037.5     .12       0
Bank Sta=4872.2,5084.9
XS Rating Curve= 0 ,0
Exp/Cntr=0.3,0.1

Type RM Length L Ch R = 1 ,22572   ,443,443,443
BEGIN DESCRIPTION:
HOLLY BRANCH 32.0
END DESCRIPTION:
XS GIS Cut Line= 3
      3643199.61     10591760.19      3643049.61     10591360.19
      3642499.64      10591160.2
#Sta/Elev= 30
  4593.9  396.35    4609  395.25  4659.9  387.49  4689.1  382.59  4694.5  382.89
  4724.7  376.38  4774.3   370.7  4786.1  367.79  4796.8  367.71  4828.9  363.54
  4835.1  361.65    4860  359.79  4865.4  358.31  4920.5  354.58  5040.2  356.02
    5067  355.12  5094.3  356.19  5138.1   355.9  5167.1  354.02  5169.8  353.52
  5173.1  354.02  5255.2  355.63  5287.1  359.48  5404.2  375.09  5457.4  379.96
  5499.3  386.09  5504.6  385.67  5560.4  394.35  5574.4  394.61  5606.3  398.37
#Mann= 7 ,-1 , 0
  4593.9     .16       0  4659.9     .05       0  4774.3     .12       0
  5040.2     .16       0  5094.3     .12       0  5167.1     .07       0
  5173.1     .12       0
Bank Sta=4860,5287.1
XS Rating Curve= 0 ,0
Exp/Cntr=0.3,0.1

Type RM Length L Ch R = 1 ,22129   ,455,455,455
BEGIN DESCRIPTION:
HOLLY BRANCH 31.0
END DESCRIPTION:
XS GIS Cut Line= 3
      3644149.56     10591010.19      3643349.61     10591110.19
      3642599.56     10590810.17
#Sta/Elev= 30
  4169.3  408.89  4229.7  400.32  4249.9   395.7  4290.6  389.82  4448.9  367.23
  4453.9  367.61    4522  359.08  4534.6  358.86  4562.3  355.75  4824.3  356.12
    4915  354.06  5019.9  354.39  5050.9  355.88  5119.2  353.45    5122  352.95
  5125.2  353.45  5176.1  354.75  5391.5  354.78  5421.1  357.36  5427.8  359.06
  5525.7   371.5    5553  376.42  5589.4  379.74  5606.9  383.92  5643.2  387.25
  5660.7  390.23  5714.6  395.52  5729.4  395.83  5738.8  398.07  5783.3  399.71
#Mann= 5 ,-1 , 0
  4169.3     .05       0  4290.6     .12       0  5119.2     .07       0
  5125.2     .12       0  5525.7     .16       0
Bank Sta=4534.6,5427.8
XS Rating Curve= 0 ,0
Exp/Cntr=0.3,0.1

Type RM Length L Ch R = 1 ,21674   ,395,395,395
BEGIN DESCRIPTION:
HOLLY BRANCH 30.0
END DESCRIPTION:
XS GIS Cut Line= 3
      3644249.63     10590810.19      3643449.61     10590660.19
      3642799.62     10590560.19
#Sta/Elev= 30
  4159.5  419.01  4185.8  414.73    4296  403.56  4393.5  390.03  4406.2  389.63
  4434.2  384.44  4458.8  382.48  4563.9   367.7    4569   368.6  4668.2  358.41
  4678.6  358.68  4726.7  352.84  4790.3  353.47  4878.9  350.89  4881.6  350.39
  4884.9  350.89  4922.6  351.67  4932.8   353.5  4947.2  351.94    4976  353.52
  5075.9  351.91  5155.6  354.43  5333.9  356.55  5357.9  358.52  5388.3  361.32
  5434.4  368.47  5489.5  379.98  5519.8  382.85  5550.2  388.71  5631.1  395.85
#Mann= 5 ,-1 , 0
  4159.5     .05       0  4678.6     .12       0  4878.9     .07       0
  4884.9     .12       0  5434.4     .16       0
Bank Sta=4668.2,5357.9
XS Rating Curve= 0 ,0
Exp/Cntr=0.3,0.1

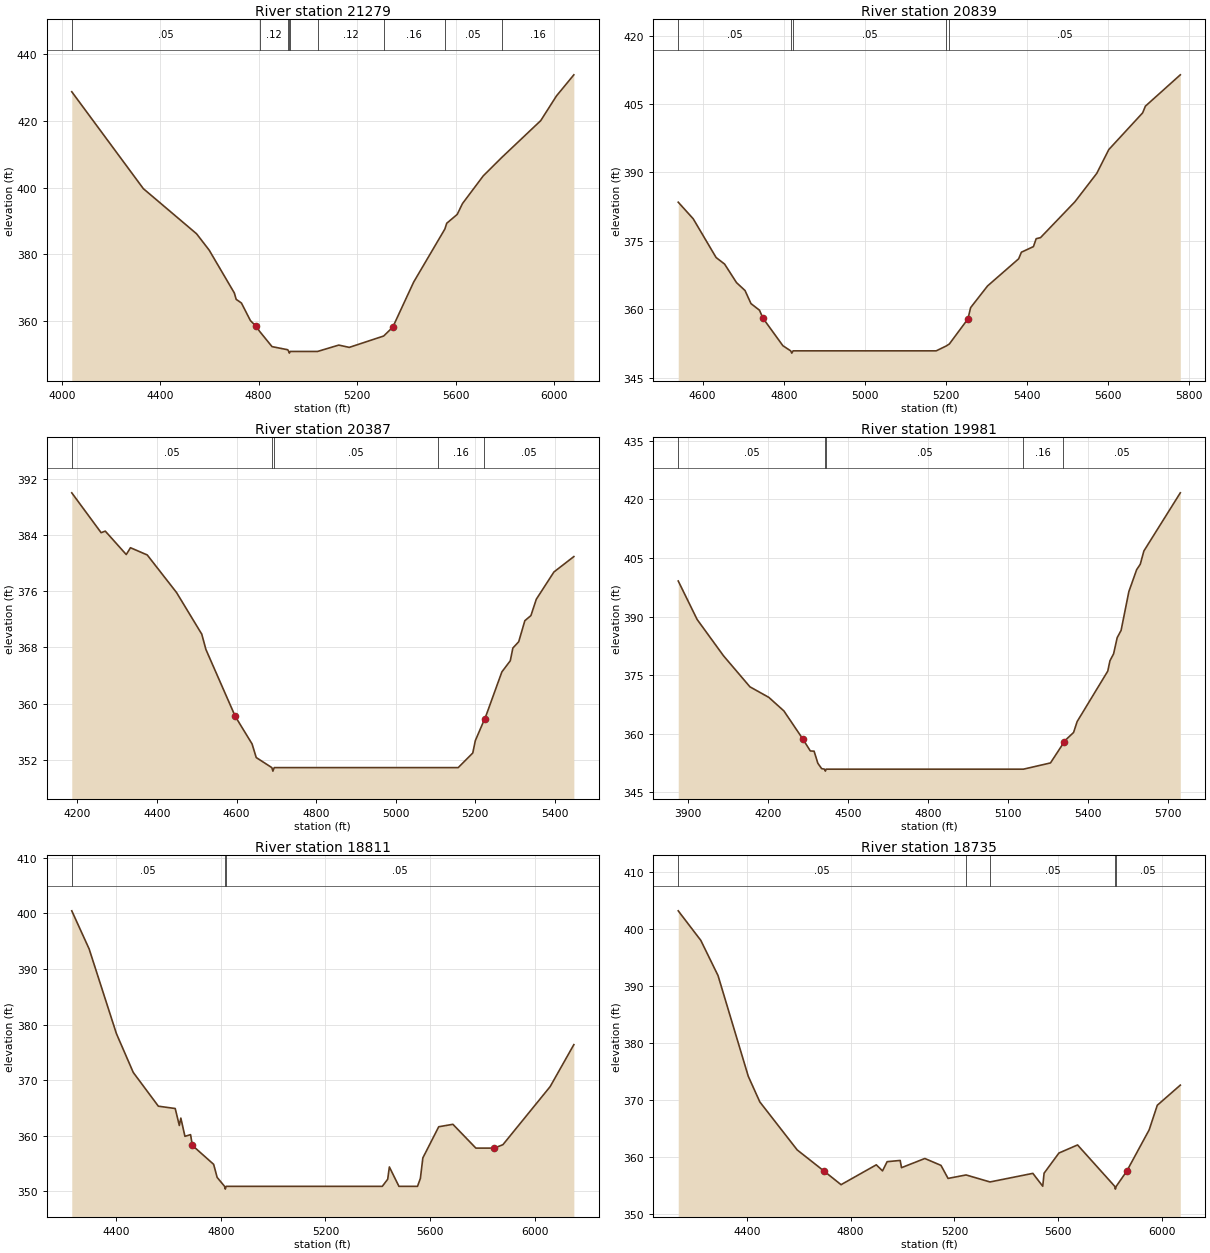
Type RM Length L Ch R = 1 ,21279   ,440,440,440
BEGIN DESCRIPTION:
HOLLY BRANCH 29.0
END DESCRIPTION:
XS GIS Cut Line= 3
      3644349.65     10590810.21      3643549.61     10590310.19
      3642749.63     10589560.21
#Sta/Elev= 30
  4040.7  428.71  4331.4  399.68  4547.8  386.15  4599.1  381.24  4701.1  368.43
  4708.8   366.5    4730  365.41  4766.6  360.14  4787.8  358.56  4804.4  356.87
  4854.4  352.34  4918.3   351.4  4922.2  350.89  4924.9  350.39  4928.2  350.89
  5039.3  350.89  5125.6   352.8  5168.1  352.11  5308.1  355.52  5344.9  358.16
  5429.9  371.68  5556.7  387.58  5564.2   389.3  5606.7  391.95  5628.2   395.2
  5712.7  403.51  5787.1  408.96  5946.2  420.06  6010.1  427.46  6080.7  433.78
#Mann= 9 ,-1 , 0
  4040.7     .05       0  4804.4     .12       0  4918.3     .05       0
  4922.2    .033       0  4928.2     .05       0  5039.3     .12       0
  5308.1     .16       0  5556.7     .05       0  5787.1     .16       0
Bank Sta=4787.8,5344.9
XS Rating Curve= 0 ,0
Exp/Cntr=0.3,0.1

Type RM Length L Ch R = 1 ,20839   ,452,452,452
BEGIN DESCRIPTION:
HOLLY BRANCH 28.0
END DESCRIPTION:
XS GIS Cut Line= 3
      3644099.63      10590160.2      3643749.61     10589910.19
      3642999.62     10589610.19
#Sta/Elev= 30
  4539.9  383.47  4576.8  379.84  4633.3  371.34  4654.2  369.91  4683.7  365.83
  4704.6  364.11  4719.3  361.24  4740.2   359.8  4748.8  358.05    4798  352.01
  4817.1  350.89  4819.9  350.39  4823.1  350.89    5176  350.89  5200.5  351.95
  5208.3  352.39  5254.1  357.88  5260.8  360.36  5302.6  365.12  5379.3  371.07
    5386  372.51  5415.7  373.74  5422.4  375.47  5433.2  375.71    5518  383.57
  5571.8  389.79  5601.5  395.01  5684.9  403.05  5691.7  404.52  5777.8  411.39
#Mann= 5 ,-1 , 0
  4539.9     .05       0  4817.1    .033       0  4823.1     .05       0
  5200.5     .16       0  5208.3     .05       0
Bank Sta=4748.8,5254.1
XS Rating Curve= 0 ,0
Exp/Cntr=0.3,0.1

Type RM Length L Ch R = 1 ,20387   ,406,406,406
BEGIN DESCRIPTION:
HOLLY BRANCH 27.0
END DESCRIPTION:
XS GIS Cut Line= 3
      3644199.61      10590260.2      3643949.61     10589510.19
       3643549.6     10589260.18
#Sta/Elev= 30
  4185.7  389.98  4259.5  384.31    4270  384.53  4322.7   381.2  4333.3  382.17
  4375.5  381.14  4449.2  375.79  4512.5  369.88    4523  367.69  4596.8  358.17
    4639  354.26  4649.5  352.32  4688.7  350.89  4691.4  350.39  4694.7  350.89
  5107.3  350.89  5157.3  350.89  5193.9  352.97  5200.3  354.73  5221.1  357.47
  5223.9  357.76    5267   364.5  5288.2  366.09  5294.7   367.9  5309.4   368.8
  5324.8  371.79  5340.1  372.52  5353.6  374.84  5397.9  378.72    5448  380.91
#Mann= 5 ,-1 , 0
  4185.7     .05       0  4688.7    .033       0  4694.7     .05       0
  5107.3     .16       0  5221.1     .05       0
Bank Sta=4596.8,5223.9
XS Rating Curve= 0 ,0
Exp/Cntr=0.3,0.1

Type RM Length L Ch R = 1 ,19981   ,1170,1170,1170
BEGIN DESCRIPTION:
HOLLY BRANCH 26.0
END DESCRIPTION:
XS GIS Cut Line= 3
       3644949.6     10589960.18      3644149.61     10589160.19
      3643699.58     10588560.15
#Sta/Elev= 30
  3863.1  399.11  3933.8  389.26  4032.8  379.94  4131.8  371.99  4202.5  369.29
  4259.1  365.81  4329.8  358.64  4358.1  355.56  4372.2   355.5  4386.3   352.4
  4400.5  351.03  4411.6  350.89  4414.4  350.39  4417.6  350.89  5156.6  350.89
    5258  352.49  5304.9   357.4    5308  357.94  5344.5  360.29    5358   363.1
  5472.6  376.01  5480.9  378.68  5494.5  380.45    5508   384.6  5522.6  386.45
  5551.7  396.39  5580.9  402.01  5594.5  403.41    5608   406.8  5744.5   421.7
#Mann= 5 ,-1 , 0
  3863.1     .05       0  4411.6    .033       0  4417.6     .05       0
  5156.6     .16       0  5304.9     .05       0
Bank Sta=4329.8,5308
XS Rating Curve= 0 ,0
Exp/Cntr=0.3,0.1

Type RM Length L Ch R = 1 ,18811   ,76,76,76
BEGIN DESCRIPTION:
HOLLY BRANCH 25.0
END DESCRIPTION:
XS GIS Cut Line= 4
      3645293.82     10588977.23      3644967.43     10588421.68
      3644814.65     10587873.07      3644120.21     10587761.96
#Sta/Elev= 30
  4231.2  400.45  4297.4  393.61  4401.6  378.37    4466  371.38  4561.8  365.31
  4626.2  364.89  4641.9  361.84  4647.7  363.17  4663.3  359.89  4684.8  360.19
  4691.7  358.25  4772.9  354.85  4786.3   352.5  4814.7  350.89  4817.4  350.39
  4820.7  350.89  5416.9  350.89  5437.6  352.18  5443.9  354.38  5480.5  350.89
  5551.4  350.89  5562.4  352.33  5571.7     356  5632.4  361.61  5686.5  362.05
  5774.2  357.77  5845.1  357.77  5877.6  358.39  6057.8  368.83  6148.3  376.38
#Mann= 3 ,-1 , 0
  4231.2     .05       0  4814.7    .033       0  4820.7     .05       0
Bank Sta=4691.7,5845.1
XS Rating Curve= 0 ,0
Exp/Cntr=0.3,0.1

Type RM Length L Ch R = 1 ,18735   ,119,119,119
BEGIN DESCRIPTION:
HOLLY BRANCH 24.0
END DESCRIPTION:
XS GIS Cut Line= 5
      3645397.99     10589011.97      3645036.87     10588407.79
       3644946.6     10588088.35      3644849.37     10587838.35
      3644233.01     10587699.84
#Sta/Elev= 30
  4135.3  403.24  4222.3  398.05  4288.8  391.86  4405.3  374.18  4449.9  369.67
  4593.9  361.24  4696.6  357.55  4763.1  355.13    4899  358.62    4923  357.55
  4940.6  359.17    4991  359.39  4996.2  358.12  5086.1  359.73  5148.4  358.52
  5175.6  356.23  5245.1  356.84  5337.3  355.61  5502.6  357.12  5540.7  354.86
  5545.9  357.15  5603.1  360.69  5674.9  362.11  5818.1  354.85  5820.8  354.35
  5824.1  354.85  5864.4  357.49    5951  364.76  5982.3  369.08  6071.1  372.62
#Mann= 5 ,-1 , 0
  4135.3     .05       0  5245.1     .12       0  5337.3     .05       0
  5818.1     .03       0  5824.1     .05       0
Bank Sta=4696.6,5864.4
XS Rating Curve= 0 ,0
Exp/Cntr=0.3,0.1

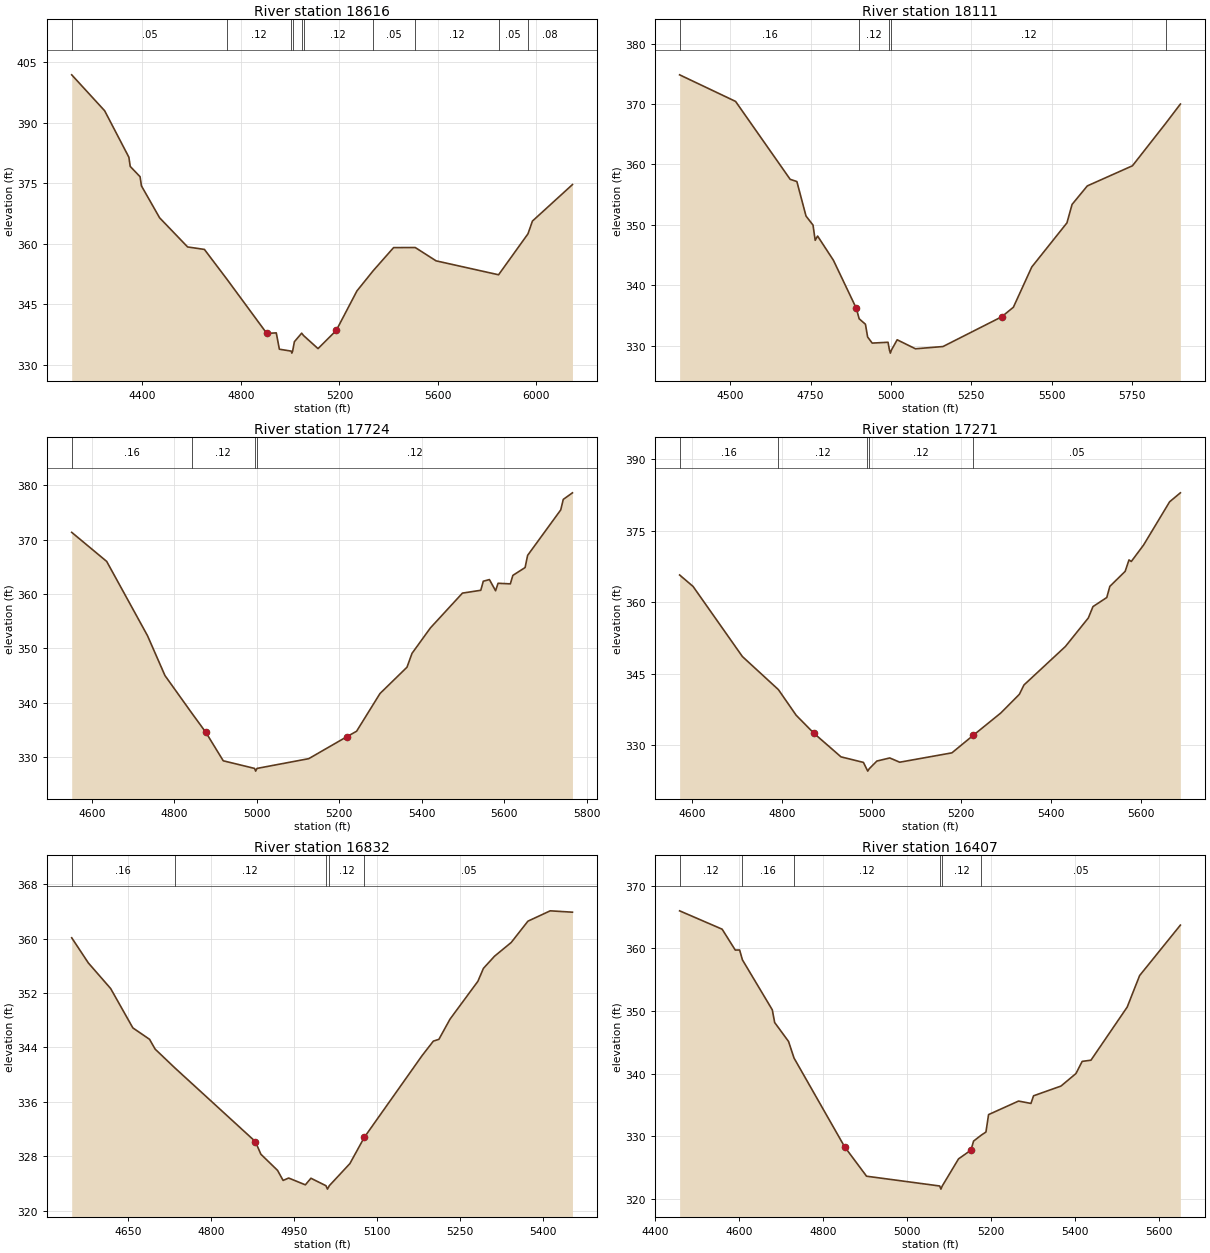
Type RM Length L Ch R = 1 ,18616   ,505,505,505
BEGIN DESCRIPTION:
HOLLY BRANCH 23.0
END DESCRIPTION:
XS GIS Cut Line= 6
      3645425.77     10588991.13      3645113.26      10588331.4
      3645050.76     10587991.13      3644967.43      10587831.4
      3644814.65     10587741.13      3644224.45     10587636.97
#Sta/Elev= 30
  4113.3  401.82  4247.1  392.92  4345.4  381.41  4350.9  379.13  4390.9  376.58
  4396.4  374.32  4470.2   366.4  4583.9  359.18  4652.1  358.57  4744.2  351.13
  4905.5  337.75  4943.8   337.9  4956.4  333.85  5004.2  333.38    5007  332.88
  5010.2  333.38  5017.4  335.71  5046.9  337.82  5054.6  337.23  5113.3     334
  5187.2  338.49  5271.2  348.28  5337.1  353.28  5420.1  359.02    5508  359.04
  5592.6  355.74  5846.3  352.29  5965.7  362.44  5983.7  365.59  6146.2  374.63
#Mann= 10 ,-1 , 0
  4113.3     .05       0  4744.2     .12       0  5004.2     .07       0
  5010.2     .12       0  5046.9     .05       0  5054.6     .12       0
  5337.1     .05       0    5508     .12       0  5846.3     .05       0
  5965.7     .08       0
Bank Sta=4905.5,5187.2
XS Rating Curve= 0 ,0
Exp/Cntr=0.3,0.1

Type RM Length L Ch R = 1 ,18111   ,387,387,387
BEGIN DESCRIPTION:
HOLLY BRANCH 22.0
END DESCRIPTION:
XS GIS Cut Line= 3
      3645842.42     10588282.78      3645349.37     10587727.24
       3645085.5     10586956.43
#Sta/Elev= 30
  4342.6  374.83  4516.6  370.43  4686.4  357.53  4707.3  357.16  4735.7  351.45
  4757.5  349.95  4764.2  347.43  4771.7  348.14    4821  344.12  4892.1  336.18
    4901  334.44  4920.6  333.53  4927.3  331.43  4941.5  330.41  4990.8  330.55
  4995.3  329.25  4998.1  328.75  5001.3  329.25  5019.2  330.96  5076.1  329.47
  5161.7  329.84  5344.2  334.76  5380.7  336.35    5438  343.02  5547.3  350.32
  5563.2  353.37  5610.7  356.44    5751  359.77  5854.7  366.81  5900.1  369.99
#Mann= 5 ,-1 , 0
  4342.6     .16       0    4901     .12       0  4995.3     .07       0
  5001.3     .12       0  5854.7     .05       0
Bank Sta=4892.1,5344.2
XS Rating Curve= 0 ,0
Exp/Cntr=0.3,0.1

Type RM Length L Ch R = 1 ,17724   ,453,453,453
BEGIN DESCRIPTION:
HOLLY BRANCH 21.0
END DESCRIPTION:
XS GIS Cut Line= 3
      3645899.62      10587810.2      3645599.61     10587510.19
      3645149.58     10586860.15
#Sta/Elev= 30
  4550.7  371.35  4635.6     366  4734.6  352.34    4777     345  4842.3  338.07
    4876  334.57  4918.4  329.32  4994.3  327.92    4997  327.42  5000.3  327.92
  5125.7  329.71  5218.2  333.75  5241.9  334.76  5298.6  341.69  5364.2  346.54
  5376.3  349.08  5420.9  353.76  5498.7  360.17  5543.2  360.69  5549.3  362.36
  5564.2  362.66  5579.1   360.6  5585.1  361.98  5614.9  361.87    5621  363.43
  5650.7  364.87  5656.8  367.11  5737.2  375.48  5743.3  377.41  5765.6  378.62
#Mann= 4 ,-1 , 0
  4550.7     .16       0  4842.3     .12       0  4994.3     .07       0
  5000.3     .12       0
Bank Sta=4876,5218.2
XS Rating Curve= 0 ,0
Exp/Cntr=0.3,0.1

Type RM Length L Ch R = 1 ,17271   ,439,439,439
BEGIN DESCRIPTION:
HOLLY BRANCH 20.0
END DESCRIPTION:
XS GIS Cut Line= 3
      3645899.61     10587710.18      3645899.61     10587260.19
       3645749.6     10586610.16
#Sta/Elev= 30
  4571.6  365.71  4601.6  363.31  4711.6  348.62    4792  341.68  4831.6  336.31
  4871.6   332.5  4931.6  327.59  4981.6  326.43  4988.6   325.1  4991.3   324.6
  4994.6   325.1  5011.6  326.71  5040.4  327.36  5062.6  326.47    5179  328.43
  5226.2  332.07  5288.4  336.81  5329.5   340.7  5339.7  342.65  5432.1  350.71
  5483.4  356.71  5493.7  359.08  5524.5  360.99  5531.3  363.32  5565.5  366.47
  5574.1  368.87  5579.2  368.54  5606.6  371.99  5664.7  381.05  5688.7  382.93
#Mann= 5 ,-1 , 0
  4571.6     .16       0    4792     .12       0  4988.6     .07       0
  4994.6     .12       0  5226.2     .05       0
Bank Sta=4871.6,5226.2
XS Rating Curve= 0 ,0
Exp/Cntr=0.3,0.1

Type RM Length L Ch R = 1 ,16832   ,425,425,425
BEGIN DESCRIPTION:
HOLLY BRANCH 19.0
END DESCRIPTION:
XS GIS Cut Line= 3
       3646349.6     10587610.15      3646299.61     10587160.19
      3646249.61     10586710.19
#Sta/Elev= 30
  4547.9  360.13    4578  356.43  4618.3  352.67  4658.5  346.88  4688.7   345.2
  4698.8  343.76  4734.2  341.02  4879.9  330.18    4890  328.31  4920.1  325.94
  4930.2  324.46  4940.3  324.81  4970.4  323.81  4980.5  324.78  5007.7  323.68
  5010.4  323.18  5013.7  323.68  5050.9  326.93    5077  330.79  5181.7  342.83
  5201.9  344.94  5211.9   345.2    5232  348.17  5282.4  353.73  5292.4  355.63
  5312.5  357.42  5342.7  359.44  5372.9  362.57  5413.2  364.09  5453.4  363.89
#Mann= 5 ,-1 , 0
  4547.9     .16       0  4734.2     .12       0  5007.7     .07       0
  5013.7     .12       0    5077     .05       0
Bank Sta=4879.9,5077
XS Rating Curve= 0 ,0
Exp/Cntr=0.3,0.1

Type RM Length L Ch R = 1 ,16407   ,500,500,500
BEGIN DESCRIPTION:
HOLLY BRANCH 18.0
END DESCRIPTION:
XS GIS Cut Line= 3
      3646522.98     10587687.32      3646705.28     10587062.31
      3646263.59     10586750.53
#Sta/Elev= 30
  4458.5  365.99  4559.7  363.06  4590.9  359.73  4601.3  359.74    4608  358.16
    4679   350.2  4684.7  348.17  4717.7  345.15  4730.8   342.5  4851.3  328.33
  4903.4  323.65  5077.5  322.09  5080.3  321.59  5083.5  322.09  5122.3  326.42
  5151.8  327.81    5158  329.25  5176.3   330.2  5187.5   330.7  5193.7  333.48
  5265.1  335.64  5294.6  335.26  5300.8  336.48    5366  338.03  5401.7  340.03
  5416.5  341.97  5437.4  342.16  5523.6  350.63  5553.2  355.66  5650.2  363.71
#Mann= 6 ,-1 , 0
  4458.5     .12       0    4608     .16       0  4730.8     .12       0
  5077.5     .07       0  5083.5     .12       0  5176.3     .05       0
Bank Sta=4851.3,5151.8
XS Rating Curve= 0 ,0
Exp/Cntr=0.3,0.1