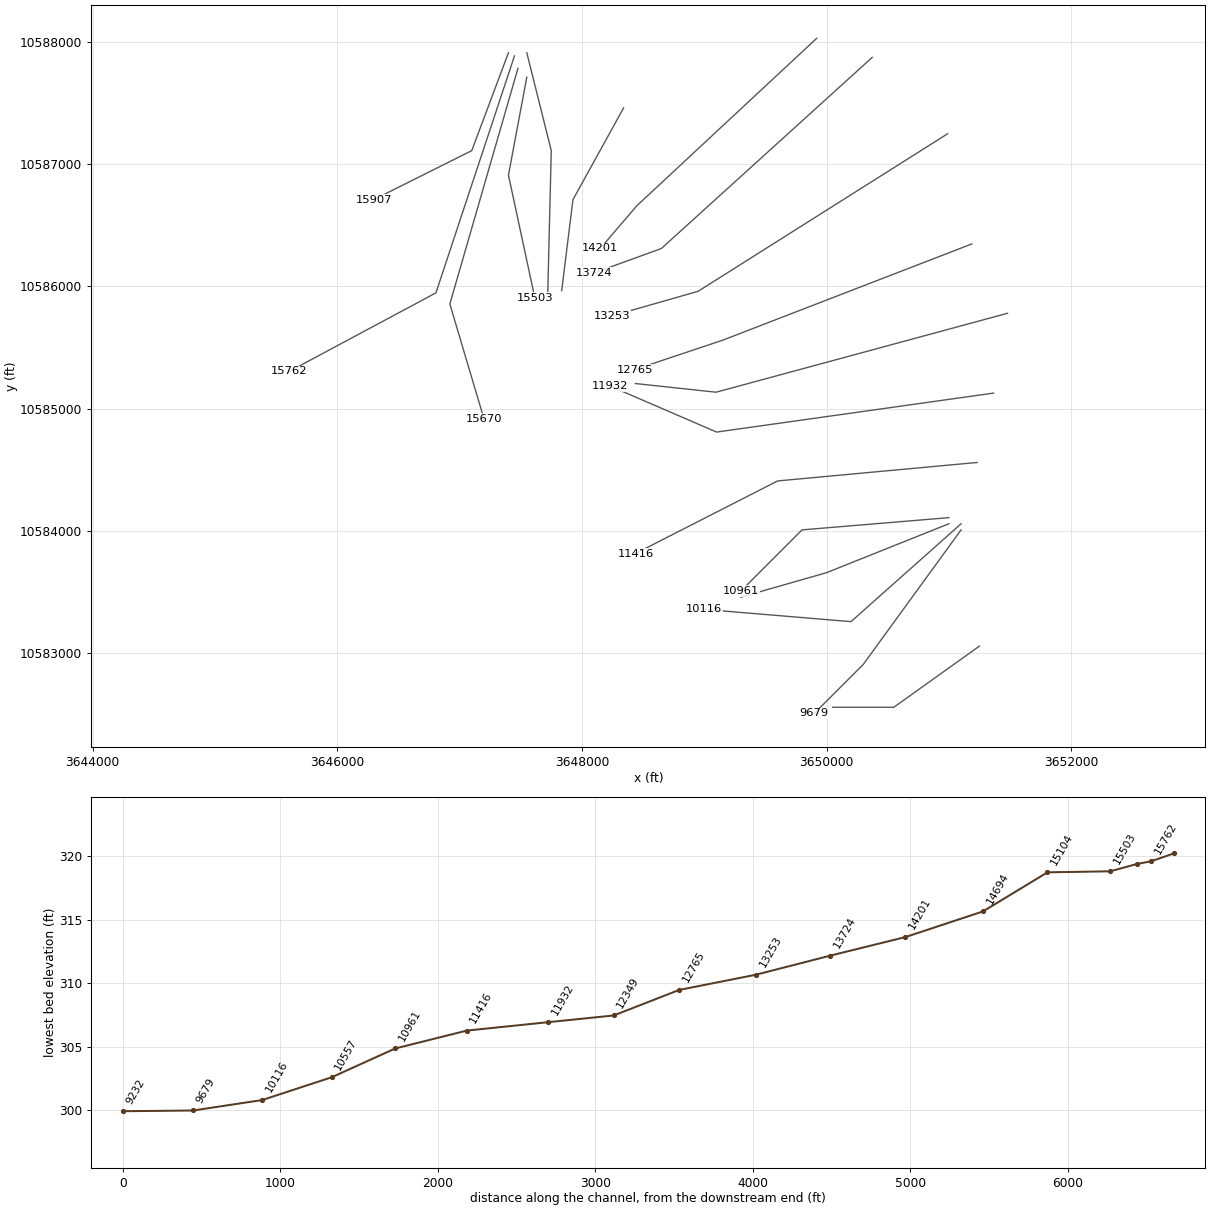
HEC-RAS study HOLLY BRANCH.prj: HOLLY BRANCH Base Level Engineering

--- HOLLY BRANCH.g01 (geometry) --- (continued)

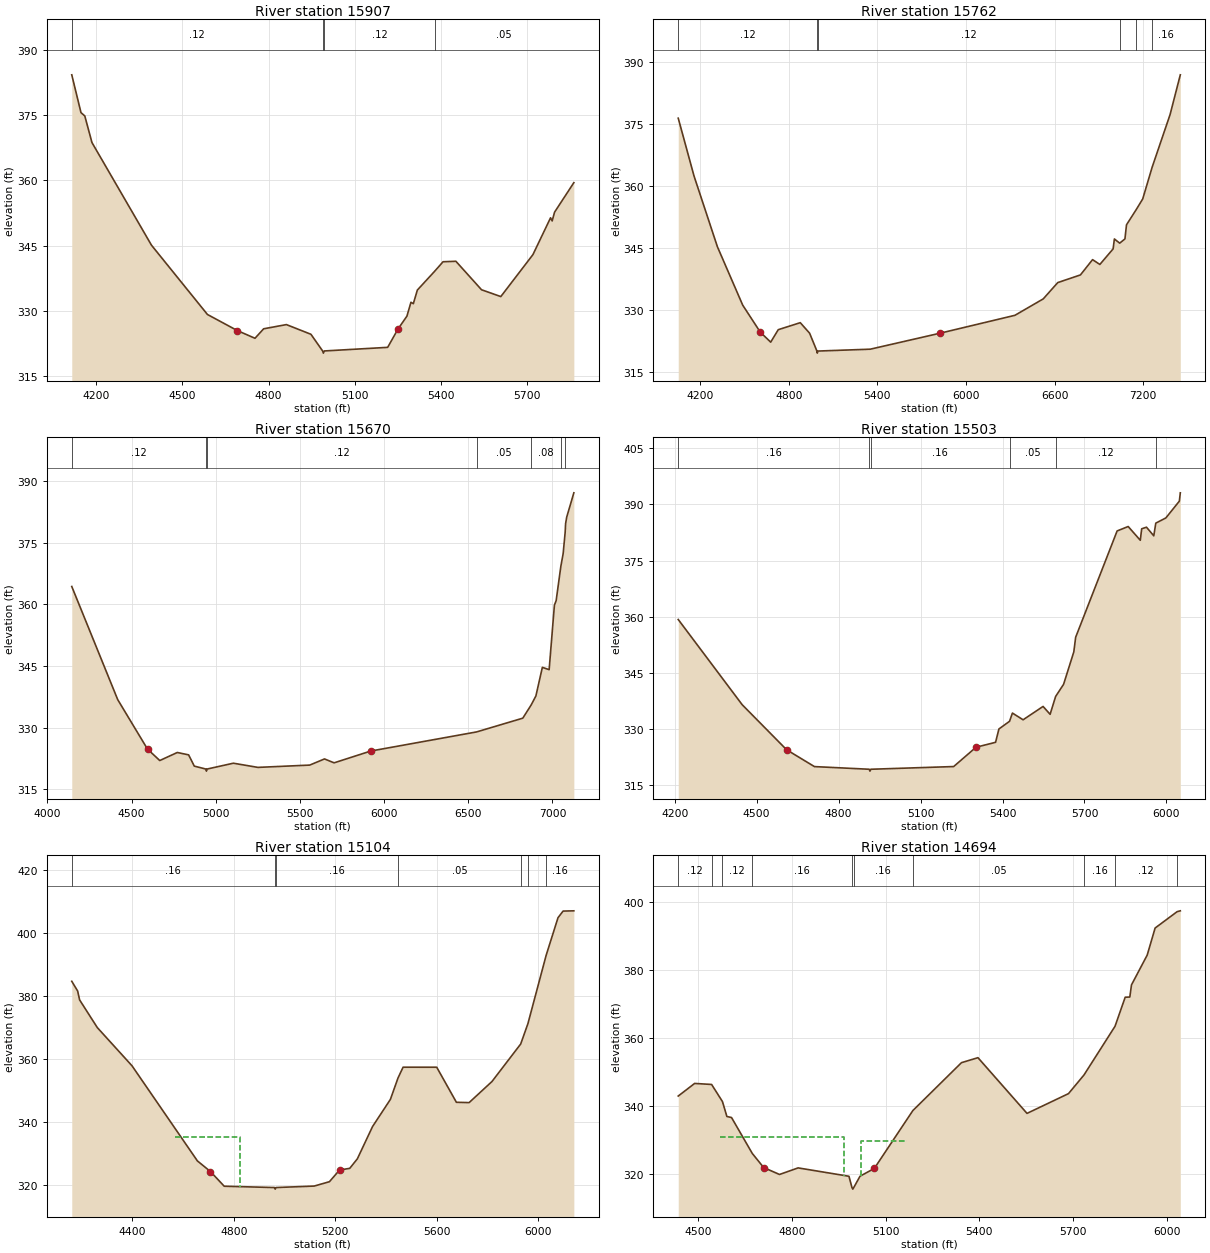
Type RM Length L Ch R = 1 ,15907   ,145,145,145
BEGIN DESCRIPTION:
HOLLY BRANCH 17.0
END DESCRIPTION:
XS GIS Cut Line= 3
      3647399.62     10587910.22      3647099.61     10587110.19
      3646299.58     10586710.17
#Sta/Elev= 30
  4114.4  384.32  4146.5  375.62  4159.8  374.85  4184.7  368.73  4392.1  345.09
    4587  329.14  4691.2  325.43  4752.6  323.66  4782.8  325.84    4862  326.81
  4947.5  324.58  4988.2  320.74  4990.9  320.24  4994.2  320.74  5214.8  321.57
  5251.1  325.82  5281.9  328.76  5295.9  331.95  5304.2  331.62  5318.2  334.76
  5378.2  339.07  5407.7  341.28  5452.4  341.39  5541.8  334.83  5608.9  333.26
  5720.7  342.91  5782.2   351.4  5787.8  350.68  5796.2   352.7  5863.3  359.49
#Mann= 4 ,-1 , 0
  4114.4     .12       0  4988.2     .07       0  4994.2     .12       0
  5378.2     .05       0
Bank Sta=4691.2,5251.1
XS Rating Curve= 0 ,0
Exp/Cntr=0.3,0.1

Type RM Length L Ch R = 1 ,15762   ,92,92,92
BEGIN DESCRIPTION:
Mapping XS 15f6aa43
END DESCRIPTION:
XS GIS Cut Line= 3
      3647448.85     10587884.59      3646806.99     10585947.64
      3645608.47     10585305.78
#Sta/Elev= 30
    4051  376.34  4157.8   362.4  4316.3   345.3  4487.6  331.21  4606.8  324.68
  4677.2  322.27  4728.3  325.28  4877.4  326.97  4940.6  324.44  4990.2  320.12
    4993  319.62  4996.2  320.12  5351.4  320.57  5825.5  324.44  6331.1  328.75
  6522.8  332.71  6621.2  336.65  6774.7   338.5  6856.8  342.19  6906.3  341.03
  6996.1  344.79  7004.6  347.18  7040.7  346.17  7076.1  347.19  7086.7   350.6
  7150.6  354.16  7196.4  356.84  7260.5  364.52  7381.7   377.2  7451.1  386.81
#Mann= 6 ,-1 , 0
    4051     .12       0  4990.2     .07       0  4996.2     .12       0
  7040.7     .16       0  7150.6     .12       0  7260.5     .16       0
Bank Sta=4606.8,5825.5
XS Rating Curve= 0 ,0
Exp/Cntr=0.3,0.1

Type RM Length L Ch R = 1 ,15670   ,167,167,167
BEGIN DESCRIPTION:
Mapping XS 9fc40299
END DESCRIPTION:
XS GIS Cut Line= 3
      3647477.25     10587782.34      3646920.59     10585856.76
      3647198.91     10584919.54
#Sta/Elev= 30
  4145.1  364.38    4418  336.82  4594.9  324.77  4667.8  321.98  4771.9  323.94
  4839.2  323.36  4872.8  320.62  4942.2   319.9    4945   319.4  4948.2   319.9
    5105  321.33  5250.7  320.31  5558.4  320.87  5646.3  322.37  5703.3  321.42
  5920.6  324.29  6549.5  328.95    6824   332.3  6873.3  335.49  6901.8  337.71
  6940.2  344.68  6980.5  344.12  7011.8  359.83  7022.2  360.95  7049.8  369.23
  7063.9  372.46  7075.6  377.58  7078.3   379.7  7084.8  381.28  7127.2   387.2
#Mann= 7 ,-1 , 0
  4145.1     .12       0  4942.2     .07       0  4948.2     .12       0
  6549.5     .05       0  6873.3     .08       0  7049.8     .16       0
  7075.6     .12       0
Bank Sta=4594.9,5920.6
XS Rating Curve= 0 ,0
Exp/Cntr=0.3,0.1

Type RM Length L Ch R = 1 ,15503   ,399,399,399
BEGIN DESCRIPTION:
HOLLY BRANCH 16.0
END DESCRIPTION:
XS GIS Cut Line= 3
      3647549.61     10587710.21      3647399.61     10586910.19
      3647614.76     10585909.01
#Sta/Elev= 30
  4212.9  359.29  4446.9  336.56  4609.7  324.53  4711.5  320.04  4911.9  319.33
  4914.7  318.83  4917.9  319.33  5221.2  320.05    5303   325.2  5374.6  326.52
  5386.9  330.08  5425.8  332.13  5436.3  334.32  5475.4  332.53  5548.5  336.09
  5574.2  333.99  5594.5  338.76  5623.5  341.98    5661  350.64  5667.8  354.55
  5819.6  382.92  5860.1   384.1  5904.4  380.43  5909.5  383.49    5927  383.92
  5953.8  381.62  5961.1     385    5998  386.39  6047.4  390.87  6050.9  393.09
#Mann= 6 ,-1 , 0
  4212.9     .16       0  4911.9     .07       0  4917.9     .16       0
  5425.8     .05       0  5594.5     .12       0  5961.1     .16       0
Bank Sta=4609.7,5303
XS Rating Curve= 0 ,0
Exp/Cntr=0.3,0.1

Type RM Length L Ch R = 1 ,15104   ,410,410,410
BEGIN DESCRIPTION:
HOLLY BRANCH 15.0
END DESCRIPTION:
XS GIS Cut Line= 3
      3647549.61      10587910.2      3647749.61     10587110.19
      3647721.27     10585957.87
#Sta/Elev= 30
  4162.1  384.69  4185.3  381.59    4193  378.78  4262.6  370.01  4399.2  357.89
  4656.9   327.7  4708.4  324.32  4762.5  319.67  4960.5  319.25  4963.3  318.75
  4966.5  319.25  5116.8  319.72  5176.8   321.1  5216.8  324.82  5256.8  325.34
  5286.8  328.36  5346.8  338.62  5416.9  347.21  5446.9     354  5466.9  357.43
  5599.4  357.42  5676.9   346.3    5727   346.2    5817  352.89  5930.1  364.79
  5958.6  371.26  6030.6     393  6077.1  404.87  6097.1  406.96  6139.4  407.04
#Mann= 7 ,-1 , 0
  4162.1     .16       0  4960.5     .07       0  4966.5     .16       0
  5446.9     .05       0  5930.1     .16       0  5958.6     .12       0
  6030.6     .16       0
#XS Ineff= 1 ,-1
 4568.18 4825.28335.4373
Permanent Ineff=
       F
Bank Sta=4708.4,5216.8
XS Rating Curve= 0 ,0
Exp/Cntr=0.3,0.1

Type RM Length L Ch R = 1 ,14694   ,493,493,493
BEGIN DESCRIPTION:
HOLLY BRANCH 14.0
END DESCRIPTION:
XS GIS Cut Line= 3
       3648340.9     10587459.52      3647926.87     10586709.41
      3647834.72     10585965.08
#Sta/Elev= 30
  4436.3  342.99  4488.8  346.69  4543.1  346.39  4577.8  341.37    4592  336.99
  4606.9  336.68  4673.3  326.14  4709.7  322.01  4760.4  319.97    4820   321.9
  4982.7  319.44  4992.2  316.17    4995  315.67  4998.2  316.17  5018.1  319.46
  5063.8  321.74  5187.3  338.74  5342.7  352.78  5395.5  354.25  5552.5   337.9
  5685.3   343.7  5734.9  349.18  5834.2  363.47  5866.7  371.99  5881.5  372.05
  5886.8   375.6  5937.2  384.37  5962.5   392.3  6032.9   397.1  6043.1  397.35
#Mann= 10 ,-1 , 0
  4436.3     .12       0  4543.1     .16       0  4577.8     .12       0
  4673.3     .16       0  4992.2     .07       0  4998.2     .16       0
  5187.3     .05       0  5734.9     .16       0  5834.2     .12       0
  6032.9     .16       0
#XS Ineff= 2 ,-1
 4569.77 4967.61  330.93 5019.77 5169.09  329.78
Permanent Ineff=
       F       F
Bank Sta=4709.7,5063.8
XS Rating Curve= 0 ,0
Exp/Cntr=0.3,0.1

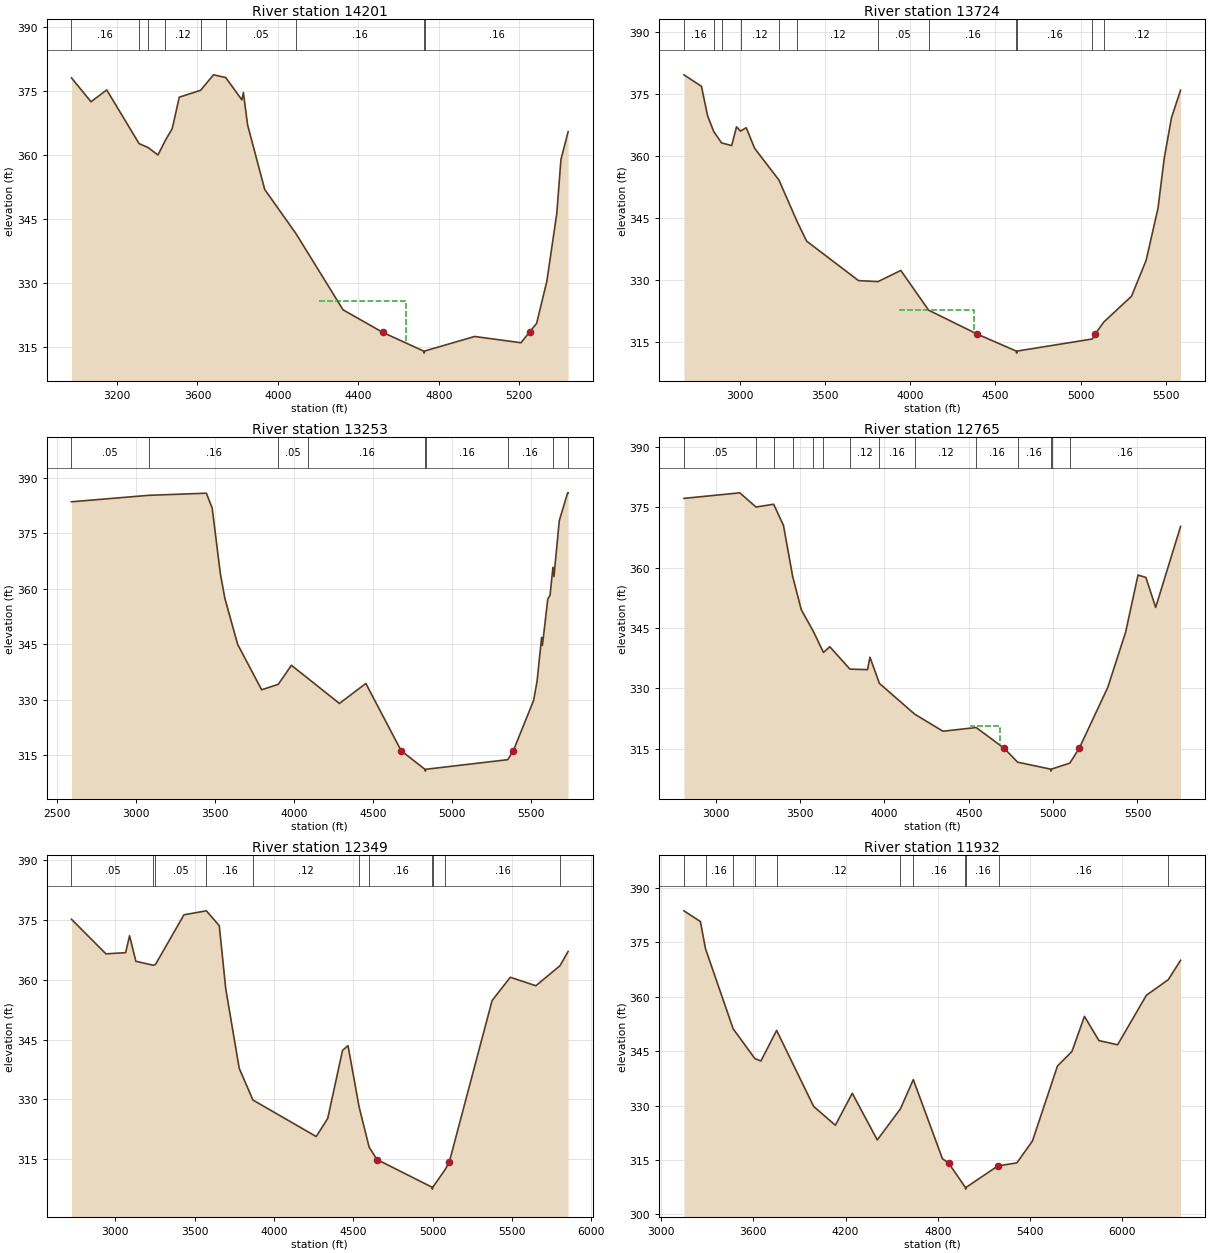
Type RM Length L Ch R = 1 ,14201   ,477,477,477
BEGIN DESCRIPTION:
HOLLY BRANCH 13.0
END DESCRIPTION:
XS GIS Cut Line= 3
       3649919.1      10588028.1      3648449.61     10586660.19
      3648149.62      10586310.2
#Sta/Elev= 30
    2974  378.14  3071.1  372.55  3149.2  375.32    3310  362.74  3354.8  361.82
  3403.8  360.08  3440.1  363.47  3474.6  366.25  3509.8  373.63  3615.6  375.23
  3679.8  378.86  3740.6  378.23    3821  372.98  3828.4   374.7  3849.4  367.12
  3934.4     352  4090.2  341.63  4323.8   323.8  4521.6   318.5  4723.8  314.15
  4726.6  313.65  4729.8  314.15  4978.2  317.55  5208.3  316.08  5251.1  318.59
  5286.2  320.64  5336.7  330.47  5386.1  346.32  5406.9  359.01  5442.6  365.54
#Mann= 9 ,-1 , 0
    2974     .16       0    3310     .12       0  3354.8     .16       0
  3440.1     .12       0  3615.6     .16       0  3740.6     .05       0
  4090.2     .16       0  4723.8     .07       0  4729.8     .16       0
#XS Ineff= 1 ,-1
 4202.84  4635.8  325.97
Permanent Ineff=
       F
Bank Sta=4521.6,5251.1
XS Rating Curve= 0 ,0
Exp/Cntr=0.3,0.1

Type RM Length L Ch R = 1 ,13724   ,471,471,471
BEGIN DESCRIPTION:
HOLLY BRANCH 12.0
END DESCRIPTION:
XS GIS Cut Line= 3
      3650372.88     10587872.15      3648649.61     10586310.19
      3648099.65      10586110.2
#Sta/Elev= 30
  2673.9  379.62  2776.6  376.83  2812.4  369.71  2848.3   365.9  2894.4  363.12
  2953.6  362.48    2982  367.02  3005.4  365.98  3038.8  366.81  3088.1  361.82
  3230.8  354.12  3339.1   343.9  3392.9  339.33  3697.1  329.76  3811.3  329.51
  3945.1  332.22    4108   322.6  4391.1  316.84  4621.3  312.69    4624  312.19
  4627.3  312.69  5067.8  315.62  5084.8  316.84  5134.3   319.7  5297.6  325.99
  5382.8  334.65  5452.6   347.3  5489.2  359.43  5531.7  369.26  5584.9   375.9
#Mann= 12 ,-1 , 0
  2673.9     .16       0  2848.3     .12       0  2894.4     .16       0
  3005.4     .12       0  3230.8     .16       0  3339.1     .12       0
  3811.3     .05       0    4108     .16       0  4621.3     .07       0
  4627.3     .16       0  5067.8     .16       0  5134.3     .12       0
#XS Ineff= 1 ,-1
 3931.82  4373.3   322.6
Permanent Ineff=
       F
Bank Sta=4391.1,5084.8
XS Rating Curve= 0 ,0
Exp/Cntr=0.3,0.1

Type RM Length L Ch R = 1 ,13253   ,488,488,488
BEGIN DESCRIPTION:
HOLLY BRANCH 11.0
END DESCRIPTION:
XS GIS Cut Line= 3
      3650989.73     10587248.26      3648949.61     10585960.19
      3648249.64      10585760.2
#Sta/Elev= 30
  2594.2  383.57  3081.9  385.31  3447.3  385.89  3483.8  381.89  3535.5  364.16
  3564.1  357.43  3644.9     345  3796.7   332.7  3901.5  334.17    3985  339.32
  4090.6  335.74  4288.6     329  4455.7  334.41  4679.1   316.2  4829.2  311.19
    4832  310.69  4835.2  311.19  5353.3  313.79  5387.8  316.16  5516.5   329.8
  5538.6  335.04  5567.2  346.85  5572.4  344.71  5606.2  357.23  5620.5  358.27
  5638.8  365.85  5645.2  363.33    5679  378.47    5732  385.99  5734.9  385.99
#Mann= 9 ,-1 , 0
  2594.2     .05       0  3081.9     .16       0  3901.5     .05       0
  4090.6     .16       0  4829.2     .07       0  4835.2     .16       0
  5353.3     .16       0  5638.8     .12       0    5732     .16       0
Bank Sta=4679.1,5387.8
XS Rating Curve= 0 ,0
Exp/Cntr=0.3,0.1

Type RM Length L Ch R = 1 ,12765   ,416,416,416
BEGIN DESCRIPTION:
HOLLY BRANCH 10.0
END DESCRIPTION:
XS GIS Cut Line= 3
      3651188.23     10586347.83      3649149.61     10585560.19
       3648430.3     10585319.81
#Sta/Elev= 30
  2811.7  377.16  3142.6  378.54    3239  375.02  3343.4  375.71  3401.7  370.44
    3456  357.82    3507  349.56  3579.6  344.09  3638.7  338.94  3676.2  340.36
  3795.7   334.8  3899.8  334.67  3914.4  337.76  3970.2  331.26  4179.1  323.64
  4346.9  319.39    4544  320.31  4709.5  315.17  4789.5  311.71  4984.6  309.99
  4987.3  309.49  4990.6  309.99    5099  311.48  5155.3   315.2  5323.6  330.23
  5429.5  343.92  5503.3  358.14    5550  357.55  5607.9  350.11  5755.6  370.19
#Mann= 14 ,-1 , 0
  2811.7     .05       0    3239     .16       0  3343.4     .12       0
    3456     .16       0  3579.6     .12       0  3638.7     .16       0
  3795.7     .12       0  3970.2     .16       0  4179.1     .12       0
    4544     .16       0  4789.5     .16       0  4984.6     .07       0
  4990.6     .16       0    5099     .16       0
#XS Ineff= 1 ,-1
  4512.5 4685.51  320.68
Permanent Ineff=
       F
Bank Sta=4709.5,5155.3
XS Rating Curve= 0 ,0
Exp/Cntr=0.3,0.1

Type RM Length L Ch R = 1 ,12349   ,417,417,417
BEGIN DESCRIPTION:
HOLLY BRANCH 9.0
END DESCRIPTION:
XS GIS Cut Line= 3
      3651478.95     10585780.65      3649096.71     10585135.46
      3648437.37     10585206.35
#Sta/Elev= 30
  2723.4  375.21  2940.5  366.53  3064.6  366.83  3089.5  371.07  3129.4  364.66
  3239.5  363.67  3252.8  363.86  3432.6  376.34    3574  377.33  3655.1   373.6
    3696  357.75  3780.9   337.8  3867.4  329.84  4266.4  320.68  4338.9  325.23
  4432.4  342.33    4467  343.47  4536.5  328.17  4600.2  317.99  4649.7  314.91
    4996  307.98  4998.8  307.48    5002  307.98  5080.3  312.46  5105.6  314.32
  5375.3  354.82  5490.3  360.65  5651.2  358.53  5802.7  363.53  5854.6  367.13
#Mann= 11 ,-1 , 0
  2723.4     .05       0  3239.5     .16       0  3252.8     .05       0
    3574     .16       0  3867.4     .12       0  4536.5     .16       0
  4600.2     .16       0    4996     .07       0    5002     .16       0
  5080.3     .16       0  5802.7     .12       0
Bank Sta=4649.7,5105.6
XS Rating Curve= 0 ,0
Exp/Cntr=0.3,0.1

Type RM Length L Ch R = 1 ,11932   ,516,516,516
BEGIN DESCRIPTION:
HOLLY BRANCH 8.0
END DESCRIPTION:
XS GIS Cut Line= 3
      3651365.51     10585128.37      3649101.11      10584809.7
      3648233.17     10585184.47
#Sta/Elev= 30
  3148.4  383.71  3255.3  380.76  3288.9  373.22  3468.9  351.15  3610.3  342.94
  3649.2  342.29  3751.5  350.72  3992.5  329.76  4133.9  324.57  4243.8  333.39
  4406.6  320.51  4557.6  329.12    4641  337.16  4830.7  315.33  4871.1  314.14
  4979.2  307.45  4981.9  306.95  4985.2  307.45  5194.3  313.43  5196.4  313.39
  5315.4   314.2  5416.4  320.23  5579.4  340.92  5673.5  344.91  5754.9  354.61
  5848.9  347.93  5970.5  346.76  6158.2  360.43  6300.4  364.72  6380.5  370.07
#Mann= 11 ,-1 , 0
  3148.4     .05       0  3288.9     .16       0  3468.9     .12       0
  3610.3     .16       0  3751.5     .12       0  4557.6     .16       0
    4641     .16       0  4979.2     .07       0  4985.2     .16       0
  5196.4     .16       0  6300.4     .12       0
Bank Sta=4871.1,5194.3
XS Rating Curve= 0 ,0
Exp/Cntr=0.3,0.1

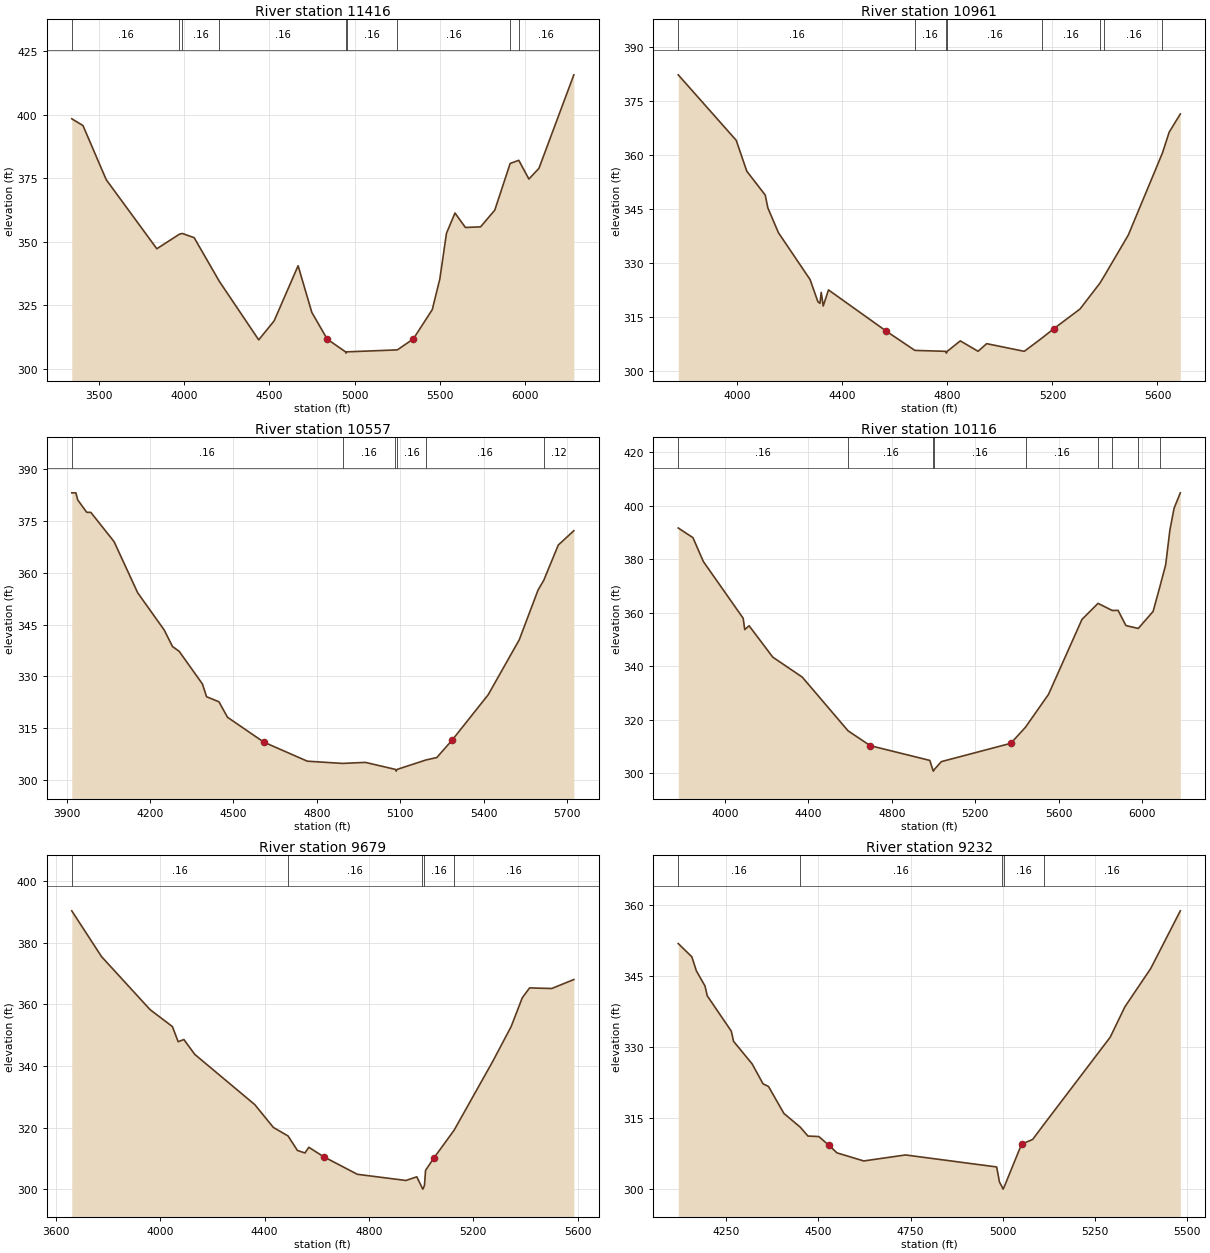
Type RM Length L Ch R = 1 ,11416   ,455,455,455
BEGIN DESCRIPTION:
HOLLY BRANCH 7.0
END DESCRIPTION:
XS GIS Cut Line= 3
      3651230.79     10584561.18      3649599.61     10584410.19
      3648437.31     10583816.72
#Sta/Elev= 30
  3341.1  398.35  3406.8  395.68  3543.1  374.42  3839.7  347.29  3972.2  353.01
  3989.5  353.29  4058.7  351.64  4206.2  334.48    4437   311.5  4527.3  318.95
  4667.9  340.61  4748.3   322.3  4838.7  311.78  4946.1  306.79  4948.9  306.29
  4952.1  306.79  5249.5  307.56  5343.1  311.85  5454.3  323.37  5498.7  335.41
  5537.5  353.34  5587.6  361.33  5648.6  355.65  5737.5  355.89  5820.8  362.46
    5911  380.79  5961.5  382.03  6020.8  374.68  6079.6  378.86  6284.3  415.61
#Mann= 9 ,-1 , 0
  3341.1     .16       0  3972.2     .12       0  3989.5     .16       0
  4206.2     .16       0  4946.1     .07       0  4952.1     .16       0
  5249.5     .16       0    5911     .12       0  5961.5     .16       0
#XS Ineff= 1 ,-1
 4135.51 4674.43  337.72
Permanent Ineff=
       F
Bank Sta=4838.7,5343.1
XS Rating Curve= 0 ,0
Exp/Cntr=0.3,0.1

Type RM Length L Ch R = 1 ,10961   ,404,404,404
BEGIN DESCRIPTION:
HOLLY BRANCH 6.0
END DESCRIPTION:
XS GIS Cut Line= 3
      3650999.65     10584110.19      3649799.61     10584010.19
      3649299.61     10583510.19
#Sta/Elev= 30
  3775.7  382.16  3996.5  363.97  4036.6  355.41  4106.9  348.77  4116.9   345.2
  4157.1  338.33  4277.5  325.32  4307.6  319.12  4315.1   318.7  4320.1  321.75
  4327.6  317.96  4347.7  322.43  4568.5  310.94  4676.5  305.64  4793.8  305.38
  4796.5  304.88  4799.8  305.38  4849.4  308.28  4917.2  305.39  4949.8  307.51
    5093  305.38  5158.9  308.98  5206.2  311.71  5305.2  317.13  5380.7  324.29
  5398.3   326.4    5489  337.67  5619.1  360.48  5644.6  366.23    5687  371.29
#Mann= 8 ,-1 , 0
  3775.7     .16       0  4676.5     .16       0  4793.8     .07       0
  4799.8     .16       0  5158.9     .16       0  5380.7     .12       0
  5398.3     .16       0  5619.1     .12       0
Bank Sta=4568.5,5206.2
XS Rating Curve= 0 ,0
Exp/Cntr=0.3,0.1

Type RM Length L Ch R = 1 ,10557   ,441,441,441
BEGIN DESCRIPTION:
HOLLY BRANCH 5.0
END DESCRIPTION:
XS GIS Cut Line= 3
      3650999.57     10584060.17      3649999.61     10583660.19
      3649299.61     10583460.19
#Sta/Elev= 30
  3918.8  383.13  3933.6  383.12  3940.3  381.07  3972.6   377.5  3987.4  377.47
  4070.9  369.01  4155.7  354.23  4251.3  343.42  4280.9  338.67  4305.1  337.26
  4388.6  327.82  4403.4  324.14  4447.8  322.68  4478.8  318.19  4609.4  310.99
  4765.6  305.49  4892.4  304.84  4974.2  305.14  5082.5  303.11  5085.2  302.61
  5088.5  303.11  5192.3  305.84  5231.1  306.54    5287  311.66  5415.7  324.69
  5527.5   340.6  5595.1     355  5615.5   357.8  5667.9  368.03  5723.8  372.17
#Mann= 6 ,-1 , 0
  3918.8     .16       0  4892.4     .16       0  5082.5     .07       0
  5088.5     .16       0  5192.3     .16       0  5615.5     .12       0
Bank Sta=4609.4,5287
XS Rating Curve= 0 ,0
Exp/Cntr=0.3,0.1

Type RM Length L Ch R = 1 ,10116   ,437,437,437
BEGIN DESCRIPTION:
HOLLY BRANCH 4.0
END DESCRIPTION:
XS GIS Cut Line= 3
      3651099.61     10584060.19      3650199.61     10583260.19
      3648999.63     10583360.19
#Sta/Elev= 30
  3775.8  391.77  3846.5  388.13  3896.2  379.23  4087.3  357.99  4094.8  353.76
  4115.7  355.19  4229.4  343.45  4370.8  335.98  4590.7  315.87  4696.9  310.34
  4982.5  304.83    4997  301.32  4999.8  300.82    5003  301.32  5037.7  304.37
  5371.3  311.23  5441.6  317.26  5551.9  329.53  5712.5  357.58  5789.5  363.57
  5857.6  360.91  5885.6  360.95  5923.2  355.26  5982.5  354.19  6053.7  360.56
  6085.2  369.55  6113.9  377.99  6133.9  390.85    6154  399.09  6184.1  404.91
#Mann= 9 ,-1 , 0
  3775.8     .16       0  4590.7     .16       0    4997     .07       0
    5003     .16       0  5441.6     .16       0  5789.5     .12       0
  5857.6     .16       0  5982.5     .12       0  6085.2     .16       0
Bank Sta=4696.9,5371.3
XS Rating Curve= 0 ,0
Exp/Cntr=0.3,0.1

Type RM Length L Ch R = 1 ,9679    ,447,447,447
BEGIN DESCRIPTION:
HOLLY BRANCH 3.0
END DESCRIPTION:
XS GIS Cut Line= 3
      3651099.62      10584010.2      3650299.61     10582910.19
      3649899.64     10582510.22
#Sta/Elev= 30
  3660.1  390.34  3774.1   375.5  3960.3  358.28  4046.1  352.77  4068.2  347.86
  4090.2  348.56  4131.9  343.74  4362.2  327.43  4433.3  320.03  4489.7  317.26
  4525.7  312.55  4554.6  311.74  4569.3  313.59  4625.7  310.55  4755.6  304.81
  4941.8  302.81  4983.5     304  5003.7   300.5  5006.5     300  5009.7   300.5
  5012.9  301.24  5017.2  306.11  5048.5  310.04  5126.8  319.15  5274.8  341.46
  5345.5  352.79    5388   362.1  5416.2  365.32  5501.1  365.12  5585.9  368.04
#Mann= 5 ,-1 , 0
  3660.1     .16       0  4489.7     .16       0  5003.7     .07       0
  5009.7     .16       0  5126.8     .16       0
Bank Sta=4625.7,5048.5
XS Rating Curve= 0 ,0
Exp/Cntr=0.3,0.1

Type RM Length L Ch R = 1 ,9232    ,445,445,445
BEGIN DESCRIPTION:
HOLLY BRANCH 2.0
END DESCRIPTION:
XS GIS Cut Line= 3
       3651249.6     10583060.18      3650549.61     10582560.19
      3650049.62     10582560.19
#Sta/Elev= 30
  4120.6  351.89  4157.5  349.08  4169.7  346.12  4193.1  342.91  4199.2  340.84
  4264.4  333.35  4270.5  331.21  4320.9  326.42  4350.4  322.21  4365.1  321.66
  4406.9  315.95  4451.2  313.05    4472  311.17  4501.5  311.06  4528.6  309.23
  4550.7  307.61  4623.2   305.9  4736.3  307.17  4983.3  304.63  4990.8  301.47
  4997.8  300.44  5000.6  299.94  5003.8  300.44  5050.8  309.45  5080.8  310.45
  5110.6  313.56  5290.8  332.07  5330.8  338.52  5400.8  346.63  5480.8  358.81
#Mann= 5 ,-1 , 0
  4120.6     .16       0  4451.2     .16       0  4997.8     .07       0
  5003.8     .16       0  5110.6     .16       0
Bank Sta=4528.6,5050.8
XS Rating Curve= 0 ,0
Exp/Cntr=0.3,0.1