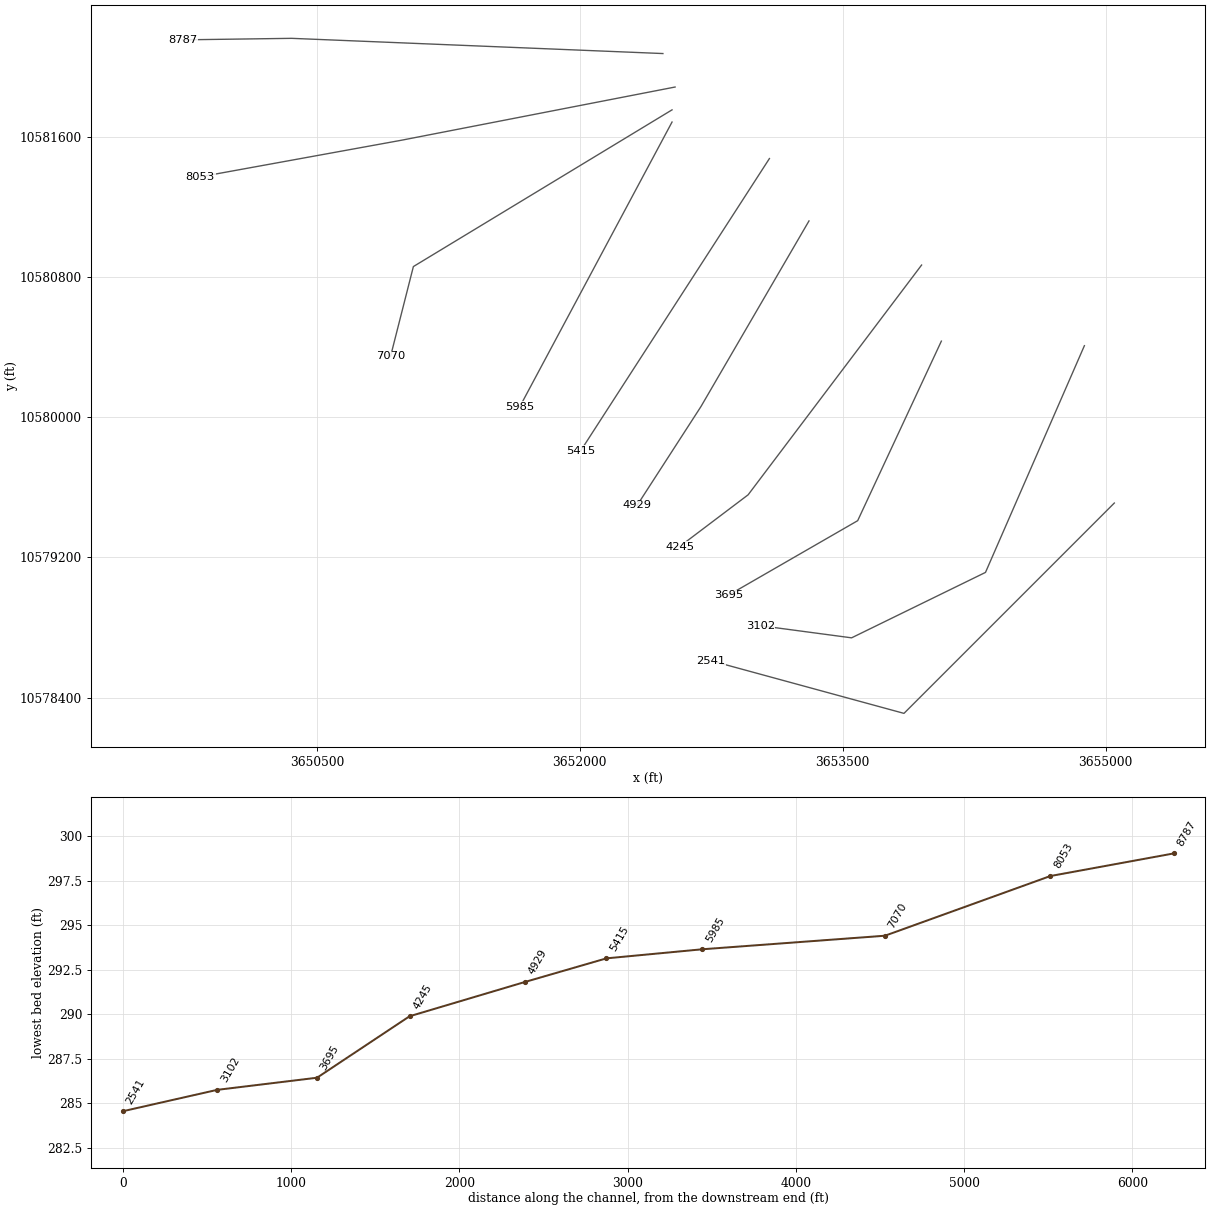
HEC-RAS study HOLLY BRANCH.prj: HOLLY BRANCH Base Level Engineering

--- HOLLY BRANCH.g01 (geometry) --- (continued)

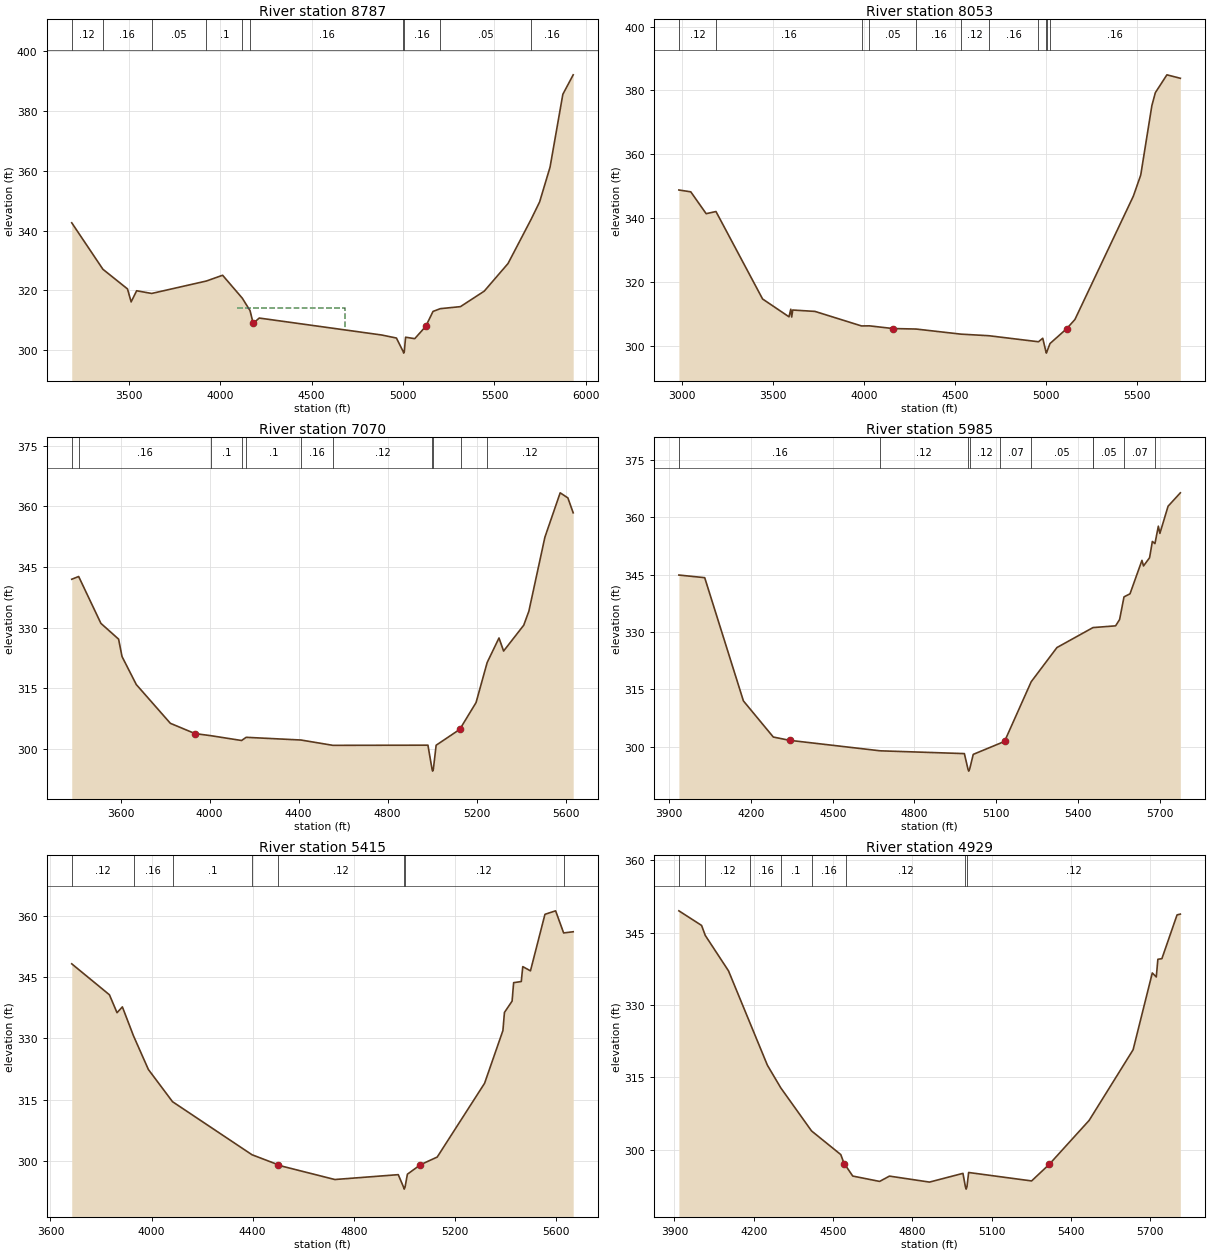
Type RM Length L Ch R = 1 ,8787    ,734,734,734
BEGIN DESCRIPTION:
Mapping XS a6f38158
END DESCRIPTION:
XS GIS Cut Line= 3
      3652474.36     10582074.46      3650356.32     10582161.27
      3649732.99     10582152.61
#Sta/Elev= 30
  3187.6  342.65  3358.1   327.1  3492.6  320.52  3512.6  316.17  3542.6   319.9
    3625     319  3924.7  323.17    4013  325.09  4120.7  317.41  4163.2  313.23
  4180.2  308.99  4213.2  310.77  4883.8  305.09  4963.8  304.08  5000.9  299.53
  5003.6  299.03  5006.9  299.53  5013.9  304.36  5063.9  303.87    5124  307.97
    5164  312.99    5204  313.91  5314.1  314.59  5444.1  319.77  5574.2  329.01
  5700.6  343.81  5747.1  349.63  5804.2  361.28  5874.2  385.66  5930.8  392.17
#Mann= 10 ,-1 , 0
  3187.6     .12       0  3358.1     .16       0    3625     .05       0
  3924.7      .1       0  4120.7     .12       0  4163.2     .16       0
  5000.9     .07       0  5006.9     .16       0    5204     .05       0
  5700.6     .16       0
#XS Ineff= 1 ,-1
  4089.2 4684.09  314.07
Permanent Ineff=
       F
Bank Sta=4180.2,5124
XS Rating Curve= 0 ,0
Exp/Cntr=0.3,0.1

Type RM Length L Ch R = 1 ,8053    ,983,983,983
BEGIN DESCRIPTION:
Mapping XS a304c5b6
END DESCRIPTION:
XS GIS Cut Line= 3
      3652543.81     10581883.49      3650981.32     10581579.67
      3649835.46     10581371.33
#Sta/Elev= 30
  2981.8  348.83  3047.2  348.25  3131.9  341.41  3185.7  342.09  3441.9  314.71
  3587.1  309.13  3596.9  311.51    3602  309.06  3607.5  311.25  3729.8  310.82
  3985.7  306.27  4029.2   306.3  4157.6  305.46  4285.6   305.3  4532.8   303.7
  4685.4  303.21  4958.4  301.32  4981.9  302.42  4999.2  298.26  5001.9  297.76
  5005.2  298.26  5021.6  300.75    5114  305.44  5158.7  308.28  5479.9   346.9
  5520.5  353.51  5581.5  375.19  5600.8  379.29  5664.3  384.88  5738.2   383.8
#Mann= 11 ,-1 , 0
  2981.8     .12       0  3185.7     .16       0  3985.7      .1       0
  4029.2     .05       0  4285.6     .16       0  4532.8     .12       0
  4685.4     .16       0  4958.4     .12       0  4999.2     .07       0
  5005.2     .12       0  5021.6     .16       0
Bank Sta=4157.6,5114
XS Rating Curve= 0 ,0
Exp/Cntr=0.3,0.1

Type RM Length L Ch R = 1 ,7070    ,1085,1085,1085
BEGIN DESCRIPTION:
Mapping XS 5322d1ab
END DESCRIPTION:
XS GIS Cut Line= 3
      3652526.46     10581753.28      3651050.76     10580859.18
      3650920.55     10580347.01
#Sta/Elev= 30
  3380.5  341.96  3411.6  342.64  3511.6  331.03  3591.1  327.12  3606.6   322.8
  3670.6  315.87  3823.8  306.26  3934.3  303.72  4006.2  303.19  4143.9     302
  4164.5  302.79  4410.8  302.12  4554.1   300.8  4981.5  300.84  4999.9  294.91
  5002.6  294.41  5005.9  294.91  5018.4  300.83  5125.5  304.79  5128.8  305.15
  5197.8   311.4  5247.8  321.34  5300.9  327.41  5321.6  324.17  5412.1  330.57
  5435.1  334.03  5507.3   352.4  5575.9  363.38  5610.5  362.12  5634.4  358.43
#Mann= 11 ,-1 , 0
  3380.5     .12       0  3411.6     .16       0  4006.2      .1       0
  4143.9     .16       0  4164.5      .1       0  4410.8     .16       0
  4554.1     .12       0  4999.9     .07       0  5005.9     .12       0
  5128.8     .07       0  5247.8     .12       0
Bank Sta=3934.3,5125.5
XS Rating Curve= 0 ,0
Exp/Cntr=0.3,0.1

Type RM Length L Ch R = 1 ,5985    ,570,570,570
BEGIN DESCRIPTION:
Mapping XS cc63a958
END DESCRIPTION:
XS GIS Cut Line= 2
      3652526.44     10581683.81      3651658.38     10580060.54
#Sta/Elev= 30
  3935.3   344.9  4030.1  344.21  4172.2     312  4281.9  302.56    4342   301.7
  4674.2  298.96  4983.3  298.23  4996.6  294.15  4999.3  293.65  5002.6  294.15
  5015.9  298.03    5115  300.95  5131.3   301.5  5228.6  317.01  5323.1  325.95
  5455.7  331.18  5457.1  331.18  5538.4  331.62  5553.1  333.27  5569.3  339.19
  5591.3  339.99  5635.2  348.74  5640.9  347.28  5663.1  349.42  5673.4  353.68
  5682.9  353.12  5695.4  357.67    5701  355.79  5731.1  362.89  5776.1  366.39
#Mann= 10 ,-1 , 0
  3935.3     .16       0  4674.2     .12       0  4996.6     .07       0
  5002.6     .12       0    5115     .07       0  5228.6     .05       0
  5455.7     .12       0  5457.1     .05       0  5569.3     .07       0
  5682.9     .12       0
Bank Sta=4342,5131.3
XS Rating Curve= 0 ,0
Exp/Cntr=0.3,0.1

Type RM Length L Ch R = 1 ,5415    ,486,486,486
BEGIN DESCRIPTION:
Mapping XS afe856d2
END DESCRIPTION:
XS GIS Cut Line= 2
        3653082.     10581475.47      3652005.62     10579808.84
#Sta/Elev= 30
  3684.1  348.27  3833.2   340.7  3863.3  336.31  3884.4  337.74  3928.5  330.64
  3987.3  322.42  4082.9  314.53  4397.4  301.55  4498.5  299.16  4499.9  299.01
    4725  295.49    4976  296.68  4996.9  293.64  4999.6  293.14  5002.9  293.64
  5012.1  296.79  5063.5   299.1  5130.1  300.99  5317.5  319.04  5390.1  331.95
  5396.1  336.38  5426.4  339.15  5432.4  343.66  5462.7  343.94  5468.6  347.59
    5499  346.55  5556.4  360.39  5598.6  361.24  5630.3  355.83  5668.1  356.12
#Mann= 8 ,-1 , 0
  3684.1     .12       0  3928.5     .16       0  4082.9      .1       0
  4397.4     .16       0  4498.5     .12       0  4996.9     .07       0
  5002.9     .12       0  5630.3     .16       0
Bank Sta=4499.9,5063.5
XS Rating Curve= 0 ,0
Exp/Cntr=0.3,0.1

Type RM Length L Ch R = 1 ,4929    ,684,684,684
BEGIN DESCRIPTION:
Mapping XS 84510a7a
END DESCRIPTION:
XS GIS Cut Line= 3
      3653307.72     10581119.62      3652691.39     10580060.57
      3652326.81     10579496.35
#Sta/Elev= 30
  3916.8  349.54  4002.7  346.51  4016.7  344.43  4104.5  337.09  4186.5  326.18
  4251.7  317.51  4302.6  312.79  4418.7  303.88  4529.4  298.97    4543  296.93
  4547.2  296.73  4574.5  294.52  4676.2  293.41  4713.5  294.51  4864.9  293.27
  4991.5  295.08  5000.7  292.31  5003.5  291.81  5006.7  292.31    5013  295.26
  5251.2  293.51  5317.8  296.94  5468.9  306.07  5635.2  320.72  5707.8  336.65
  5722.9  335.82  5728.9  339.49  5744.1  339.62  5801.5   348.7  5813.9  348.86
#Mann= 8 ,-1 , 0
  3916.8     .16       0  4016.7     .12       0  4186.5     .16       0
  4302.6      .1       0  4418.7     .16       0  4547.2     .12       0
  5000.7     .07       0  5006.7     .12       0
Bank Sta=4543,5317.8
XS Rating Curve= 0 ,0
Exp/Cntr=0.3,0.1

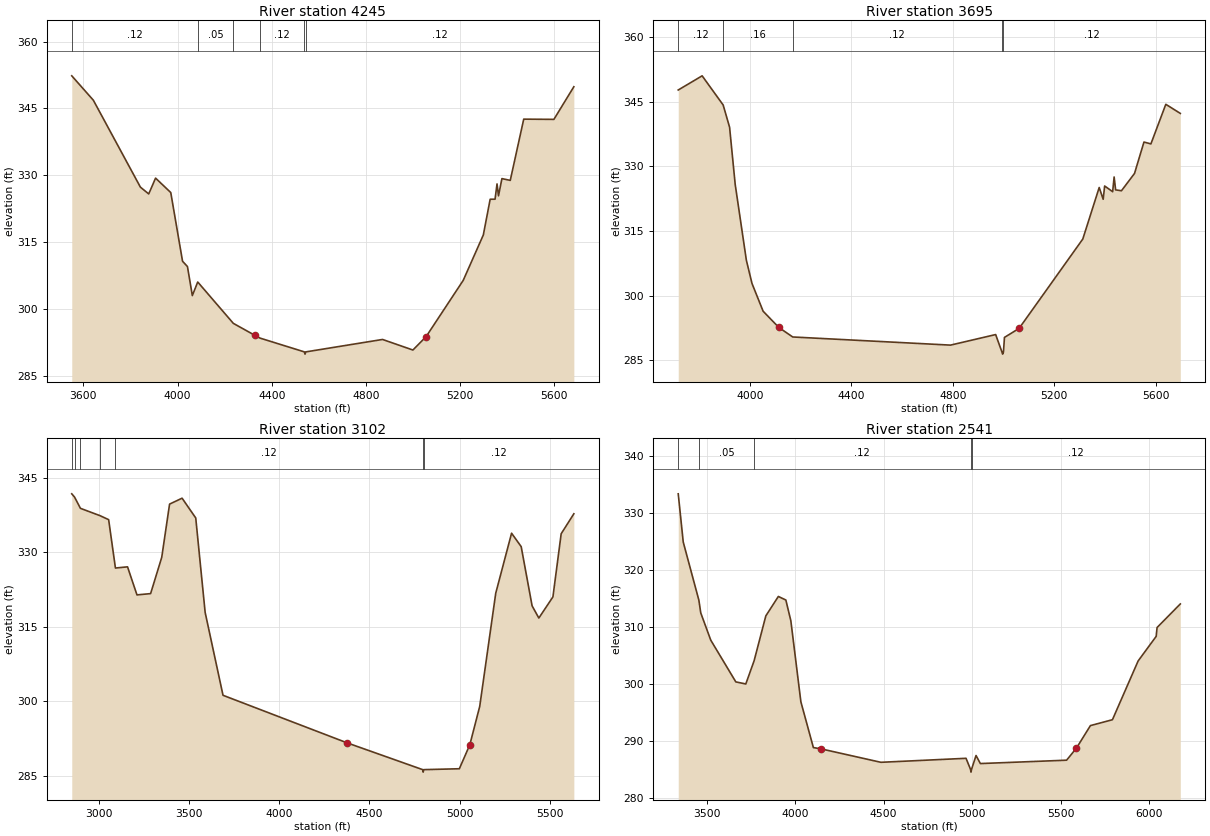
Type RM Length L Ch R = 1 ,4245    ,550,550,550
BEGIN DESCRIPTION:
Mapping XS a22d765a
END DESCRIPTION:
XS GIS Cut Line= 3
      3653950.08     10580867.88      3652960.49      10579557.1
      3652569.85     10579261.95
#Sta/Elev= 30
  3550.8  352.33  3642.4  346.86  3842.2  327.36  3877.6  325.83  3906.7  329.38
  3971.2  326.14  4021.2  310.73    4042  309.54  4062.8  303.03  4085.7  306.07
  4236.9  296.79  4327.2  294.14  4350.6  293.48  4538.6  290.39  4541.3  289.89
  4544.6  290.39  4870.4  293.18  4999.4  290.81  5055.7  293.83    5213  306.43
  5298.4  316.62  5327.5  324.64  5348.3  324.65  5356.6  328.08  5362.9  325.41
  5377.4  329.27  5412.8  328.87    5470  342.61  5598.1  342.56  5682.8  349.88
#Mann= 6 ,-1 , 0
  3550.8     .12       0  4085.7     .05       0  4236.9     .16       0
  4350.6     .12       0  4538.6     .07       0  4544.6     .12       0
Bank Sta=4327.2,5055.7
XS Rating Curve= 0 ,0
Exp/Cntr=0.3,0.1

Type RM Length L Ch R = 1 ,3695    ,593,593,593
BEGIN DESCRIPTION:
Mapping XS 4f651cba
END DESCRIPTION:
XS GIS Cut Line= 3
      3654062.93     10580433.86      3653585.49     10579409.53
       3652848.5     10578984.68
#Sta/Elev= 30
  3716.6  347.74  3810.9  351.03  3893.9  344.26  3919.2  339.09  3941.3  325.84
  3985.4  308.23  4007.5  302.86  4051.6  296.39  4113.7  292.62  4168.3  290.42
  4790.8  288.53  4968.9  290.98  4993.7  286.94  4996.4  286.44  4999.7  286.94
  5003.6  290.32  5061.4  292.41  5312.7  313.15  5377.4  325.11  5393.1  322.38
  5398.9  325.46  5430.5  324.14  5436.3  327.55  5442.2  324.56  5465.3  324.36
  5516.7  328.37    5554  335.66  5581.4  335.23  5640.2  344.42  5697.4  342.31
#Mann= 5 ,-1 , 0
  3716.6     .12       0  3893.9     .16       0  4168.3     .12       0
  4993.7     .07       0  4999.7     .12       0
Bank Sta=4113.7,5061.4
XS Rating Curve= 0 ,0
Exp/Cntr=0.3,0.1

Type RM Length L Ch R = 1 ,3102    ,561,561,561
BEGIN DESCRIPTION:
Mapping XS 7ab2ea2e
END DESCRIPTION:
XS GIS Cut Line= 4
      3654878.89      10580407.8      3654314.65     10579114.39
      3653550.76     10578741.13       3653029.9     10578810.57
#Sta/Elev= 30
  2847.6  341.79  2862.9  341.14  2895.7  338.87  3004.6  337.39  3052.3  336.59
    3090  326.85  3157.2  327.09  3209.5  321.44  3285.2   321.7  3346.9  328.99
  3390.5  339.72    3460  340.91  3535.7  336.93    3588   317.9  3687.1  301.23
    4376  291.65  4795.3  286.26    4798  285.76  4801.3  286.26  4998.9  286.44
  5057.1  291.28    5112  298.99  5200.9  321.78  5288.8  333.86  5342.1  331.16
  5402.7  319.24  5440.1  316.78  5518.3  321.04  5564.1  333.75  5634.4  337.77
#Mann= 7 ,-1 , 0
  2847.6     .16       0  2862.9     .12       0  2895.7     .16       0
  3004.6     .05       0    3090     .12       0  4795.3     .07       0
  4801.3     .12       0
Bank Sta=4376,5057.1
XS Rating Curve= 0 ,0
Exp/Cntr=0.3,0.1

Type RM Length L Ch R = 1 ,2541    ,0,0,0
BEGIN DESCRIPTION:
HOLLY BRANCH 1.0
END DESCRIPTION:
XS GIS Cut Line= 3
      3655049.61     10579510.19      3653849.61     10578310.19
      3652749.64     10578610.18
#Sta/Elev= 30
  3339.1  333.31  3367.4  324.86  3455.7  314.68  3466.4  312.45  3522.9  307.68
  3664.4  300.37  3720.9     300    3768  304.08  3834.1  311.93  3904.8  315.33
  3947.2  314.71  3975.5  311.07  4032.1  296.88  4102.8  288.86  4145.2  288.64
  4484.6  286.28  4965.4  286.98  4990.7  285.06  4993.5  284.56  4996.7  285.06
    5022  287.47  5046.5  286.06  5533.7  286.65    5589  288.75  5668.4  292.71
  5792.8  293.74  5937.9  304.03  6039.9  308.34    6045  309.89  6176.3  314.02
#Mann= 5 ,-1 , 0
  3339.1     .12       0  3455.7     .05       0    3768     .12       0
  4990.7     .07       0  4996.7     .12       0
Bank Sta=4145.2,5589
XS Rating Curve= 0 ,0
Exp/Cntr=0.3,0.1

Chan Stop Cuts=-1
Use User Specified Reach Order=0
Composite Channel Slope=5