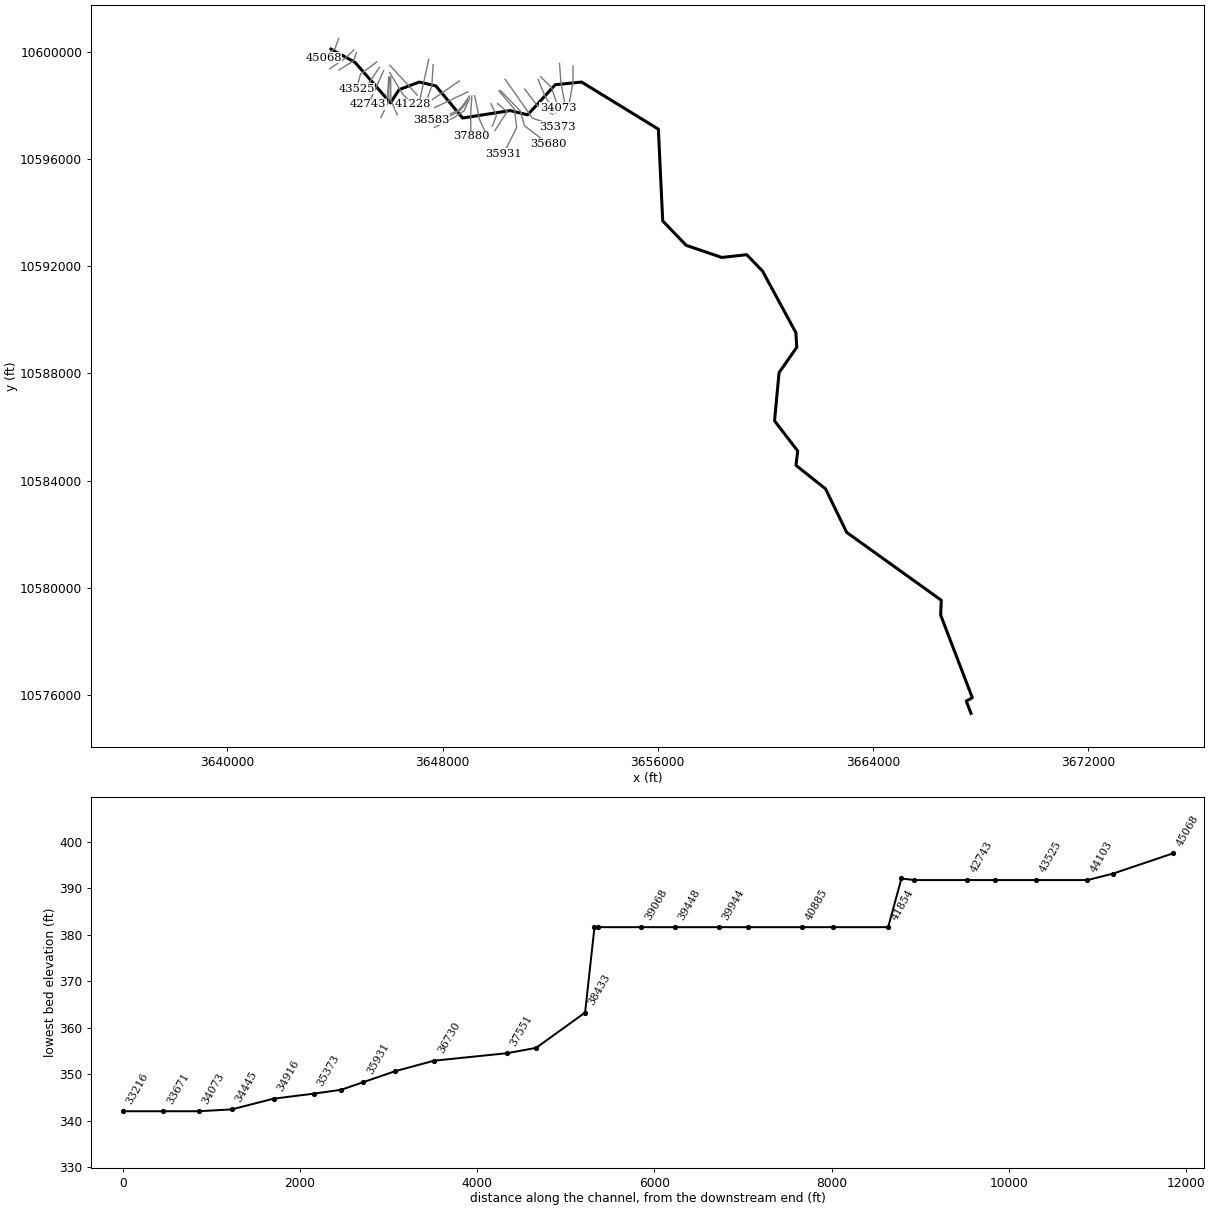
--- JELLY SLOUGH.prj (project) ---

Proj Title=JELLY SLOUGH Base Level Engineering
Current Plan=p01
Default Exp/Contr=0.3,0.1
English Units
Geom File=g01
Flow File=f01
Plan File=p01
Y Axis Title=Elevation
X Axis Title(PF)=Main Channel Distance
X Axis Title(XS)=Station
BEGIN DESCRIPTION:
JELLY SLOUGH
END DESCRIPTION:
DSS Export Rating Curves= 0
DSS Export Rating Curve Sorted= 0
DSS Export Volume Flow Curves= 0
DXF OffsetX= 0
DXF OffsetY= 0
DXF ScaleX= 1
DXF ScaleY= 10

--- JELLY SLOUGH.p01 (plan) ---

Plan Title=Multiple Run
Short Identifier=Multiple
Geom File=g01
Flow File=f01
Subcritical Flow
K Sum by GR= 0
Std Step Tol= 0.01
Critical Tol= 0.01
Num of Std Step Trials= 20
Max Error Tol= 0.3
Flow Tol Ratio= 0.001
Split Flow NTrial= 30
Split Flow Tol= 0.02
Split Flow Ratio= 0.02
Log Output Level= 0
Friction Slope Method= 1
Unsteady Friction Slope Method= 2
Unsteady Bridges Friction Slope Method= 1
Parabolic Critical Depth
Global Vel Dist=  1 , 1 , 1
Global Log Level= 0
CheckData=True
Encroach Param= -1, 0, 0, 0
BEGIN DESCRIPTION:
Multiple Run
END DESCRIPTION:

--- JELLY SLOUGH.f01 (steady flow) ---

Flow Title=Multiple
Program Version=4.10
Number of Profiles= 7
Profile Names=10-year,25-year,50-year,1pct_min,100-year,1pct_plu,500-year
River Rch & RM=JELLY SLOUGH,Reach-1         ,45068
     903    1244    1529    1377    1862    2518    2758
River Rch & RM=JELLY SLOUGH,Reach-1         ,41228
    1102    1535    1900    1723    2330    3151    3511
River Rch & RM=JELLY SLOUGH,Reach-1         ,32239
    1642    2326    2912    2668    3608    4879    5559
River Rch & RM=JELLY SLOUGH,Reach-1         ,26748
    1831    2607    3275    3010    4071    5505    6315
River Rch & RM=JELLY SLOUGH,Reach-1         ,25088
    1953    2784    3501    3218    4352    5886    6760
River Rch & RM=JELLY SLOUGH,Reach-1         ,19213
    2052    2925    3678    3380    4571    6182    7095
River Rch & RM=JELLY SLOUGH,Reach-1         ,13878
    2194    3135    3949    3635    4915    6647    7653
River Rch & RM=JELLY SLOUGH,Reach-1         ,12881
    2306    3300    4162    3835    5186    7014    8094
River Rch & RM=JELLY SLOUGH,Reach-1         ,10130
    2356    3370    4246    3910    5288    7151    8239
River Rch & RM=JELLY SLOUGH,Reach-1         ,5225
    2550    3650    4604    4241    5735    7756    8945
Boundary for River Rch & Prof#=JELLY SLOUGH,Reach-1         , 1
Up Type= 0
Dn Type= 3
Dn Slope=0.002
Boundary for River Rch & Prof#=JELLY SLOUGH,Reach-1         , 2
Up Type= 0
Dn Type= 3
Dn Slope=0.002
Boundary for River Rch & Prof#=JELLY SLOUGH,Reach-1         , 3
Up Type= 0
Dn Type= 3
Dn Slope=0.002
Boundary for River Rch & Prof#=JELLY SLOUGH,Reach-1         , 4
Up Type= 0
Dn Type= 3
Dn Slope=0.002
Boundary for River Rch & Prof#=JELLY SLOUGH,Reach-1         , 5
Up Type= 0
Dn Type= 3
Dn Slope=0.002
Boundary for River Rch & Prof#=JELLY SLOUGH,Reach-1         , 6
Up Type= 0
Dn Type= 3
Dn Slope=0.002
Boundary for River Rch & Prof#=JELLY SLOUGH,Reach-1         , 7
Up Type= 0
Dn Type= 3
Dn Slope=0.002
DSS Import GetInterval= 0
DSS Import GetPeak= 0
DSS Import FillOption= 0

--- JELLY SLOUGH.g01 (geometry) ---

Geom Title=Existing Conditions
Program Version=4.10

River Reach=JELLY SLOUGH    ,Reach-1
Reach XY= 30
        3643852.       10600091.        3644741.       10599600.
        3646064.       10598086.      3646382.75       10598580.
      3647133.25       10598863.       3647749.5       10598720.
      3648745.25       10597522.        3650510.       10597799.
      3651163.75       10597642.        3652189.       10598763.
      3653168.25       10598864.      3656025.25       10597107.
      3656186.25       10593686.       3657059.5       10592776.
      3658384.25       10592323.        3659309.       10592427.
      3659897.25       10591819.      3661138.25       10589521.
        3661172.       10588973.        3660513.       10588029.
      3660345.25       10586233.       3661206.5       10585109.
      3661142.75       10584572.        3662242.       10583697.
       3663027.5       10582074.      3666545.25       10579543.
       3666523.5       10578990.      3667700.25       10575908.
        3667475.       10575782.        3667652.       10575325.

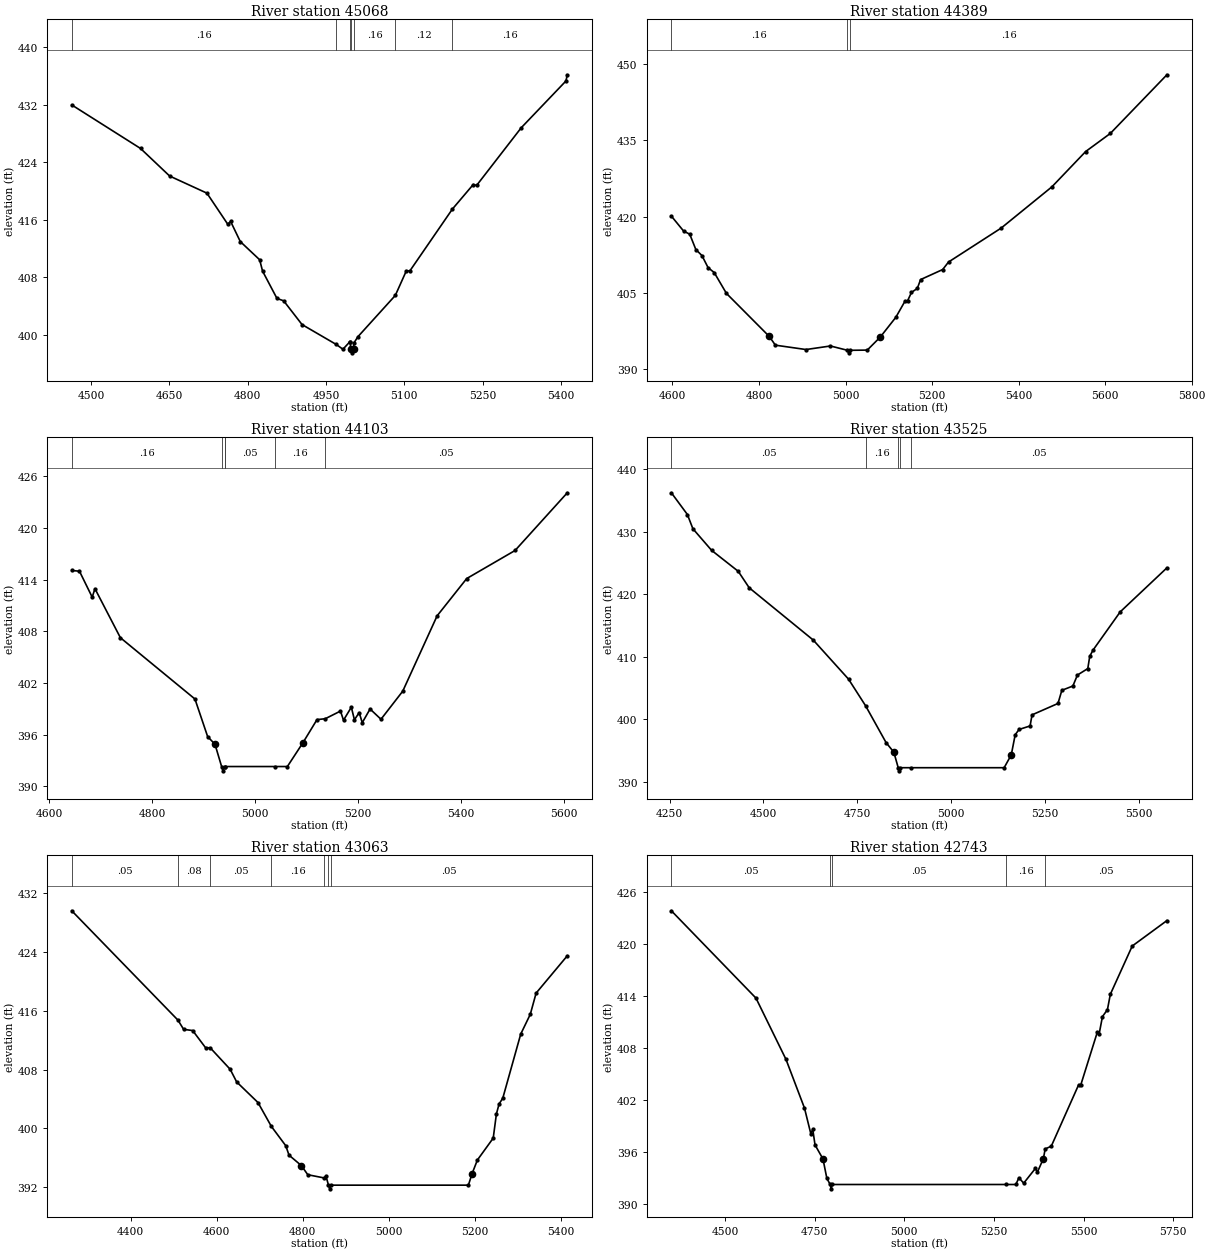
Type RM Length L Ch R = 1 ,45068   ,679,679,679
BEGIN DESCRIPTION:
JELLY SLOUGH 92.0
END DESCRIPTION:
XS GIS Cut Line= 3
      3644138.28     10600493.23      3644002.87     10600123.47
      3643570.99     10599774.84
#Sta/Elev= 30
  4463.3  431.98    4595  425.93  4650.7   422.1  4722.1  419.72  4762.1  415.39
  4767.4   415.8    4786  412.99  4823.1  410.46  4828.6  408.89  4856.2  405.09
    4869  404.76  4904.2  401.46  4969.8  398.69  4982.5  398.03  4995.9  399.08
  4996.9  399.09    4997  398.03  4999.8  397.53    5003  398.03  5003.3  398.88
  5011.3  399.78  5082.8  405.51    5104  408.94  5110.5   408.9  5192.1  417.51
    5232  420.92  5238.4  420.79  5323.9  428.81  5409.5  435.31  5412.1  436.17
#Mann= 7 ,-1 , 0
  4463.3     .16       0  4969.8     .12       0  4995.9     .16       0
    4997     .07       0    5003     .16       0  5082.8     .12       0
  5192.1     .16       0
Bank Sta=4997,5003
XS Rating Curve= 0 ,0
Exp/Cntr=0.3,0.1

Type RM Length L Ch R = 1 ,44389   ,286,286,286
BEGIN DESCRIPTION:
JELLY SLOUGH 91.0
END DESCRIPTION:
XS GIS Cut Line= 3
      3644699.63     10600060.21      3644399.61     10599760.19
      3643799.61     10599360.19
#Sta/Elev= 30
  4597.4   420.1  4625.7  417.15  4639.9  416.53    4654  413.51  4668.1  412.32
  4682.3  409.94  4696.4  408.98  4724.7  404.87  4823.7  396.39  4837.8  394.67
  4908.6  393.81  4965.1  394.51  5004.5  393.66  5007.3  393.16  5010.5  393.66
  5050.2   393.7  5080.3  396.27  5116.3  400.17  5137.4  403.34  5143.4  403.42
  5152.4  405.06  5165.9  405.86  5173.4  407.59  5224.5  409.57    5238  411.05
  5359.7  417.74  5476.9  425.86    5555  432.82  5612.1  436.39  5742.8  447.94
#Mann= 3 ,-1 , 0
  4597.4     .16       0  5004.5     .07       0  5010.5     .16       0
Bank Sta=4823.7,5080.3
XS Rating Curve= 0 ,0
Exp/Cntr=0.3,0.1

Type RM Length L Ch R = 1 ,44103   ,578,578,578
BEGIN DESCRIPTION:
JELLY SLOUGH 90.0
END DESCRIPTION:
XS GIS Cut Line= 3
       3644799.6     10599960.17      3644680.74     10599649.27
       3644149.6     10599310.18
#Sta/Elev= 30
  4643.4  415.06  4658.4  414.97  4683.1  411.96  4688.5  412.94  4737.9  407.25
  4882.8  400.13  4907.5  395.76  4921.7  394.88  4934.6  392.29  4937.4  391.79
  4940.6  392.29  4941.1  392.29  5037.8  392.29  5062.4  392.29  5092.8  395.07
    5120  397.74    5136  397.84  5165.6  398.73  5171.5  397.67  5186.7  399.18
  5192.7  397.72    5202  398.55  5207.9  397.38  5223.1  398.97  5244.3  397.78
  5286.6  401.04  5353.4  409.79  5410.9  414.12  5504.9  417.38  5606.4  424.08
#Mann= 6 ,-1 , 0
  4643.4     .16       0  4934.6     .03       0  4940.6     .16       0
  4941.1     .05       0  5037.8     .16       0    5136     .05       0
Bank Sta=4921.7,5092.8
XS Rating Curve= 0 ,0
Exp/Cntr=0.3,0.1

Type RM Length L Ch R = 1 ,43525   ,462,462,462
BEGIN DESCRIPTION:
JELLY SLOUGH 89.0
END DESCRIPTION:
XS GIS Cut Line= 3
      3645549.62      10599610.2      3644949.61     10599160.19
      3644799.61     10598610.19
#Sta/Elev= 30
  4254.7   436.2  4297.4  432.73    4312  430.46    4362     427  4432.8  423.66
    4462  421.03  4632.8  412.67  4726.6  406.44    4772  402.19  4826.6  396.31
  4847.4  394.76    4859  392.29  4861.8  391.79    4865  392.29  4892.1  392.29
  5141.2  392.29  5160.2  394.35  5170.6  397.55  5180.9   398.4  5210.3  398.96
  5215.5  400.73  5284.6  402.55  5294.9  404.65  5324.3  405.34  5336.4  407.09
    5364  408.12  5369.2  410.08  5377.9  411.07  5450.4  417.18  5574.8  424.21
#Mann= 5 ,-1 , 0
  4254.7     .05       0    4772     .16       0    4859    .033       0
    4865     .16       0  4892.1     .05       0
Bank Sta=4847.4,5160.2
XS Rating Curve= 0 ,0
Exp/Cntr=0.3,0.1

Type RM Length L Ch R = 1 ,43063   ,320,320,320
BEGIN DESCRIPTION:
JELLY SLOUGH 88.0
END DESCRIPTION:
XS GIS Cut Line= 3
      3645649.59     10599410.16      3645249.61     10598810.19
       3644899.6     10598560.18
#Sta/Elev= 30
  4263.4  429.61  4510.2  414.73  4523.3  413.48  4544.3  413.32  4574.3  410.98
  4585.1  410.97  4631.4  408.05  4646.5  406.33    4696  403.53    4727  400.29
  4760.6  397.65  4768.1  396.37  4796.7  394.96  4811.7  393.71    4850  393.27
  4853.8  393.55  4859.8  392.29  4862.5  391.79  4865.8  392.29  5184.8  392.29
  5193.4  393.86  5205.7  395.71  5242.5  398.69  5249.9  401.98  5256.1  403.33
  5264.7  404.12  5306.4  412.84  5328.6  415.53  5342.1  418.41  5414.6  423.49
#Mann= 7 ,-1 , 0
  4263.4     .05       0  4510.2     .08       0  4585.1     .05       0
    4727     .16       0    4850     .05       0  4859.8    .033       0
  4865.8     .05       0
Bank Sta=4796.7,5193.4
XS Rating Curve= 0 ,0
Exp/Cntr=0.3,0.1

Type RM Length L Ch R = 1 ,42743   ,595,595,595
BEGIN DESCRIPTION:
JELLY SLOUGH 87.0
END DESCRIPTION:
XS GIS Cut Line= 2
      3645807.72     10599285.09      3645234.81     10598026.44
#Sta/Elev= 30
  4349.8  423.82  4585.9  413.76  4669.7   406.7  4721.3  401.09  4738.9  398.15
  4744.4  398.64  4750.7  396.85  4772.9  395.23  4783.7     393    4793  392.29
  4795.7  391.79    4799  392.29  5283.3  392.29  5311.1  392.29  5319.7  393.07
    5333  392.44  5365.8  394.15  5371.3  393.71    5388  395.28    5393  396.39
    5410   396.7  5486.6   403.8  5492.1  403.73  5538.2   409.8  5543.7  409.66
  5552.8  411.63  5566.7  412.43  5574.8   414.2  5635.9  419.76  5732.7  422.69
#Mann= 5 ,-1 , 0
  4349.8     .05       0    4793    .033       0    4799     .05       0
  5283.3     .16       0    5393     .05       0
Bank Sta=4772.9,5388
XS Rating Curve= 0 ,0
Exp/Cntr=0.3,0.1

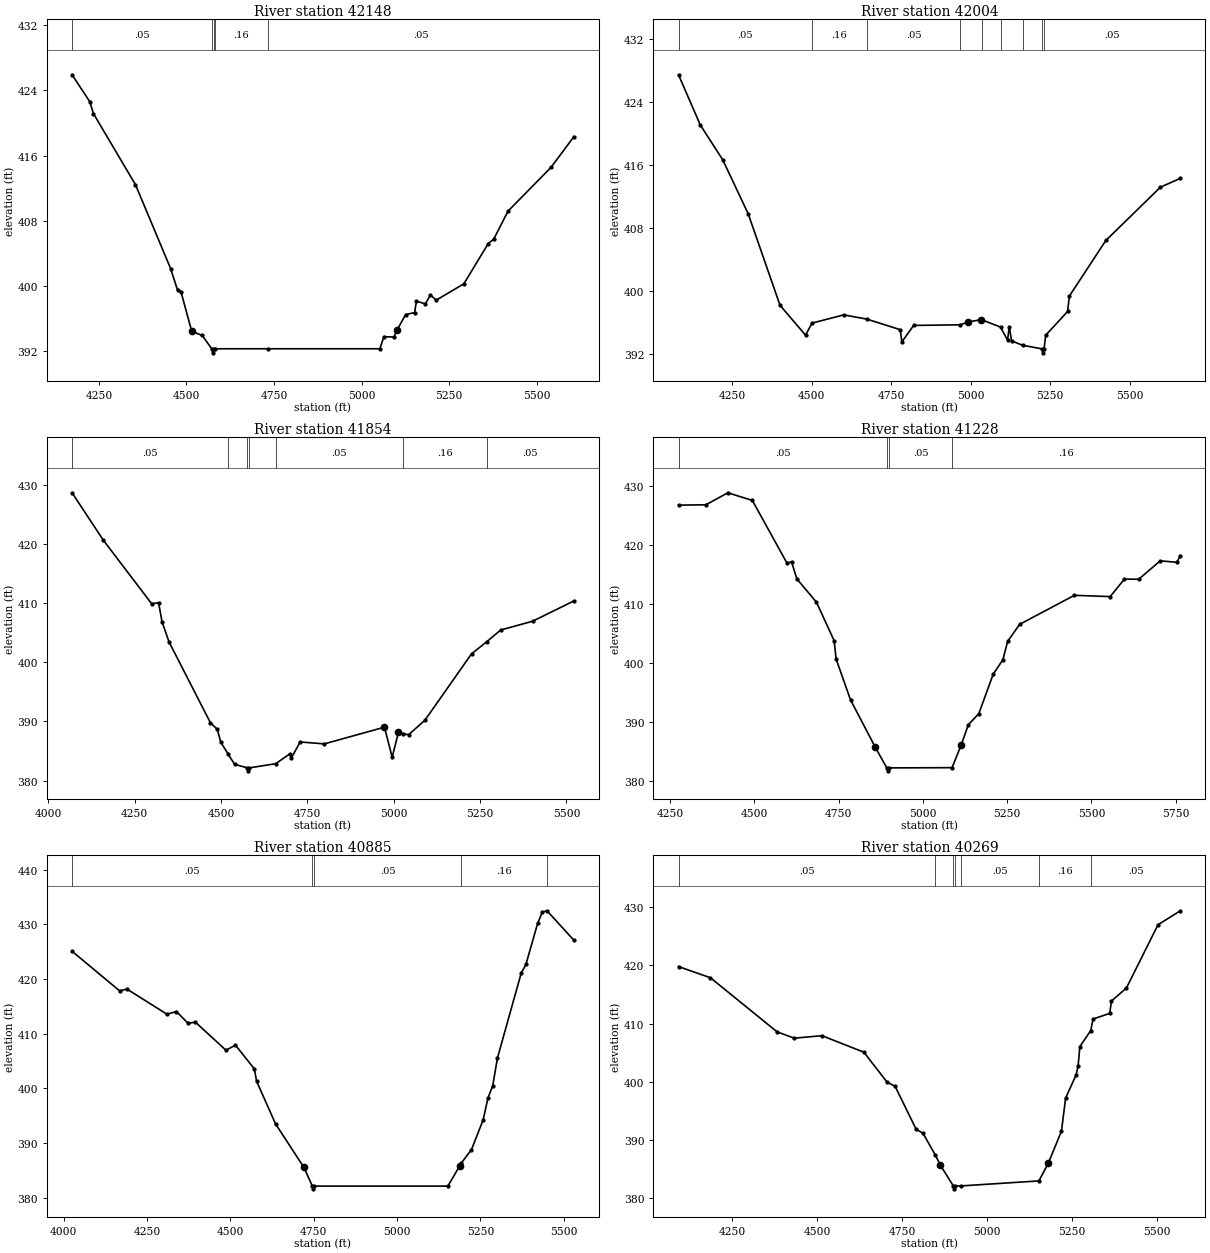
Type RM Length L Ch R = 1 ,42148   ,144,144,144
BEGIN DESCRIPTION:
JELLY SLOUGH 86.0
END DESCRIPTION:
XS GIS Cut Line= 4
      3645998.69     10599050.72       3645946.6     10598330.22
       3645859.8     10598156.61      3645374.12     10597983.15
#Sta/Elev= 30
  4173.6  425.92  4224.3  422.61  4234.7  421.15  4354.6  412.43  4454.9  402.13
  4474.9  399.46  4484.9  399.21    4515  394.45  4545.1  393.92  4572.2  392.29
  4574.9  391.79  4578.2  392.29  4580.6  392.29  4731.4  392.29    5052  392.29
  5063.7  393.77  5092.2  393.73  5100.9  394.57  5125.7  396.49  5151.2  396.73
  5156.5  398.14    5182   397.8  5196.5   398.9  5212.8  398.25    5292  400.27
  5361.5  405.21    5377  405.74  5417.8  409.18  5540.9  414.57  5605.8  418.32
#Mann= 5 ,-1 , 0
  4173.6     .05       0  4572.2    .033       0  4578.2     .05       0
  4580.6     .16       0  4731.4     .05       0
Bank Sta=4515,5100.9
XS Rating Curve= 0 ,0
Exp/Cntr=0.3,0.1

Type RM Length L Ch R = 1 ,42004   ,150,150,150
BEGIN DESCRIPTION:
Mapping XS 695771ca
END DESCRIPTION:
XS GIS Cut Line= 6
      3646036.44      10599048.5      3645999.99     10598579.79
      3646007.29     10598215.62       3645993.4     10598130.12
      3645958.32     10598079.79      3645708.33     10597538.14
#Sta/Elev= 30
    4081  427.44  4149.5  421.06  4219.7  416.67    4300  409.81  4400.3  398.17
  4480.5  394.38  4501.4  395.91  4600.7  396.95  4672.8  396.42  4778.6  395.07
  4783.6  393.51  4820.8  395.61  4967.9  395.69  4990.6  396.03  5033.6  396.35
  5036.3  396.31  5094.1   395.4  5116.2  393.75  5121.7  395.44    5129  393.64
    5164  393.09  5225.1  392.63  5227.9  392.13  5231.1  392.63  5236.4  394.37
  5305.2  397.38  5310.8  399.34  5425.5   406.4  5597.1  413.16  5659.9  414.29
#Mann= 9 ,-1 , 0
    4081     .05       0  4501.4     .16       0  4672.8     .05       0
  4967.9     .08       0  5036.3     .05       0  5094.1      .1       0
    5164     .05       0  5225.1     .07       0  5231.1     .05       0
#XS Ineff= 2 ,-1
 4378.68 4990.13  395.98 5050.28 5341.12  395.98
Permanent Ineff=
       T       T
Bank Sta=4990.6,5033.6
XS Rating Curve= 0 ,0
Exp/Cntr=0.3,0.1

Type RM Length L Ch R = 1 ,41854   ,626,626,626
BEGIN DESCRIPTION:
JELLY SLOUGH 85.0
END DESCRIPTION:
XS GIS Cut Line= 3
      3646068.13     10599050.73      3646076.81     10598200.01
      3646311.02     10597644.85
#Sta/Elev= 30
  4068.3  428.66  4158.8  420.65  4298.8   409.9  4318.8  410.08  4328.9  406.84
  4348.9  403.47  4468.9  389.79  4488.9  388.67  4498.9  386.51  4520.4  384.47
  4538.9  382.76  4575.9  382.15  4578.6  381.65  4581.9  382.15  4658.2  382.86
  4698.5  384.51  4703.5  383.84  4728.9  386.53  4798.9  386.21  4973.1  389.03
  4995.4  383.94  5013.7  388.21  5025.9  387.95  5042.9  387.75  5090.3  390.21
  5225.2  401.43  5268.7  403.45  5309.6  405.46    5402  406.94  5521.6  410.37
#Mann= 7 ,-1 , 0
  4068.3     .05       0  4520.4     .16       0  4575.9     .03       0
  4581.9     .16       0  4658.2     .05       0  5025.9     .16       0
  5268.7     .05       0
Bank Sta=4973.1,5013.7
XS Rating Curve= 0 ,0
Exp/Cntr=0.3,0.1

Type RM Length L Ch R = 1 ,41228   ,343,343,343
BEGIN DESCRIPTION:
JELLY SLOUGH 84.0
END DESCRIPTION:
XS GIS Cut Line= 3
      3646033.42     10599215.62      3646519.52     10598408.35
      3646910.18     10598026.37
#Sta/Elev= 30
    4275  426.82    4356  426.88  4421.4  428.92  4493.9  427.62  4596.5  416.99
  4610.4  417.17    4626  414.28  4684.2  410.32  4736.6  403.78  4742.5  400.66
  4785.2  393.72    4859  385.63  4892.9  382.15  4895.7  381.65  4898.9  382.15
  5086.5  382.19  5113.4  386.01  5134.8  389.49  5165.8  391.36  5208.6  398.09
  5237.3  400.54  5251.4  403.66  5286.9  406.55  5449.5  411.49  5555.5  411.27
  5597.9  414.25  5640.3  414.22  5704.1  417.35  5753.5   417.1  5763.7  418.24
#Mann= 4 ,-1 , 0
    4275     .05       0  4892.9    .033       0  4898.9     .05       0
  5086.5     .16       0
Bank Sta=4859,5113.4
XS Rating Curve= 0 ,0
Exp/Cntr=0.3,0.1

Type RM Length L Ch R = 1 ,40885   ,616,616,616
BEGIN DESCRIPTION:
JELLY SLOUGH 83.0
END DESCRIPTION:
XS GIS Cut Line= 3
      3646042.07     10599484.75      3646866.74     10598590.64
      3647057.03      10598374.4
#Sta/Elev= 30
  4025.6  425.08  4168.4  417.83  4189.9  418.17  4310.1  413.57  4338.5  414.06
  4373.6   411.9  4395.2  412.13  4487.1  406.98  4515.4  407.93  4572.1  403.57
  4578.9   401.3  4635.6  393.53  4720.7  385.56    4746  382.15  4748.8  381.65
    4752  382.15  5152.2  382.15    5188  385.86  5192.4  386.35  5223.1  388.82
  5258.2  394.28  5272.4  398.25  5286.7  400.48  5300.9  405.56    5372  421.06
  5386.3  422.67  5421.4  430.18  5435.6  432.24  5449.5  432.48    5530   427.1
#Mann= 5 ,-1 , 0
  4025.6     .05       0    4746    .033       0    4752     .05       0
  5192.4     .16       0  5449.5     .05       0
Bank Sta=4720.7,5188
XS Rating Curve= 0 ,0
Exp/Cntr=0.3,0.1

Type RM Length L Ch R = 1 ,40269   ,325,325,325
BEGIN DESCRIPTION:
JELLY SLOUGH 82.0
END DESCRIPTION:
XS GIS Cut Line= 2
      3647485.42     10599713.36      3647170.76     10598270.26
#Sta/Elev= 30
  4091.4   419.8  4185.4  417.88  4381.6  408.59  4432.4  407.51  4513.4  407.94
  4637.1   405.1  4704.5  400.01  4729.2  399.22  4790.6  391.89  4811.1  391.17
  4846.7  387.52  4862.3   385.7  4900.2  382.15    4903  381.65  4906.2  382.15
  4922.5  382.15  5152.1  383.01  5179.7  386.04  5218.6  391.56  5230.7  397.23
  5261.4  401.17  5267.6  402.78  5272.7  406.07  5304.6  408.81  5311.6   410.8
  5360.6  411.77  5365.7  413.89  5409.7  416.12  5502.7  426.98  5568.4  429.38
#Mann= 7 ,-1 , 0
  4091.4     .05       0  4846.7      .1       0  4900.2    .033       0
  4906.2      .1       0  4922.5     .05       0  5152.1     .16       0
  5304.6     .05       0
Bank Sta=4862.3,5179.7
XS Rating Curve= 0 ,0
Exp/Cntr=0.3,0.1

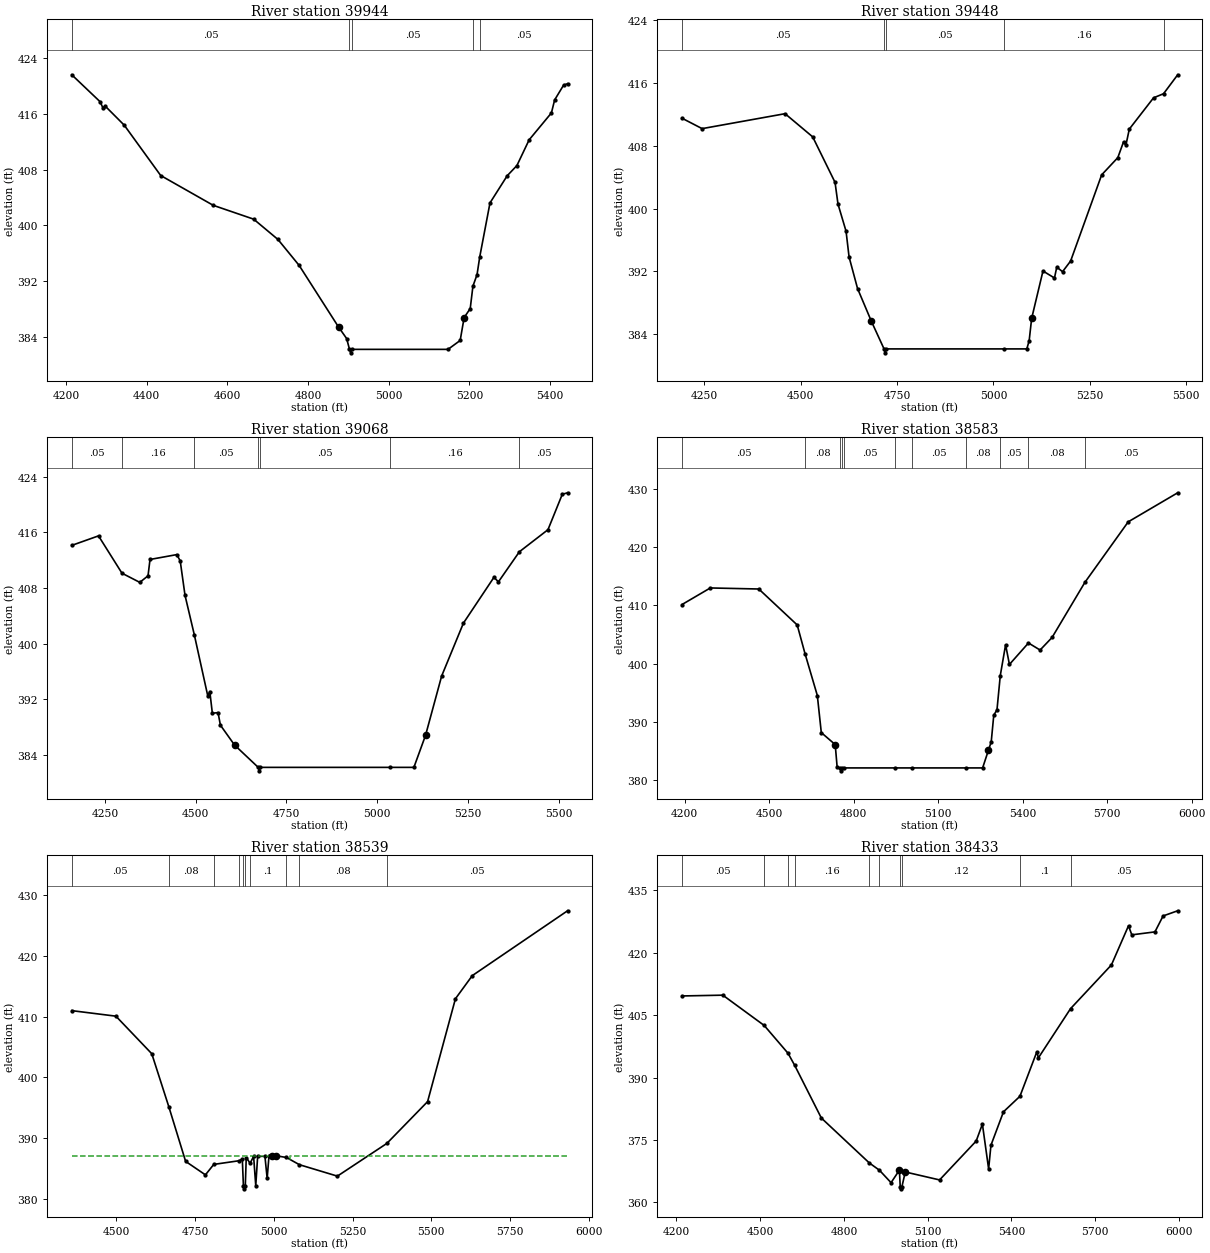
Type RM Length L Ch R = 1 ,39944   ,496,496,496
BEGIN DESCRIPTION:
JELLY SLOUGH 81.0
END DESCRIPTION:
XS GIS Cut Line= 3
      3647649.61     10599510.15      3647599.61     10598710.19
      3647449.62     10598310.21
#Sta/Elev= 30
  4214.6  421.65  4284.7  417.78  4292.2  416.84  4297.2  417.16  4344.8  414.39
    4435  407.16  4565.2  402.87  4665.4  400.88  4725.6  397.96  4778.2  394.22
  4875.8  385.36  4895.9   383.7  4902.9  382.15  4905.7  381.65  4908.9  382.15
    5147  382.15  5177.2  383.43    5187  386.72  5202.1  388.02  5208.8  391.24
    5219   392.9  5225.6  395.43  5251.1  403.22  5293.8  407.13  5317.8  408.59
  5348.1  412.29  5403.3  416.16  5411.3  418.03  5433.5  420.16  5443.3  420.36
#Mann= 5 ,-1 , 0
  4214.6     .05       0  4902.9    .033       0  4908.9     .05       0
  5208.8     .16       0  5225.6     .05       0
Bank Sta=4875.8,5187
XS Rating Curve= 0 ,0
Exp/Cntr=0.3,0.1

Type RM Length L Ch R = 1 ,39448   ,380,380,380
BEGIN DESCRIPTION:
JELLY SLOUGH 80.0
END DESCRIPTION:
XS GIS Cut Line= 2
      3648626.68     10598905.66      3647567.64     10598176.48
#Sta/Elev= 30
    4192   411.5  4244.4  410.17  4459.5  412.07  4531.2  409.12  4589.1  403.34
  4596.8  400.57  4617.7  397.12  4625.5  393.85  4647.5  389.83  4683.4  385.66
  4716.2  382.15    4719  381.65  4722.2  382.15  5026.7  382.15  5086.5  382.15
  5092.6   383.2    5099  386.02  5128.4  392.06  5158.2  391.17  5164.2  392.56
  5179.1  391.97  5200.1  393.33  5280.6  404.29  5322.5  406.48  5337.4   408.5
  5343.5  408.07  5352.3  410.11  5415.2  414.09  5441.1  414.61  5477.8  417.02
#Mann= 5 ,-1 , 0
    4192     .05       0  4716.2    .033       0  4722.2     .05       0
  5026.7     .16       0  5441.1     .05       0
Bank Sta=4683.4,5099
XS Rating Curve= 0 ,0
Exp/Cntr=0.3,0.1

Type RM Length L Ch R = 1 ,39068   ,485,485,485
BEGIN DESCRIPTION:
JELLY SLOUGH 79.0
END DESCRIPTION:
XS GIS Cut Line= 2
      3648939.17     10598497.67      3647706.55     10597911.74
#Sta/Elev= 30
  4158.9  414.14  4232.5  415.51  4297.1  410.13  4346.1  408.81  4368.8  409.75
  4374.3  412.11    4448  412.81  4457.4  411.91  4470.7  406.93  4496.1  401.29
  4533.3  392.45  4538.9  393.08  4545.9  389.95  4561.6  390.04  4568.1  388.23
    4607  385.37  4672.2  382.15  4674.9  381.65  4678.2  382.15  5033.7  382.15
  5100.7  382.15  5132.8  386.77  5177.1  395.31  5237.1  402.94    5321  409.53
  5333.5  408.89  5391.1  413.22  5469.8   416.4  5509.2   421.5  5523.7  421.72
#Mann= 7 ,-1 , 0
  4158.9     .05       0  4297.1     .16       0  4496.1     .05       0
  4672.2    .033       0  4678.2     .05       0  5033.7     .16       0
  5391.1     .05       0
Bank Sta=4607,5132.8
XS Rating Curve= 0 ,0
Exp/Cntr=0.3,0.1

Type RM Length L Ch R = 1 ,38583   ,44,44,44
BEGIN DESCRIPTION:
JELLY SLOUGH 78.0
END DESCRIPTION:
XS GIS Cut Line= 6
      3649002.14     10598338.87      3648741.74     10597974.32
      3648590.16      10597815.8      3648235.56     10597645.15
      3647830.77      10597562.4      3647562.93     10597462.81
#Sta/Elev= 30
  4189.8  410.14  4290.7  412.99  4462.8  412.81  4599.2  406.65  4627.1  401.71
  4670.7  394.56  4684.8   388.2  4734.2  386.15  4741.1  382.26  4752.3  382.15
    4755  381.65  4758.3  382.15  4766.2  382.15  4947.7  382.15    5006  382.15
  5199.6  382.15  5257.7  382.15  5278.1  385.14  5288.3  386.62  5297.3  391.19
  5308.7   392.1  5320.4  397.97  5339.3  403.25  5352.9  399.88  5420.5  403.56
  5461.8  402.35  5504.4  404.51  5620.8  413.94  5774.8  424.32  5950.5   429.3
#Mann= 11 ,-1 , 0
  4189.8     .05       0  4627.1     .08       0  4752.3     .07       0
  4758.3     .08       0  4766.2     .05       0  4947.7      .1       0
    5006     .05       0  5199.6     .08       0  5320.4     .05       0
  5420.5     .08       0  5620.8     .05       0
Bank Sta=4734.2,5278.1
XS Rating Curve= 0 ,0
Exp/Cntr=0.3,0.1

Type RM Length L Ch R = 1 ,38539   ,106,106,106
BEGIN DESCRIPTION:
Mapping XS 06fac271
END DESCRIPTION:
XS GIS Cut Line= 4
      3648941.37     10598165.26      3648680.98     10597835.43
      3648429.24      10597670.5      3647639.33     10597349.32
#Sta/Elev= 30
  4358.4  410.97  4498.5  410.06  4612.4  403.88  4666.8  395.11  4719.8  386.17
  4782.7  383.95  4809.2  385.67  4890.4  386.28  4899.8  386.55  4903.3  382.15
  4906.1  381.65  4909.3  382.15  4912.3   386.8  4924.5  385.86  4935.7  386.98
  4942.5  382.17  4948.5  386.99  4971.6  387.01  4978.7  383.36  4984.6  387.13
  4993.8  387.13  5007.4  387.09  5039.8  386.81  5081.2  385.62  5201.6  383.74
  5358.6  389.12    5488     396  5576.4  412.93  5629.9  416.73  5932.3   427.4
#Mann= 10 ,-1 , 0
  4358.4     .05       0  4666.8     .08       0  4809.2     .05       0
  4890.4     .08       0  4903.3     .07       0  4909.3     .08       0
  4924.5      .1       0  5039.8     .05       0  5081.2     .08       0
  5358.6     .05       0
#XS Ineff= 2 , 0
       0 4984.38  387.12 5052.06       0  387.05
Permanent Ineff=
       T       T
Bank Sta=4993.8,5007.4
XS Rating Curve= 0 ,0
Exp/Cntr=0.3,0.1

Type RM Length L Ch R = 1 ,38433   ,553,553,553
BEGIN DESCRIPTION:
JELLY SLOUGH 77.0
END DESCRIPTION:
XS GIS Cut Line= 4
      3649002.15     10598252.07      3648801.81     10597793.64
      3648420.62     10597536.55      3647692.98     10597167.83
#Sta/Elev= 30
  4219.6  409.59  4366.1  409.78  4514.4   402.5  4599.6  395.83  4623.3  392.95
    4719  380.27  4890.8  369.48  4927.1  367.73  4968.7  364.74  4998.6  367.75
  5001.6  363.76  5004.4  363.26  5007.6  363.76  5019.6  367.31  5142.5   365.4
  5273.6  374.74  5295.9  378.81  5318.2  368.04  5326.5  373.73  5371.4  381.77
  5430.3  385.49  5490.8  396.16  5496.4  394.72  5611.5  406.53    5758  417.04
  5819.2  426.45    5831  424.27  5913.9  424.98  5943.1  428.81  5995.4  430.05
#Mann= 10 ,-1 , 0
  4219.6     .05       0  4514.4     .16       0  4599.6     .05       0
  4623.3     .16       0  4890.8     .08       0  4927.1     .12       0
  5001.6     .07       0  5007.6     .12       0  5430.3      .1       0
  5611.5     .05       0
Bank Sta=4998.6,5019.6
XS Rating Curve= 0 ,0
Exp/Cntr=0.3,0.1

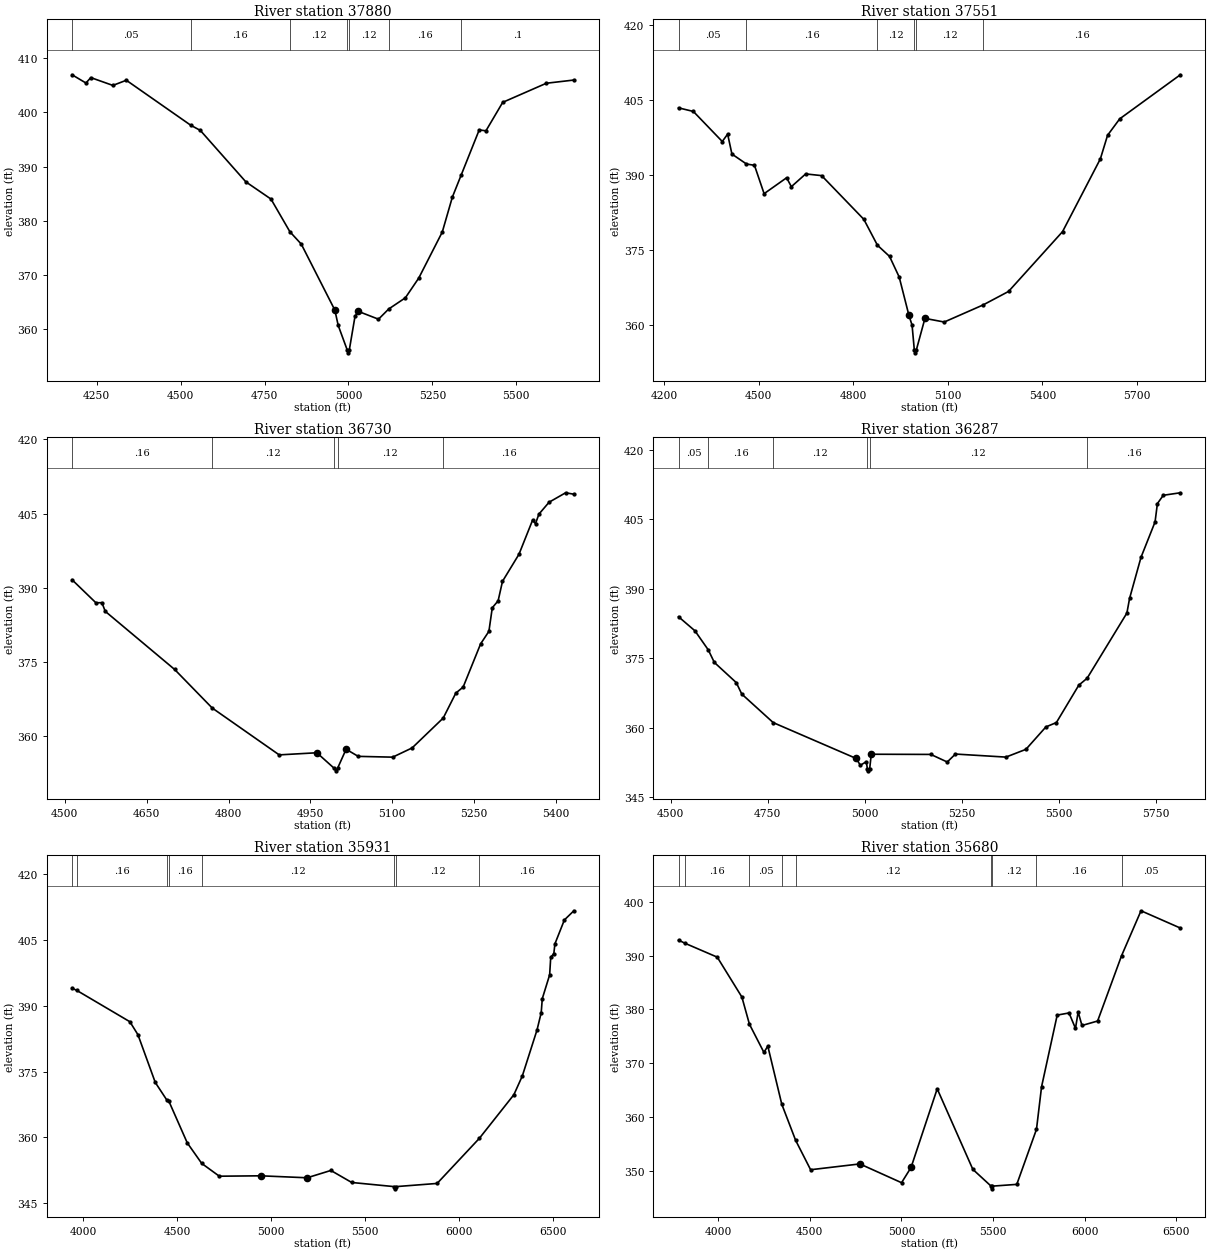
Type RM Length L Ch R = 1 ,37880   ,329,329,329
BEGIN DESCRIPTION:
JELLY SLOUGH 76.0
END DESCRIPTION:
XS GIS Cut Line= 3
      3649088.18     10598341.45      3649044.78     10597673.01
      3649053.46     10596848.31
#Sta/Elev= 30
  4176.7  406.91  4218.1  405.39  4232.5  406.39  4298.2  404.95  4338.3   405.9
  4529.9  397.62  4558.8  396.65  4694.4  387.17  4769.2     384  4825.5  377.98
  4859.4   375.7  4959.4  363.54  4969.4  360.71  4996.4  356.16  4999.1  355.66
  5002.4  356.16  5019.4  362.37  5029.4   363.3  5089.4  361.86  5119.8  363.74
  5169.4   365.8  5209.4  369.45  5279.4  377.93  5309.4  384.36  5335.5   388.4
  5389.4  396.75  5409.4  396.58  5459.4  401.83  5589.4  405.35  5671.3  405.94
#Mann= 7 ,-1 , 0
  4176.7     .05       0  4529.9     .16       0  4825.5     .12       0
  4996.4     .07       0  5002.4     .12       0  5119.8     .16       0
  5335.5      .1       0
Bank Sta=4959.4,5029.4
XS Rating Curve= 0 ,0
Exp/Cntr=0.3,0.1

Type RM Length L Ch R = 1 ,37551   ,821,821,821
BEGIN DESCRIPTION:
JELLY SLOUGH 75.0
END DESCRIPTION:
XS GIS Cut Line= 3
      3649193.14     10598356.22      3649375.42     10597462.17
      3649661.89     10596845.83
#Sta/Elev= 30
  4245.6  403.49  4292.6  402.77  4384.4  396.76  4401.4  398.24    4415  394.25
  4461.2  392.26  4486.5     392  4517.1  386.33  4588.5  389.51  4603.6  387.73
    4649  390.28  4699.6  389.94  4833.5   381.2  4876.6  376.03  4915.1  373.79
  4945.7  369.67  4976.4  362.05  4986.6  360.03  4993.8  355.01  4996.5  354.51
  4999.8  355.01  5027.4   361.4  5088.6  360.67  5211.8  364.08  5292.6  366.78
    5464  378.74    5584  393.29  5606.9  398.01  5645.4  401.29  5837.7   410.1
#Mann= 6 ,-1 , 0
  4245.6     .05       0  4461.2     .16       0  4876.6     .12       0
  4993.8     .07       0  4999.8     .12       0  5211.8     .16       0
Bank Sta=4976.4,5027.4
XS Rating Curve= 0 ,0
Exp/Cntr=0.3,0.1

Type RM Length L Ch R = 1 ,36730   ,443,443,443
BEGIN DESCRIPTION:
JELLY SLOUGH 74.0
END DESCRIPTION:
XS GIS Cut Line= 3
      3649799.62     10598060.16      3649999.61     10597610.19
      3649849.61     10597210.19
#Sta/Elev= 30
  4513.2  391.59  4556.9  386.93  4567.9  386.95    4574   385.2  4701.2  373.43
    4770  365.63  4892.8  356.14  4961.8  356.57  4993.7  353.41  4996.5  352.91
  4999.7  353.41  5015.4  357.28  5037.6  355.84  5100.8  355.68  5136.4  357.55
  5193.4   363.6  5216.5  368.65  5229.9  369.87  5261.9  378.61  5277.1  381.15
  5283.3  385.92    5294  387.33    5302  391.27  5332.2  396.75  5357.2  403.67
  5362.5  402.94  5368.7  404.87  5387.4  407.29  5417.7   409.2  5432.8  408.91
#Mann= 5 ,-1 , 0
  4513.2     .16       0    4770     .12       0  4993.7     .07       0
  4999.7     .12       0  5193.4     .16       0
Bank Sta=4961.8,5015.4
XS Rating Curve= 0 ,0
Exp/Cntr=0.3,0.1

Type RM Length L Ch R = 1 ,36287   ,356,356,356
BEGIN DESCRIPTION:
JELLY SLOUGH 73.0
END DESCRIPTION:
XS GIS Cut Line= 3
      3650049.58     10598060.21      3650399.61     10597760.19
       3649949.6     10597060.17
#Sta/Elev= 30
  4520.3  383.95  4562.6  380.91    4597  376.78  4612.5  374.08  4669.1  369.71
  4683.3  367.23  4764.3  361.06    4978  353.31  4988.9  351.83  5004.1  352.61
    5007  351.13  5009.8  350.63    5013  351.13    5017  354.22  5170.5  354.18
  5212.8  352.54  5233.9  354.26    5364   353.6  5415.6  355.28  5467.1  360.13
  5494.1  361.07  5551.9  369.16  5573.3  370.65  5675.8  384.75  5682.7  387.92
  5712.1  396.79  5748.4  404.46  5754.4  408.42  5769.6  410.22  5813.5  410.76
#Mann= 6 ,-1 , 0
  4520.3     .05       0    4597     .16       0  4764.3     .12       0
    5007     .07       0    5013     .12       0  5573.3     .16       0
Bank Sta=4978,5017
XS Rating Curve= 0 ,0
Exp/Cntr=0.3,0.1

Type RM Length L Ch R = 1 ,35931   ,251,251,251
BEGIN DESCRIPTION:
JELLY SLOUGH 72.0
END DESCRIPTION:
XS GIS Cut Line= 4
      3650095.91     10598529.87      3650668.83     10597861.47
      3650755.63     10597167.03      3650269.64     10596195.04
#Sta/Elev= 30
  3941.9  394.03  3966.9  393.52  4249.1  386.38  4291.9  383.43  4384.1  372.54
  4444.6  368.59  4455.1  368.39  4554.2  358.76  4631.1  354.08  4724.4  351.17
  4944.5  351.26  5191.4  350.81  5317.3  352.48  5428.2  349.74  5655.4  348.79
  5658.2  348.29  5661.4  348.79    5882  349.52  6106.5   359.8  6290.1  369.75
  6334.8  374.01    6413   384.5  6435.3  388.44    6441  391.64  6480.1  397.06
  6485.8  401.04  6502.4  401.92  6508.1  404.13  6558.4  409.58  6608.8  411.67
#Mann= 8 ,-1 , 0
  3941.9     .05       0  3966.9     .16       0  4444.6     .05       0
  4455.1     .16       0  4631.1     .12       0  5655.4     .07       0
  5661.4     .12       0  6106.5     .16       0
Bank Sta=4944.5,5191.4
XS Rating Curve= 0 ,0
Exp/Cntr=0.3,0.1

Type RM Length L Ch R = 1 ,35680   ,307,307,307
BEGIN DESCRIPTION:
Mapping XS ebc71b48
END DESCRIPTION:
XS GIS Cut Line= 4
      3650147.99     10598547.24      3650894.52     10597783.35
      3651042.09     10597236.47      3651918.83     10596568.07
#Sta/Elev= 30
  3783.9  392.87  3818.5  392.29  3995.1   389.7  4129.4  382.29  4170.6  377.24
  4249.7  371.99  4270.8  373.17    4347  362.37  4422.7  355.65  4504.3  350.19
  4772.9  351.27  5000.3  347.78  5052.1  350.61  5194.8  365.23  5389.2  350.26
  5488.8  347.14  5491.5  346.64  5494.8  347.14  5628.9  347.47  5736.3   357.7
    5764  365.61  5849.3  378.93  5913.7  379.33    5949  376.46  5963.6  379.51
  5984.4     377  6069.7  377.83  6200.4  389.97  6306.5  398.32  6520.9  395.11
#Mann= 9 ,-1 , 0
  3783.9     .05       0  3818.5     .16       0  4170.6     .05       0
    4347     .16       0  4422.7     .12       0  5488.8     .07       0
  5494.8     .12       0  5736.3     .16       0  6200.4     .05       0
Bank Sta=4772.9,5052.1
XS Rating Curve= 0 ,0
Exp/Cntr=0.3,0.1

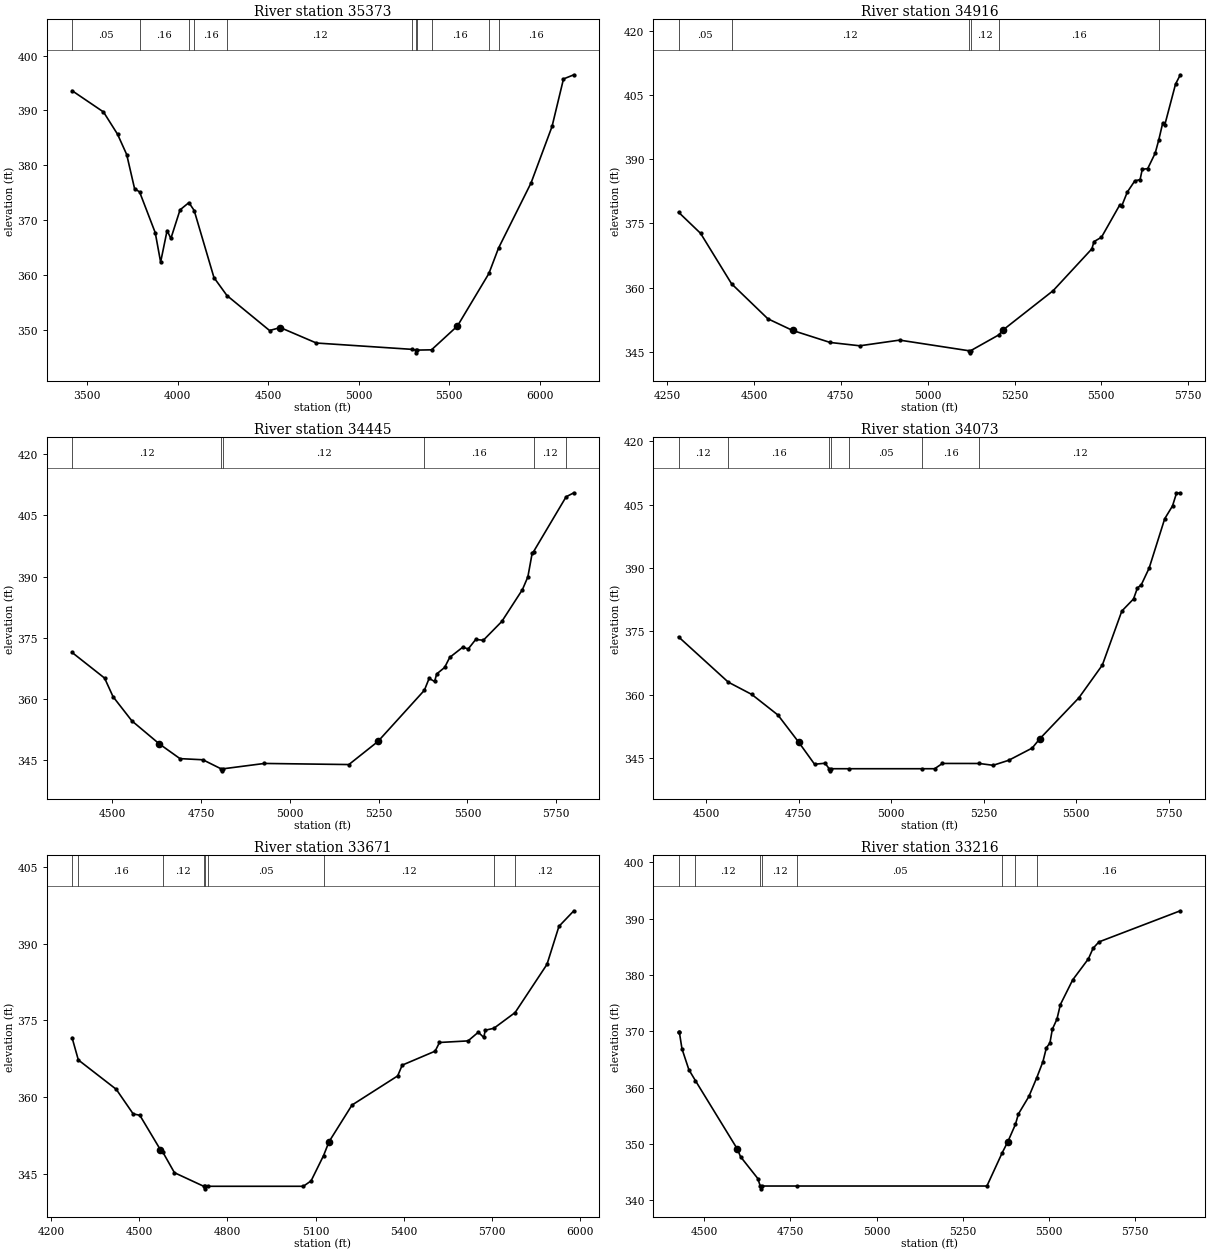
Type RM Length L Ch R = 1 ,35373   ,457,457,457
BEGIN DESCRIPTION:
JELLY SLOUGH 71.0
END DESCRIPTION:
XS GIS Cut Line= 3
      3650321.63     10598972.55      3651345.91     10597514.25
      3652283.99      10597202.2
#Sta/Elev= 30
  3416.8  393.61  3590.3  389.73  3667.9  385.67  3718.4  381.97  3761.9  375.75
  3789.6  375.15  3876.1  367.71  3905.8  362.35  3941.5  368.11  3962.4  366.66
    4013  371.88  4061.9   373.2  4091.1  371.76  4200.3  359.53  4271.9  356.26
  4507.3  349.88  4566.3  350.42  4765.8   347.6    5296  346.44    5315  346.31
  5317.8  345.81    5321  346.31  5401.6  346.36  5544.8  350.71  5718.4  360.28
  5771.4   364.9    5951  376.78    6067  387.08  6130.2  395.75  6187.5  396.51
#Mann= 11 ,-1 , 0
  3416.8     .05       0  3789.6     .16       0  4061.9     .05       0
  4091.1     .16       0  4271.9     .12       0    5296      .1       0
    5315     .07       0    5321      .1       0  5401.6     .16       0
  5718.4      .1       0  5771.4     .16       0
Bank Sta=4566.3,5544.8
XS Rating Curve= 0 ,0
Exp/Cntr=0.3,0.1

Type RM Length L Ch R = 1 ,34916   ,471,471,471
BEGIN DESCRIPTION:
JELLY SLOUGH 70.0
END DESCRIPTION:
XS GIS Cut Line= 3
      3651049.63     10598610.15      3651499.61     10598010.19
      3652099.63     10597660.18
#Sta/Elev= 30
  4282.7  377.64  4346.2  372.69  4435.4  360.88  4539.9  352.69  4610.8  349.97
  4719.1  347.15  4804.5  346.37  4919.1   347.7  5117.7  345.22  5120.5  344.72
  5123.7  345.22  5205.1  348.94  5216.6  350.05  5361.4  359.29  5472.6  369.06
  5478.8  370.76  5500.3  371.78  5553.2  379.38    5559  379.17  5574.7  382.36
  5596.2  384.97  5611.5  385.28  5617.7  387.67  5633.4  387.85  5654.9  391.45
  5665.2  394.55  5676.4  398.45  5682.2  397.96  5713.6  407.65  5727.3  409.81
#Mann= 6 ,-1 , 0
  4282.7     .05       0  4435.4     .12       0  5117.7     .07       0
  5123.7     .12       0  5205.1     .16       0  5665.2     .12       0
Bank Sta=4610.8,5216.6
XS Rating Curve= 0 ,0
Exp/Cntr=0.3,0.1

Type RM Length L Ch R = 1 ,34445   ,372,372,372
BEGIN DESCRIPTION:
JELLY SLOUGH 69.0
END DESCRIPTION:
XS GIS Cut Line= 3
       3651549.6     10598960.21      3651799.61     10598360.19
      3652199.59     10597710.22
#Sta/Elev= 30
  4386.4  371.41    4478  365.13  4501.8  360.58  4554.9  354.65  4631.8  349.04
  4690.3  345.41  4754.8  345.13  4805.9  342.92  4808.7  342.42  4811.9  342.92
  4928.1  344.23    5166  343.96  5247.8  349.61  5378.6  362.15    5392  365.06
  5407.4   364.3  5413.3  366.15  5435.6  367.73    5450   370.2  5486.6  372.69
  5502.1  372.27  5523.3   374.6  5544.6  374.39  5596.7     379  5654.7  386.79
  5670.1  389.93  5682.2  395.72  5686.3  396.12  5777.8  409.53  5799.6  410.51
#Mann= 6 ,-1 , 0
  4386.4     .12       0  4805.9     .07       0  4811.9     .12       0
  5378.6     .16       0  5686.3     .12       0  5777.8     .16       0
Bank Sta=4631.8,5247.8
XS Rating Curve= 0 ,0
Exp/Cntr=0.3,0.1

Type RM Length L Ch R = 1 ,34073   ,402,402,402
BEGIN DESCRIPTION:
JELLY SLOUGH 68.0
END DESCRIPTION:
XS GIS Cut Line= 3
      3651649.58     10599060.21      3652049.61     10598660.19
      3652299.61     10597910.18
#Sta/Elev= 30
  4425.4  373.73  4559.9  363.01  4623.4   360.1  4694.1  355.23  4750.7  348.74
  4793.1  343.58  4821.4  343.82  4832.6  342.52  4835.3  342.02  4838.6  342.52
  4886.4  342.52  5083.3  342.52  5117.6  342.52  5138.7  343.77  5238.2  343.76
  5275.7  343.33  5317.9  344.52  5381.1   347.4  5402.2  349.64  5507.6  359.31
  5570.9  367.05  5623.6  379.84  5655.2   382.7  5665.7  385.29  5676.3  386.08
  5697.4     390  5739.5  401.69  5760.6  404.72  5771.2   407.7  5781.7  407.83
#Mann= 7 ,-1 , 0
  4425.4     .12       0  4559.9     .16       0  4832.6    .033       0
  4838.6     .16       0  4886.4     .05       0  5083.3     .16       0
  5238.2     .12       0
Bank Sta=4750.7,5402.2
XS Rating Curve= 0 ,0
Exp/Cntr=0.3,0.1

Type RM Length L Ch R = 1 ,33671   ,455,455,455
BEGIN DESCRIPTION:
JELLY SLOUGH 67.0
END DESCRIPTION:
XS GIS Cut Line= 3
      3652349.61     10599560.16      3652399.61     10598860.19
      3652578.54     10597870.18
#Sta/Elev= 30
  4271.5  371.61  4292.8  367.25  4421.9   361.5  4479.5  356.69  4502.1  356.42
  4572.2  349.67  4579.7  349.27  4619.9  345.18  4719.6  342.52  4722.4  342.02
  4725.6  342.52  4733.9  342.52  5058.6  342.52    5085  343.58  5127.5  348.54
    5146  351.24  5224.2  358.42  5379.7  364.13    5395  366.23  5507.1  368.97
    5522  370.67  5619.2  370.98  5654.1  372.68  5672.7  371.65  5677.8  373.07
  5707.1  373.45  5779.4  376.53  5887.8  385.96  5928.5   393.4  5979.3  396.45
#Mann= 9 ,-1 , 0
  4271.5     .08       0  4292.8     .16       0  4579.7     .12       0
  4719.6    .033       0  4725.6     .12       0  4733.9     .05       0
  5127.5     .12       0  5707.1     .16       0  5779.4     .12       0
Bank Sta=4572.2,5146
XS Rating Curve= 0 ,0
Exp/Cntr=0.3,0.1

Type RM Length L Ch R = 1 ,33216   ,453,453,453
BEGIN DESCRIPTION:
JELLY SLOUGH 66.0
END DESCRIPTION:
XS GIS Cut Line= 3
      3652849.61     10599460.22      3652849.61     10598860.19
      3652700.07     10598017.69
#Sta/Elev= 30
  4425.7   369.8  4428.2   369.8  4435.7  366.89  4455.7  363.18  4474.6  361.25
  4595.7  349.15  4605.7  347.72  4655.7  343.85  4662.7  342.52  4665.5  342.02
  4668.7  342.52  4768.8  342.52  5320.3  342.52  5364.8  348.44  5381.2  350.42
  5402.9  353.45  5411.7  355.32  5442.1  358.43  5465.1  361.79  5482.8  364.61
  5492.9  367.09  5503.1  367.92  5510.1  370.37  5523.4  372.15  5533.5  374.76
  5569.2  379.14  5614.8  382.88  5628.3  384.75  5645.3  385.88  5881.4  391.41
#Mann= 8 ,-1 , 0
  4425.7     .08       0  4474.6     .12       0  4662.7    .033       0
  4668.7     .12       0  4768.8     .05       0  5364.8     .16       0
  5402.9     .12       0  5465.1     .16       0
Bank Sta=4595.7,5381.2
XS Rating Curve= 0 ,0
Exp/Cntr=0.3,0.1