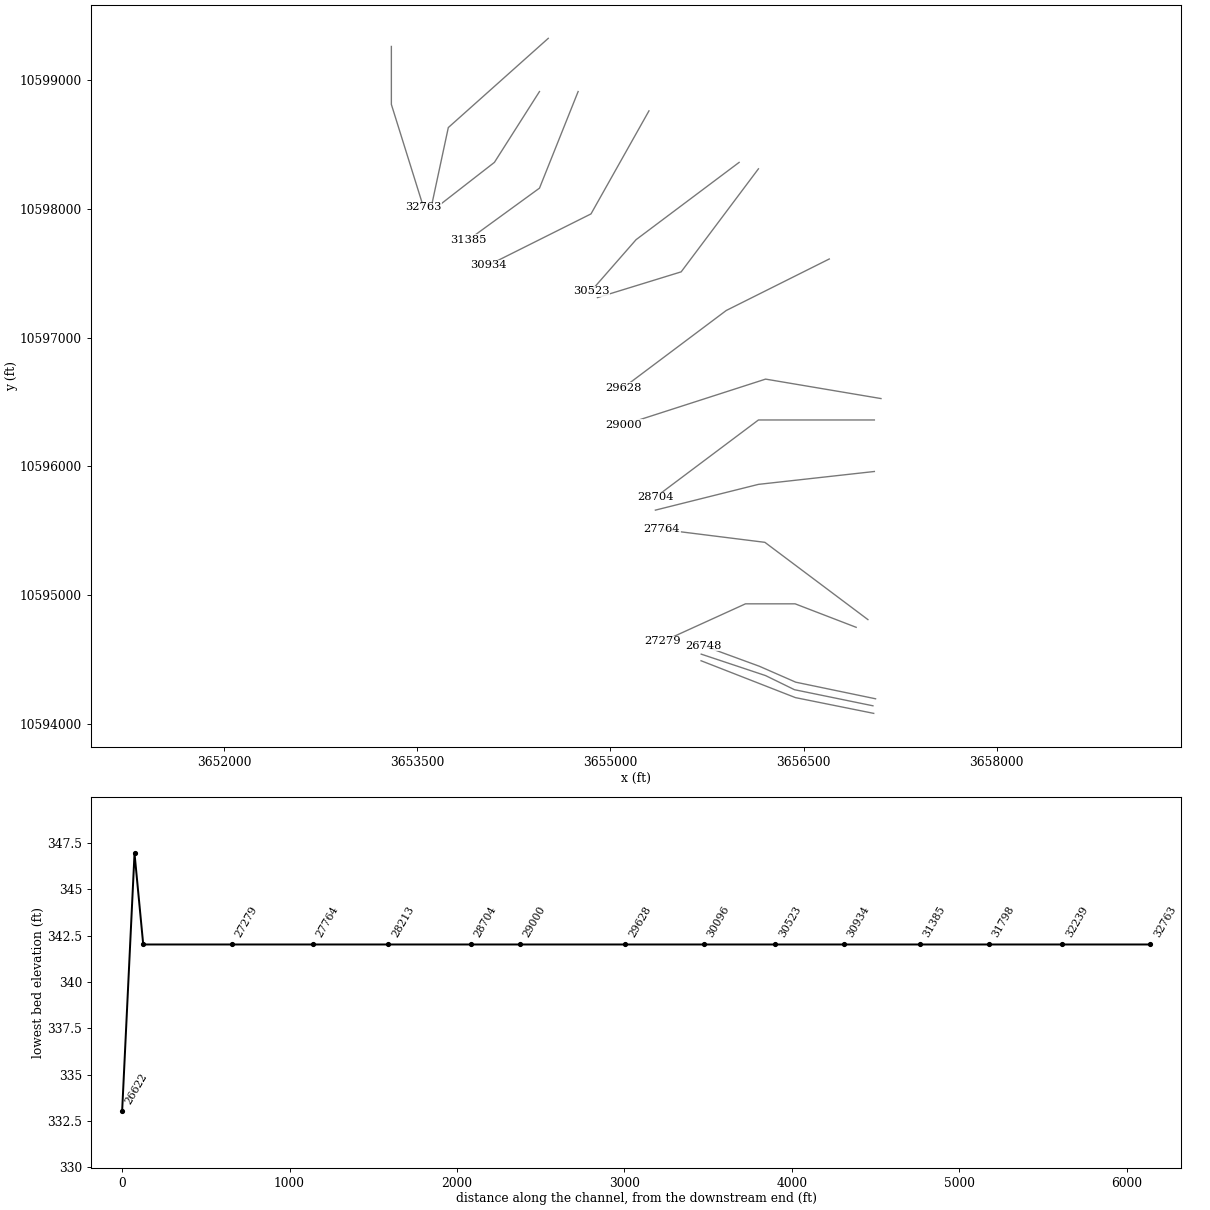
HEC-RAS study JELLY SLOUGH.prj: JELLY SLOUGH Base Level Engineering

--- JELLY SLOUGH.g01 (geometry) --- (continued)

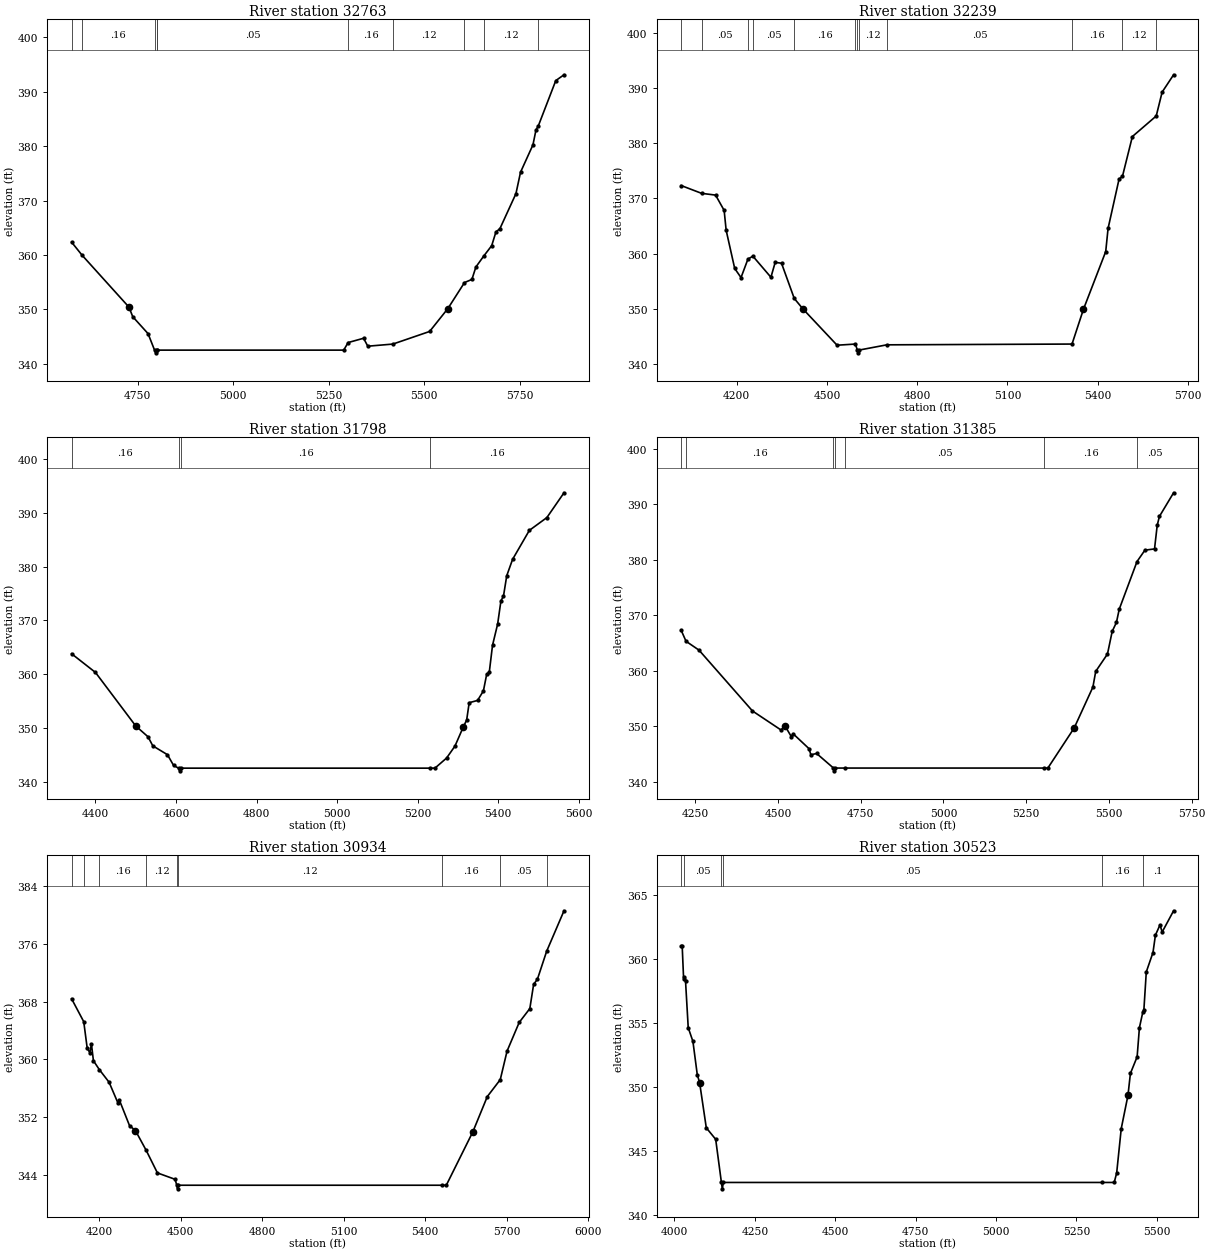
Type RM Length L Ch R = 1 ,32763   ,524,524,524
BEGIN DESCRIPTION:
JELLY SLOUGH 65.0
END DESCRIPTION:
XS GIS Cut Line= 3
      3653299.61     10599260.16      3653299.61     10598810.19
       3653549.6     10598010.21
#Sta/Elev= 30
  4577.3  362.37  4604.7  359.97  4727.3  350.43  4737.3  348.66  4777.3  345.55
  4794.3  342.52    4797  342.02  4800.3  342.52  4800.9  342.52  5289.2  342.52
  5300.6  343.91  5341.1   344.7  5352.1  343.24  5417.7  343.63  5513.9  345.95
  5561.6  350.16  5605.1  354.94  5624.5  355.52  5634.9   357.8  5655.2  359.79
  5676.3  361.73  5687.3  364.24  5697.8  364.86  5739.7  371.29  5751.7  375.23
  5784.2  380.26  5792.1     383  5798.3  383.76  5843.9  392.07  5865.4  393.14
#Mann= 10 ,-1 , 0
  4577.3     .05       0  4604.7     .16       0  4794.3    .033       0
  4800.3     .16       0  4800.9     .05       0  5300.6     .16       0
  5417.7     .12       0  5605.1     .16       0  5655.2     .12       0
  5798.3     .16       0
Bank Sta=4727.3,5561.6
XS Rating Curve= 0 ,0
Exp/Cntr=0.3,0.1

Type RM Length L Ch R = 1 ,32239   ,441,441,441
BEGIN DESCRIPTION:
JELLY SLOUGH 64.0
END DESCRIPTION:
XS GIS Cut Line= 3
       3654517.8     10599323.29      3653741.74     10598630.57
      3653616.75     10598047.27
#Sta/Elev= 30
  4015.4   372.3  4083.2  370.89  4129.8  370.57  4158.2   367.8  4164.9   364.2
  4193.3  357.29  4214.3  355.64  4237.2  358.98  4253.7  359.52  4313.7   355.7
  4327.9   358.4  4348.9  358.24  4391.2  351.87  4419.9  349.98  4533.6   343.4
  4594.7  343.61  4600.8  342.52  4603.6  342.02  4606.8  342.52  4699.1  343.47
  5314.6  343.61  5352.6  349.91  5426.6  360.35  5434.4  364.53  5470.9  373.46
  5482.3  373.98  5515.2  381.17  5594.5  384.89  5614.1  389.21  5652.2  392.35
#Mann= 12 ,-1 , 0
  4015.4     .16       0  4083.2     .05       0  4237.2     .08       0
  4253.7     .05       0  4391.2     .16       0  4594.7     .12       0
  4600.8    .033       0  4606.8     .12       0  4699.1     .05       0
  5314.6     .16       0  5482.3     .12       0  5594.5     .16       0
Bank Sta=4419.9,5352.6
XS Rating Curve= 0 ,0
Exp/Cntr=0.3,0.1

Type RM Length L Ch R = 1 ,31798   ,413,413,413
BEGIN DESCRIPTION:
JELLY SLOUGH 63.0
END DESCRIPTION:
XS GIS Cut Line= 3
      3654449.61     10598910.19      3654099.61     10598360.19
      3653649.62     10598010.19
#Sta/Elev= 30
  4341.1  363.79  4400.4  360.31  4500.3  350.36  4530.8  348.35  4542.6  346.67
    4579  345.02  4594.2  343.03  4606.5  342.52  4609.2  342.02  4612.5  342.52
  5231.7  342.52  5242.8  342.52  5271.7   344.4  5292.5  346.62  5313.4  350.22
  5321.5  351.45  5327.8  354.69  5348.6  355.11  5363.1  356.89  5371.3     360
  5377.6  360.31  5385.7  365.36  5398.4  369.31  5406.6  373.63  5412.9  374.49
    5421   378.3  5435.5  381.34  5477.1  386.73  5520.6  389.11  5563.1  393.72
#Mann= 4 ,-1 , 0
  4341.1     .16       0  4606.5    .033       0  4612.5     .16       0
  5231.7     .16       0
Bank Sta=4500.3,5313.4
XS Rating Curve= 0 ,0
Exp/Cntr=0.3,0.1

Type RM Length L Ch R = 1 ,31385   ,451,451,451
BEGIN DESCRIPTION:
JELLY SLOUGH 62.0
END DESCRIPTION:
XS GIS Cut Line= 3
      3654749.62     10598910.22      3654449.61     10598160.19
      3653899.59     10597760.18
#Sta/Elev= 30
  4207.5   367.3  4222.1  365.33  4261.4  363.73  4422.9  352.79  4509.1  349.37
  4521.2   350.1  4540.1  348.19  4545.4  348.71  4593.9     346  4599.3  344.91
  4616.8  345.14  4667.7  342.52  4670.4  342.02  4673.7  342.52  4703.8  342.52
  5303.9  342.52  5315.5  342.52  5395.1  349.74  5451.6  357.09  5460.1  359.91
  5495.6  363.03  5509.9  367.11  5522.7  368.72  5531.2   371.1  5584.9  379.67
  5608.8  381.72  5637.8  381.94  5645.9  386.17  5652.5  387.78  5695.4  392.04
#Mann= 7 ,-1 , 0
  4207.5     .05       0  4222.1     .16       0  4667.7    .033       0
  4673.7     .16       0  4703.8     .05       0  5303.9     .16       0
  5584.9     .05       0
Bank Sta=4521.2,5395.1
XS Rating Curve= 0 ,0
Exp/Cntr=0.3,0.1

Type RM Length L Ch R = 1 ,30934   ,411,411,411
BEGIN DESCRIPTION:
JELLY SLOUGH 61.0
END DESCRIPTION:
XS GIS Cut Line= 3
      3655299.61     10598760.19      3654849.61     10597960.19
      3654049.61     10597560.19
#Sta/Elev= 30
  4098.2  368.39  4142.9  365.21  4155.6  361.54  4165.4   360.9  4171.2  362.13
  4178.5   359.8  4200.5  358.55  4236.2  356.81  4268.1  353.99  4273.8  354.36
  4311.4  350.79  4333.1  350.11    4373  347.34    4414  344.23  4479.1  343.34
  4485.3  342.52    4488  342.02  4491.3  342.52  5461.7  342.52  5477.3  342.52
  5575.1  349.94  5628.2  354.82  5675.9  357.17  5700.9  361.13  5745.6  365.11
  5784.7  367.03  5798.7  370.39  5812.7  371.11  5846.7  374.99  5910.5   380.6
#Mann= 9 ,-1 , 0
  4098.2     .08       0  4142.9     .05       0  4200.5     .16       0
    4373     .12       0  4485.3    .033       0  4491.3     .12       0
  5461.7     .16       0  5675.9     .05       0  5846.7     .16       0
Bank Sta=4333.1,5575.1
XS Rating Curve= 0 ,0
Exp/Cntr=0.3,0.1

Type RM Length L Ch R = 1 ,30523   ,427,427,427
BEGIN DESCRIPTION:
JELLY SLOUGH 60.0
END DESCRIPTION:
XS GIS Cut Line= 3
       3655999.6     10598360.18      3655199.61     10597760.19
      3654849.61     10597360.19
#Sta/Elev= 30
  4020.8  361.05  4023.9  361.05  4028.1  358.61  4031.1  358.46  4034.3   358.3
  4042.7  354.64  4057.3  353.57  4070.8  350.97  4078.1  350.34  4098.9   346.8
  4128.1   345.9  4145.9  342.52  4148.7  342.02  4151.9  342.52  5328.3  342.52
  5367.7  342.52  5375.3  343.27  5389.5  346.74  5410.4  349.34    5418  351.06
  5438.9  352.36    5446  354.64  5456.9   355.9  5459.8     356  5467.4  359.01
  5488.2  360.53  5495.8  361.89  5510.1   362.7  5516.7  362.13  5552.3   363.8
#Mann= 6 ,-1 , 0
  4020.8     .16       0  4031.1     .05       0  4145.9    .033       0
  4151.9     .05       0  5328.3     .16       0  5456.9      .1       0
Bank Sta=4078.1,5410.4
XS Rating Curve= 0 ,0
Exp/Cntr=0.3,0.1

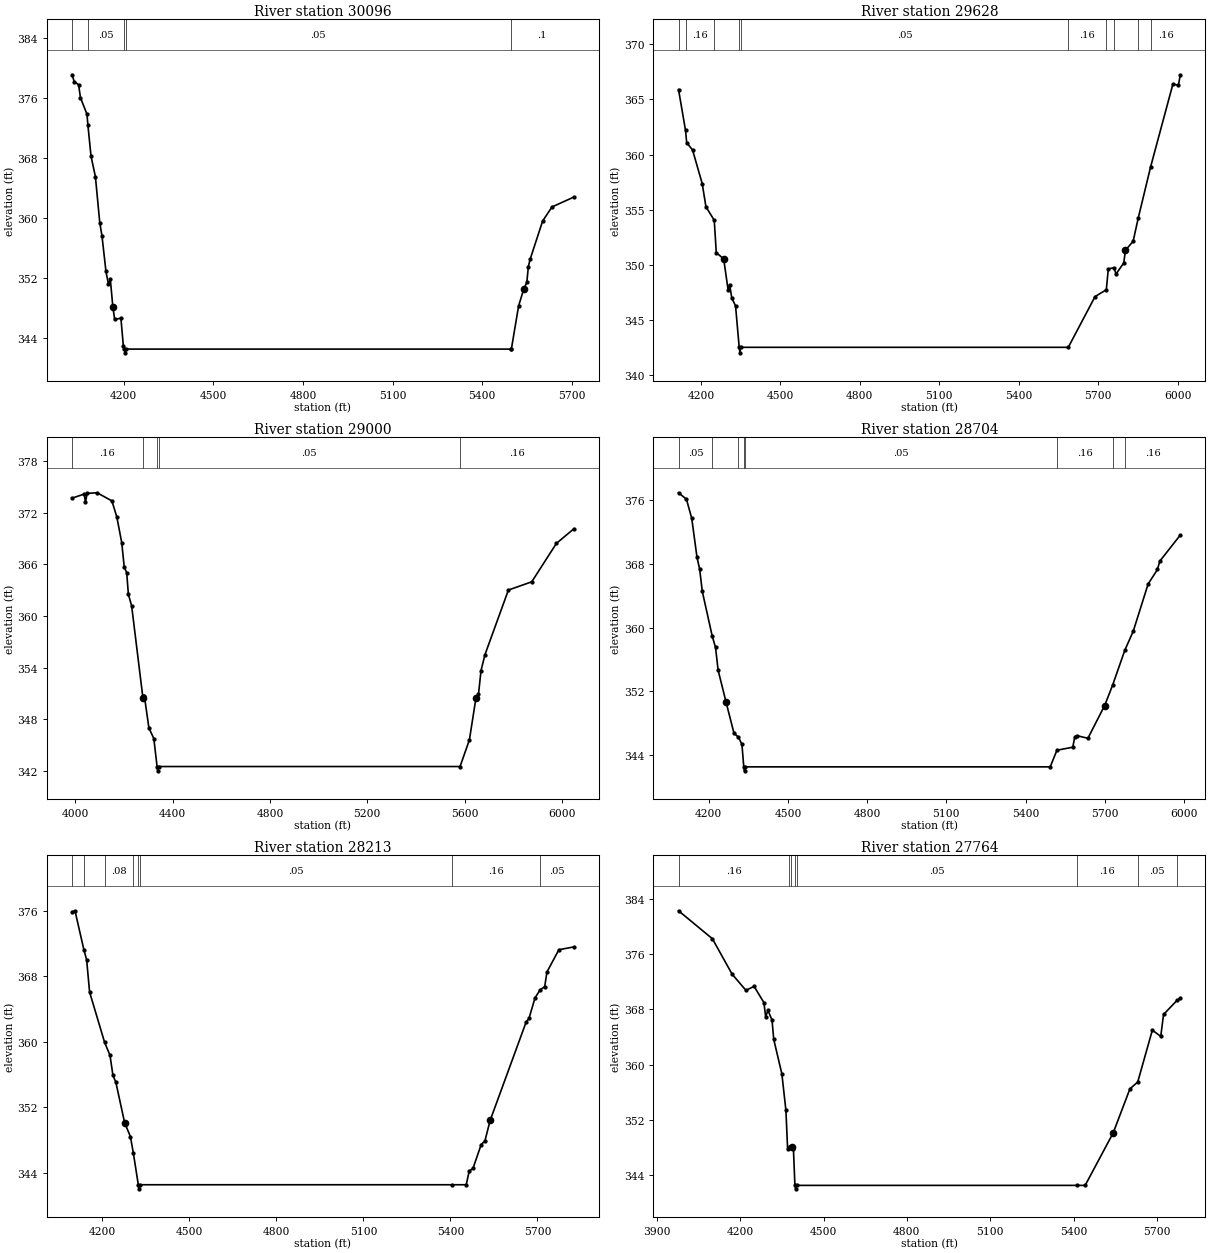
Type RM Length L Ch R = 1 ,30096   ,468,468,468
BEGIN DESCRIPTION:
JELLY SLOUGH 59.0
END DESCRIPTION:
XS GIS Cut Line= 3
      3656149.59     10598310.17      3655549.61     10597510.19
      3654899.65      10597310.2
#Sta/Elev= 30
  4027.1  379.11  4034.4   378.2  4048.9  377.79  4055.2  376.06  4077.1  373.84
    4080  372.43  4090.6  368.24  4105.2  365.53  4119.8   359.4  4127.1  357.66
  4140.6  352.87  4148.9  351.17  4155.2  351.84  4163.5  348.19  4169.8  346.48
  4190.6  346.64  4198.9   342.9  4202.2  342.52  4204.9  342.02  4208.2  342.52
  5495.2  342.52  5497.9  342.52  5522.1  348.28  5539.7  350.57  5549.6  351.42
  5554.8  353.53  5560.7   354.5  5602.5   359.6  5633.9  361.48  5707.1   362.8
#Mann= 5 ,-1 , 0
  4027.1     .16       0    4080     .05       0  4202.2    .033       0
  4208.2     .05       0  5495.2      .1       0
Bank Sta=4163.5,5539.7
XS Rating Curve= 0 ,0
Exp/Cntr=0.3,0.1

Type RM Length L Ch R = 1 ,29628   ,628,628,628
BEGIN DESCRIPTION:
JELLY SLOUGH 58.0
END DESCRIPTION:
XS GIS Cut Line= 3
      3656699.59     10597610.18      3655899.61     10597210.19
      3655099.61     10596610.19
#Sta/Elev= 30
  4115.8  365.89  4142.2  362.18  4146.5  361.09  4168.9   360.4  4205.2  357.36
  4219.2  355.27  4250.7  354.03  4258.3  351.11  4286.3  350.53    4303  347.72
  4308.6  348.21    4317  346.97    4331  346.29  4344.8  342.52  4347.5  342.02
  4350.8  342.52  5587.2  342.52  5688.3  347.12  5730.8  347.74  5738.3  349.63
  5759.6  349.74  5767.5  349.17  5796.7  350.17  5802.9  351.31  5832.1  352.14
    5851  354.21  5897.9  358.87  5982.1  366.38  6002.9  366.29  6010.2  367.23
#Mann= 10 ,-1 , 0
  4115.8     .05       0  4142.2     .16       0  4250.7     .05       0
  4344.8    .033       0  4350.8     .05       0  5587.2     .16       0
  5730.8     .12       0  5759.6     .16       0    5851     .12       0
  5897.9     .16       0
Bank Sta=4286.3,5802.9
XS Rating Curve= 0 ,0
Exp/Cntr=0.3,0.1

Type RM Length L Ch R = 1 ,29000   ,296,296,296
BEGIN DESCRIPTION:
JELLY SLOUGH 57.0
END DESCRIPTION:
XS GIS Cut Line= 3
      3657101.08     10596526.41      3656205.28     10596677.44
      3655106.29     10596323.26
#Sta/Elev= 30
  3986.2  373.67  4036.2  374.14  4041.2   373.2  4048.5  374.22  4089.1  374.29
  4149.9  373.35  4170.2  371.49  4190.5  368.49  4200.7  365.65  4210.8  365.03
  4217.7  362.51  4231.1  361.17  4276.6  350.69  4278.2  350.46  4283.2  350.75
  4302.1     347  4322.3  345.77  4335.7  342.52  4338.4  342.02  4341.7  342.52
  5581.4  342.52  5619.8  345.61  5646.6  350.44  5657.1  350.88  5667.6  353.66
  5683.9  355.51  5780.1     363  5876.2  363.96  5977.7  368.42  6049.3  370.11
#Mann= 5 ,-1 , 0
  3986.2     .16       0  4276.6     .05       0  4335.7    .033       0
  4341.7     .05       0  5581.4     .16       0
Bank Sta=4278.2,5646.6
XS Rating Curve= 0 ,0
Exp/Cntr=0.3,0.1

Type RM Length L Ch R = 1 ,28704   ,491,491,491
BEGIN DESCRIPTION:
JELLY SLOUGH 56.0
END DESCRIPTION:
XS GIS Cut Line= 3
      3657049.61     10596360.19      3656149.61     10596360.19
      3655349.61     10595760.19
#Sta/Elev= 30
  4085.9  376.96  4115.9  376.15  4135.9  373.74  4155.9  368.83  4165.9  367.36
  4175.9  364.56  4213.6  358.93  4225.9  357.54  4235.9  354.65  4265.9  350.65
  4295.9  346.74  4312.5  346.26  4325.9  345.36  4332.9  342.52  4335.7  342.02
  4338.9  342.52  5493.2  342.52  5518.7  344.61  5578.6  344.99  5585.9  346.21
  5593.2  346.45  5635.9  346.11  5699.4  350.23  5729.7   352.8  5775.7  357.17
  5807.8  359.58    5864   365.5  5899.4  367.32  5907.8  368.35  5985.9  371.65
#Mann= 8 ,-1 , 0
  4085.9     .05       0  4213.6     .08       0  4312.5     .05       0
  4332.9    .033       0  4338.9     .05       0  5518.7     .16       0
  5729.7     .05       0  5775.7     .16       0
Bank Sta=4265.9,5699.4
XS Rating Curve= 0 ,0
Exp/Cntr=0.3,0.1

Type RM Length L Ch R = 1 ,28213   ,449,449,449
BEGIN DESCRIPTION:
JELLY SLOUGH 55.0
END DESCRIPTION:
XS GIS Cut Line= 3
       3657049.6     10595960.19      3656149.61     10595860.19
      3655349.56     10595660.18
#Sta/Elev= 30
  4095.5   375.9  4105.6  376.02  4136.1  371.27  4145.8  370.01  4155.9  366.08
  4207.8  359.92  4226.3  358.35  4236.4  355.89  4246.4  355.07  4276.6  350.12
  4296.7   348.4  4306.9  346.37  4323.9  342.52  4326.7  342.02  4329.9  342.52
  5404.4  342.52  5454.6  342.52  5464.9  344.21  5477.8  344.51  5506.1  347.43
    5519  347.88    5537  350.38  5660.7  362.37    5671  362.86  5691.7  365.36
  5708.5  366.31  5725.2  366.75  5732.9  368.54  5774.1  371.26  5825.7   371.6
#Mann= 8 ,-1 , 0
  4095.5     .05       0  4136.1     .16       0  4207.8     .08       0
  4306.9     .05       0  4323.9    .033       0  4329.9     .05       0
  5404.4     .16       0  5708.5     .05       0
Bank Sta=4276.6,5537
XS Rating Curve= 0 ,0
Exp/Cntr=0.3,0.1

Type RM Length L Ch R = 1 ,27764   ,485,485,485
BEGIN DESCRIPTION:
JELLY SLOUGH 54.0
END DESCRIPTION:
XS GIS Cut Line= 3
      3656999.62     10594810.18      3656199.61     10595410.19
      3655399.64     10595510.18
#Sta/Elev= 30
  3978.1  382.29    4100  378.24  4170.8  373.12  4220.8  370.76    4250  371.35
  4285.4  368.99  4291.7  366.95    4300  367.86  4314.6  366.46  4320.8  363.66
    4350  358.68  4364.6  353.39  4370.8  347.72    4376  348.02  4382.5  348.12
  4385.4   348.1  4391.7  347.78    4397  342.52  4399.7  342.02    4403  342.52
  5411.2  342.52  5441.7  342.52  5542.5  350.11  5602.9   356.5  5630.9  357.49
  5683.6     365  5713.8   364.1  5723.9  367.27  5772.1   369.3  5784.3  369.59
#Mann= 8 ,-1 , 0
  3978.1     .16       0    4376     .08       0  4382.5     .05       0
    4397    .033       0    4403     .05       0  5411.2     .16       0
  5630.9     .05       0  5772.1     .16       0
Bank Sta=4385.4,5542.5
XS Rating Curve= 0 ,0
Exp/Cntr=0.3,0.1

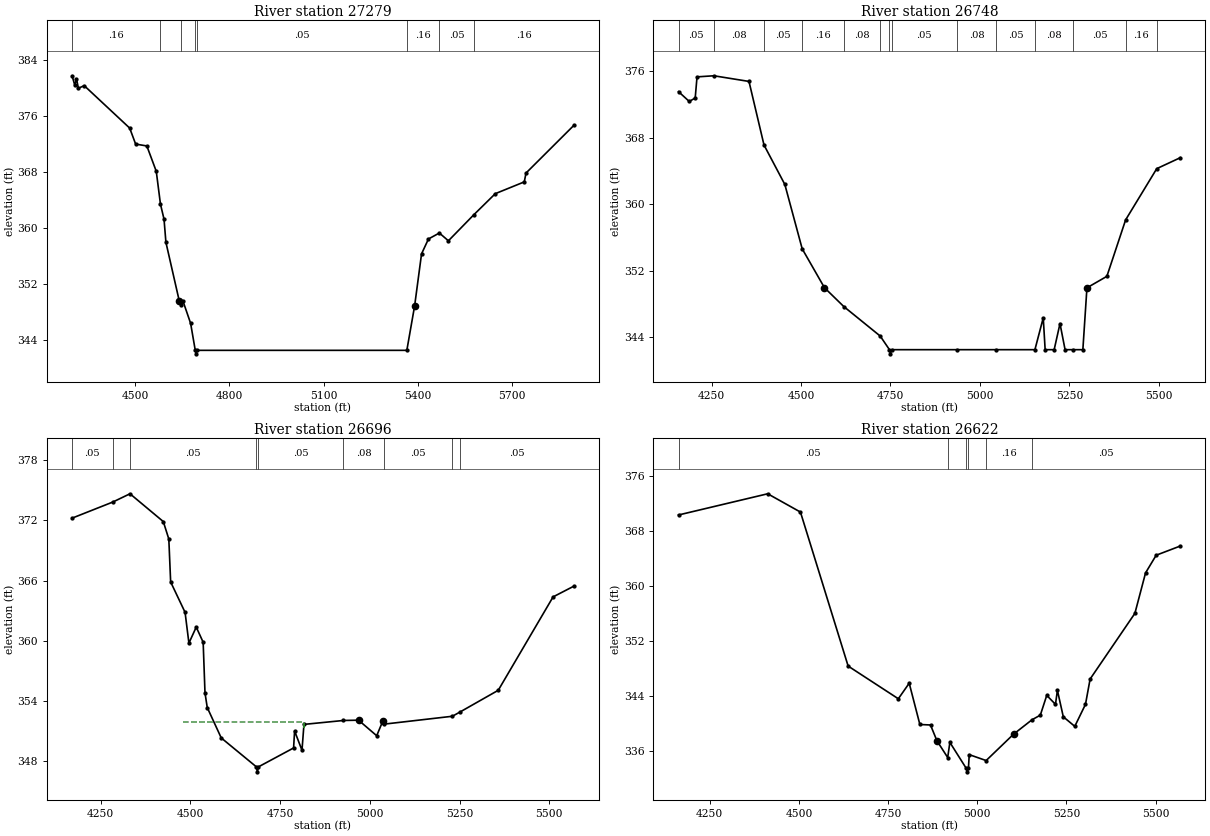
Type RM Length L Ch R = 1 ,27279   ,531,531,531
BEGIN DESCRIPTION:
JELLY SLOUGH 53.0
END DESCRIPTION:
XS GIS Cut Line= 4
      3656908.38     10594750.37      3656434.45     10594932.65
      3656049.03     10594932.65       3655408.4     10594640.98
#Sta/Elev= 30
  4299.7  381.72  4308.4  380.37  4313.8  381.29  4319.8  379.94  4338.4  380.31
  4483.1  374.25    4502  371.97  4537.7   371.7  4567.7  368.08    4581   363.4
  4592.4  361.24  4598.4  357.94  4641.2  349.51  4647.2  349.01  4652.4  349.59
    4677  346.38  4691.8  342.52  4694.6  342.02  4697.8  342.52  5365.2  342.52
    5390  348.87    5412  356.29    5434  358.42  5468.7  359.27  5497.5  358.16
  5578.7  361.89  5646.8  364.89    5739  366.57  5744.5  367.83  5896.8  374.64
#Mann= 8 ,-1 , 0
  4299.7     .16       0    4581     .08       0  4647.2     .05       0
  4691.8    .033       0  4697.8     .05       0  5365.2     .16       0
  5468.7     .05       0  5578.7     .16       0
Bank Sta=4641.2,5390
XS Rating Curve= 0 ,0
Exp/Cntr=0.3,0.1

Type RM Length L Ch R = 1 ,26748   ,52,52,52
BEGIN DESCRIPTION:
JELLY SLOUGH 52.0
END DESCRIPTION:
XS GIS Cut Line= 4
      3657058.98     10594195.43       3656439.2     10594324.33
      3656156.65     10594448.03      3655723.86     10594606.59
#Sta/Elev= 30
  4157.8  373.55  4187.8  372.37  4204.4  372.79  4209.5  375.33  4256.6  375.46
  4354.7  374.78  4396.7  367.13  4454.9  362.39  4503.4  354.65  4565.7  349.97
  4619.6  347.71  4721.4  344.16  4747.3  342.52  4750.1  342.02  4753.3  342.52
  4935.7  342.52  5045.5  342.52  5153.8  342.52  5177.1  346.35  5182.4  342.52
  5207.6  342.52  5223.9  345.66  5238.1  342.52  5260.7  342.52  5287.8  342.52
  5299.2  349.96  5354.9  351.34  5407.3  358.13  5494.3  364.29  5560.2  365.61
#Mann= 14 ,-1 , 0
  4157.8     .05       0  4256.6     .08       0  4396.7     .05       0
  4503.4     .16       0  4619.6     .08       0  4721.4     .05       0
  4747.3     .07       0  4753.3     .05       0  4935.7     .08       0
  5045.5     .05       0  5153.8     .08       0  5260.7     .05       0
  5407.3     .16       0  5494.3     .05       0
Bank Sta=4565.7,5299.2
XS Rating Curve= 0 ,0
Exp/Cntr=0.3,0.1

Type RM Length L Ch R = 1 ,26696   ,74,74,74
BEGIN DESCRIPTION:
Mapping XS 290cb1fb
END DESCRIPTION:
XS GIS Cut Line= 4
       3657038.6     10594140.99      3656429.24     10594265.99
      3656205.28     10594375.36      3655705.31     10594542.02
#Sta/Elev= 30
  4170.1  372.22  4283.2  373.82  4331.5  374.65  4424.3  371.88  4439.7  370.14
  4444.8  365.86    4485  362.83  4495.7  359.76  4516.1  361.36  4535.4  359.85
  4540.5   354.8  4546.8  353.34  4585.8  350.31  4683.6  347.43  4686.4  346.93
  4689.6  347.43  4787.4  349.31  4790.2     351  4810.8  349.08  4816.3  351.66
  4926.2  352.05  4968.4  352.08    5019  350.53    5036  351.99  5038.4  351.68
  5229.8  352.47  5249.9  352.87  5357.7  355.06  5510.5  364.37  5568.4  365.44
#Mann= 9 ,-1 , 0
  4170.1     .05       0  4283.2     .08       0  4331.5     .05       0
  4683.6     .07       0  4689.6     .05       0  4926.2     .08       0
  5038.4     .05       0  5229.8     .08       0  5249.9     .05       0
#XS Ineff= 1 ,-1
 4479.09 4815.45  351.88
Permanent Ineff=
       T
Bank Sta=4968.4,5036
XS Rating Curve= 0 ,0
Exp/Cntr=0.3,0.1

Type RM Length L Ch R = 1 ,26622   ,671,671,671
BEGIN DESCRIPTION:
JELLY SLOUGH 51.0
END DESCRIPTION:
XS GIS Cut Line= 3
      3657044.69     10594082.14       3656436.6     10594204.54
      3655704.03      10594490.8
#Sta/Elev= 30
  4162.5  370.36  4412.5  373.44  4504.3  370.78    4638   348.4  4778.7  343.65
  4809.2  345.91  4839.1  339.91  4868.9  339.84  4886.9  337.55  4917.1  335.11
  4923.2  337.31  4969.2  333.53  4971.9  333.03  4975.2  333.53  4977.5  335.53
  5024.9  334.67  5101.7   338.5  5153.3  340.59  5176.8  341.27  5194.8  344.14
  5219.3  342.84  5224.7  344.88  5241.2  341.03  5273.4  339.64  5303.4  342.84
  5316.4  346.52  5441.9  356.06  5471.8  361.94  5501.6  364.51  5569.3  365.85
#Mann= 6 ,-1 , 0
  4162.5     .05       0  4917.1     .08       0  4969.2     .07       0
  4975.2     .08       0  5024.9     .16       0  5153.3     .05       0
Bank Sta=4886.9,5101.7
XS Rating Curve= 0 ,0
Exp/Cntr=0.3,0.1