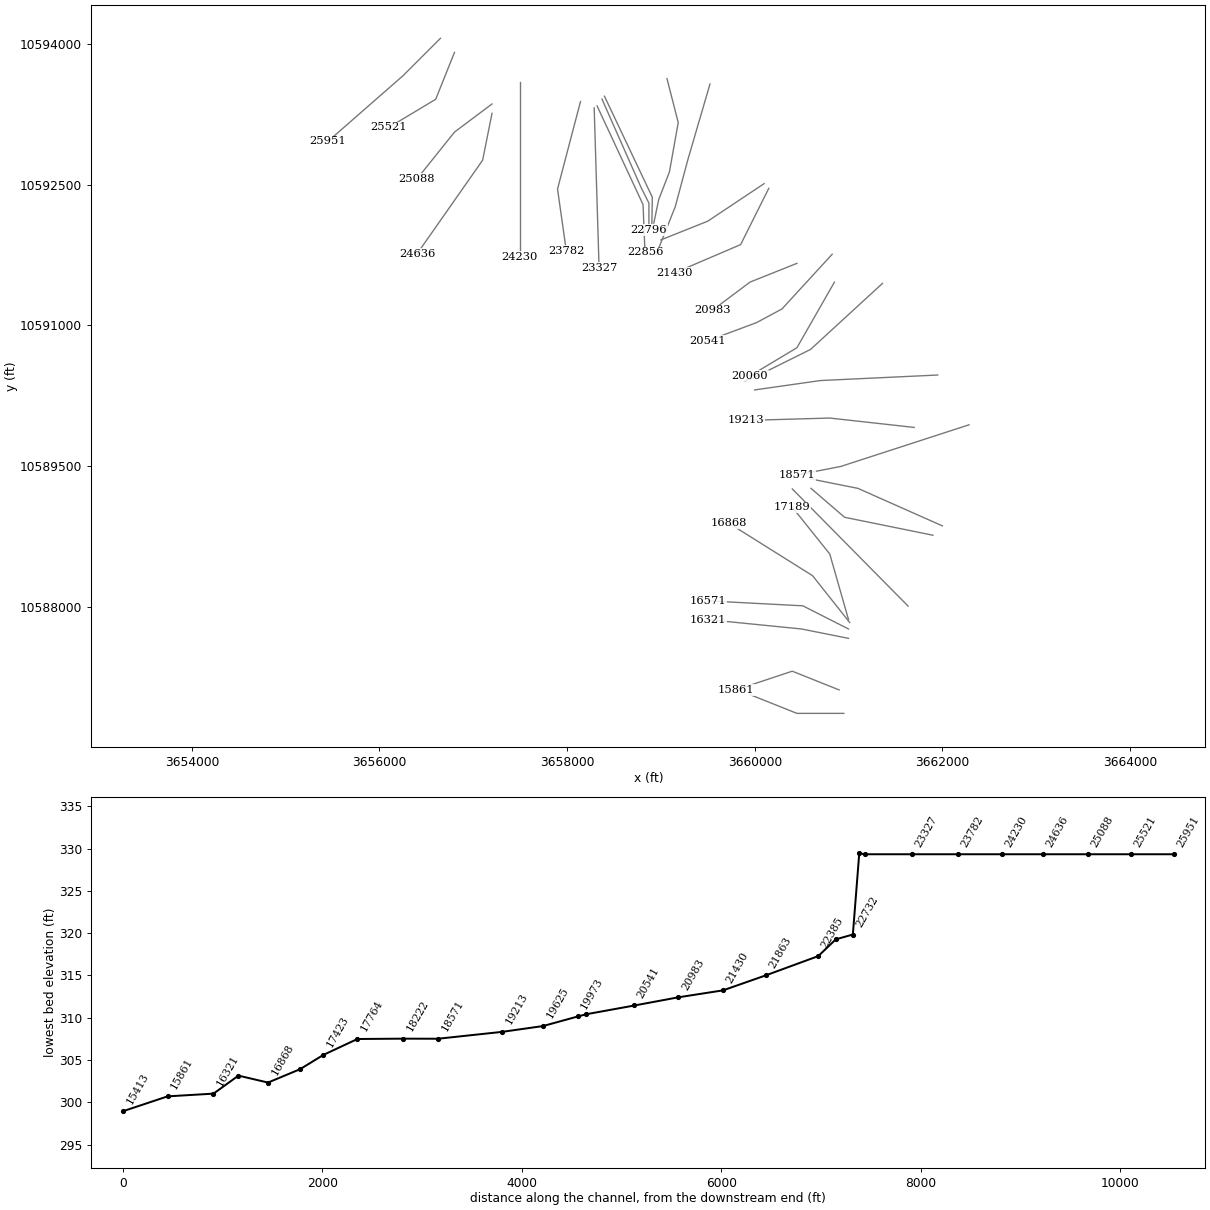
HEC-RAS study JELLY SLOUGH.prj: JELLY SLOUGH Base Level Engineering

--- JELLY SLOUGH.g01 (geometry) --- (continued)

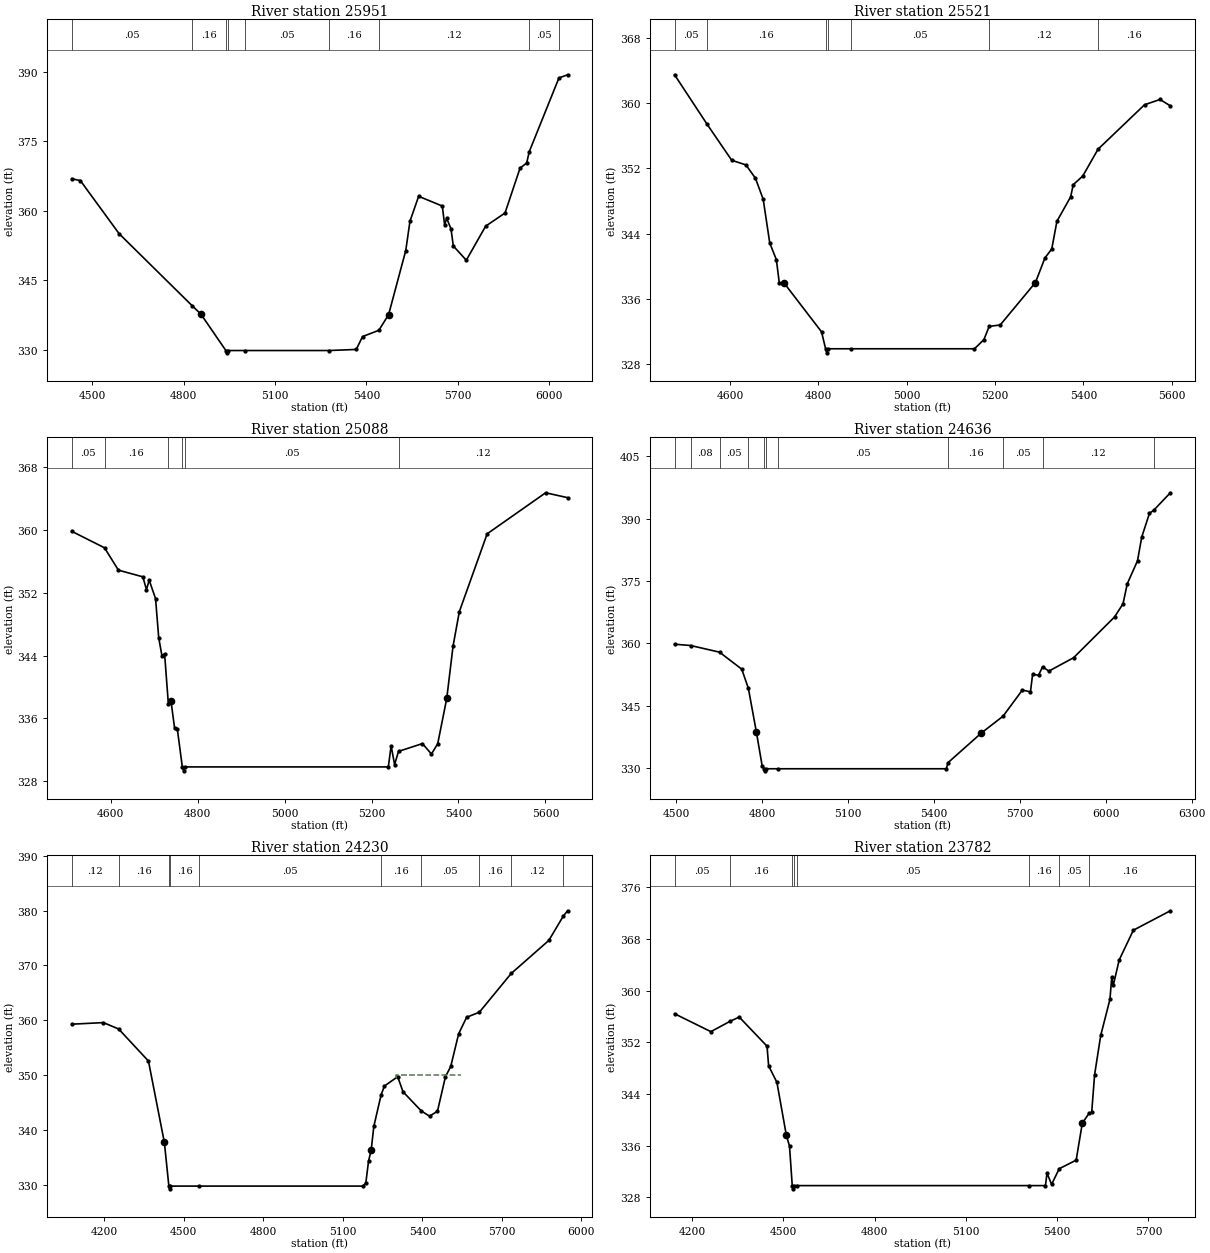
Type RM Length L Ch R = 1 ,25951   ,430,430,430
BEGIN DESCRIPTION:
JELLY SLOUGH 50.0
END DESCRIPTION:
XS GIS Cut Line= 3
      3656649.63     10594060.21      3656249.61     10593660.19
      3655449.64     10592960.21
#Sta/Elev= 30
  4432.2   366.9  4460.5   366.5  4587.8  355.04  4827.4  339.51  4856.5  337.67
  4938.4  329.82  4941.1  329.32  4944.4  329.82  4999.8  329.82  5276.5  329.82
  5366.7  330.05  5387.5  332.84    5441  334.18    5473  337.56  5529.4  351.41
  5543.2  357.72  5571.7  363.12  5649.5  361.01  5657.1  356.92  5663.7  358.36
    5678   356.1  5685.6  352.39  5728.3  349.32  5791.9  356.67  5855.5  359.51
  5904.8  369.19  5926.6   370.3  5935.1  372.75  6032.6  388.66  6060.9  389.35
#Mann= 9 ,-1 , 0
  4432.2     .05       0  4827.4     .16       0  4938.4    .033       0
  4944.4     .16       0  4999.8     .05       0  5276.5     .16       0
    5441     .12       0  5935.1     .05       0  6032.6     .12       0
Bank Sta=4856.5,5473
XS Rating Curve= 0 ,0
Exp/Cntr=0.3,0.1

Type RM Length L Ch R = 1 ,25521   ,433,433,433
BEGIN DESCRIPTION:
JELLY SLOUGH 49.0
END DESCRIPTION:
XS GIS Cut Line= 3
      3656799.62     10593910.23      3656599.61     10593410.19
      3656099.57     10593110.16
#Sta/Elev= 30
  4474.8  363.53  4548.2  357.46  4604.1  353.01  4636.4  352.44  4657.9  350.79
  4675.4   348.2  4690.2  342.82  4705.1  340.79  4711.8  337.91  4722.6  337.91
  4807.4   331.9  4816.5  329.82  4819.2  329.32  4822.5  329.82  4872.9  329.82
  5153.3  329.82  5174.7  330.94  5186.5  332.57  5211.6  332.75  5291.3  337.97
  5312.7  340.99  5328.2   342.1  5339.9  345.51    5371  348.52  5376.8  350.01
  5398.2  351.06  5432.9  354.37  5538.1  359.84  5573.1  360.49  5596.5  359.71
#Mann= 7 ,-1 , 0
  4474.8     .05       0  4548.2     .16       0  4816.5    .033       0
  4822.5     .16       0  4872.9     .05       0  5186.5     .12       0
  5432.9     .16       0
Bank Sta=4722.6,5291.3
XS Rating Curve= 0 ,0
Exp/Cntr=0.3,0.1

Type RM Length L Ch R = 1 ,25088   ,452,452,452
BEGIN DESCRIPTION:
JELLY SLOUGH 48.0
END DESCRIPTION:
XS GIS Cut Line= 3
      3657199.59     10593360.17      3656799.61     10593060.19
       3656399.6     10592560.18
#Sta/Elev= 30
  4510.6  359.84  4585.9  357.74  4617.9  354.89  4674.1  354.04  4682.4  352.41
  4688.7  353.61  4703.3  351.26  4710.6  346.27  4717.9  344.01  4724.1  344.24
  4732.7  337.89  4738.7  338.27    4747  334.79  4753.3  334.67  4764.9  329.82
  4767.6  329.32  4770.9  329.82  5238.7  329.82  5245.1  332.51  5253.1  330.12
  5262.1   331.8  5317.1  332.79  5337.9  331.46  5352.3  332.78  5373.1  338.56
  5387.6  345.23    5402   349.6    5466  359.52  5600.5  364.75  5650.9  364.13
#Mann= 6 ,-1 , 0
  4510.6     .05       0  4585.9     .16       0  4732.7     .05       0
  4764.9    .033       0  4770.9     .05       0  5262.1     .12       0
Bank Sta=4738.7,5373.1
XS Rating Curve= 0 ,0
Exp/Cntr=0.3,0.1

Type RM Length L Ch R = 1 ,24636   ,406,406,406
BEGIN DESCRIPTION:
JELLY SLOUGH 47.0
END DESCRIPTION:
XS GIS Cut Line= 3
       3657199.6     10593260.16      3657099.61     10592760.19
      3656399.63     10591760.21
#Sta/Elev= 30
  4495.1  359.77  4551.2  359.46    4652  357.86  4729.6  353.77  4752.8  349.14
  4780.6  338.68    4801  330.47  4808.2  329.82    4811  329.32  4814.2  329.82
  4855.9  329.82    5444  329.82    5449  331.25    5566  338.42  5641.8  342.47
    5709  348.74  5737.4  348.33  5744.8   352.5  5765.7  352.33  5779.8  354.35
  5801.5   353.3  5887.8  356.52  6030.8  366.32  6060.4  369.49  6075.2  374.29
    6111  379.84  6125.8  385.55  6152.8  391.27  6166.9  391.94  6225.6  396.19
#Mann= 11 ,-1 , 0
  4495.1     .05       0  4551.2     .08       0    4652     .05       0
  4752.8     .16       0  4808.2    .033       0  4814.2     .16       0
  4855.9     .05       0    5449     .16       0  5641.8     .05       0
  5779.8     .12       0  6166.9     .05       0
Bank Sta=4780.6,5566
XS Rating Curve= 0 ,0
Exp/Cntr=0.3,0.1

Type RM Length L Ch R = 1 ,24230   ,448,448,448
BEGIN DESCRIPTION:
JELLY SLOUGH 46.0
END DESCRIPTION:
XS GIS Cut Line= 2
      3657496.95     10593599.37      3657496.95     10591729.57
#Sta/Elev= 30
  4077.6   359.3  4196.8  359.59  4254.3  358.43  4366.8  352.59  4426.8  337.78
  4443.8  329.82  4446.5  329.32  4449.8  329.82  4557.9  329.82  5176.8  329.82
  5186.8  330.44  5196.8  334.36  5206.8  336.38  5216.8   340.7  5244.5  346.47
  5256.8  348.04  5306.8  349.74  5326.8     347  5395.7  343.51  5426.8  342.55
  5456.8  343.45  5486.8  349.72  5506.8   351.6  5536.8  357.57  5566.8  360.56
  5614.8  361.48  5734.9  368.53  5876.8  374.55  5931.1  378.96  5947.4  379.95
#Mann= 10 ,-1 , 0
  4077.6     .12       0  4254.3     .16       0  4443.8    .033       0
  4449.8     .16       0  4557.9     .05       0  5244.5     .16       0
  5395.7     .05       0  5614.8     .16       0  5734.9     .12       0
  5931.1     .16       0
#XS Ineff= 1 ,-1
 5298.86 5546.59  349.96
Permanent Ineff=
       F
Bank Sta=4426.8,5206.8
XS Rating Curve= 0 ,0
Exp/Cntr=0.3,0.1

Type RM Length L Ch R = 1 ,23782   ,455,455,455
BEGIN DESCRIPTION:
JELLY SLOUGH 45.0
END DESCRIPTION:
XS GIS Cut Line= 3
      3658142.79     10593385.78      3657897.99     10592453.49
      3657991.52     10591793.58
#Sta/Elev= 30
  4141.8  356.41  4261.3  353.64  4323.5  355.22  4354.4   355.9  4445.9  351.39
  4451.1  348.36  4478.4  345.79  4509.4  337.61  4519.8  335.94  4528.8  329.82
  4531.6  329.32  4534.8  329.82  4544.7  329.82  5308.2  329.82  5361.5  329.82
  5366.6  331.75  5381.7     330  5406.7  332.43  5462.5  333.76  5482.7  339.48
  5505.2  341.02  5513.6  341.14  5523.1  346.98  5543.3  353.06  5573.6  358.64
  5579.5  362.08  5584.6  360.81  5603.9  364.72  5650.5  369.33  5772.2  372.34
#Mann= 8 ,-1 , 0
  4141.8     .05       0  4323.5     .16       0  4528.8    .033       0
  4534.8     .16       0  4544.7     .05       0  5308.2     .16       0
  5406.7     .05       0  5505.2     .16       0
Bank Sta=4509.4,5482.7
XS Rating Curve= 0 ,0
Exp/Cntr=0.3,0.1

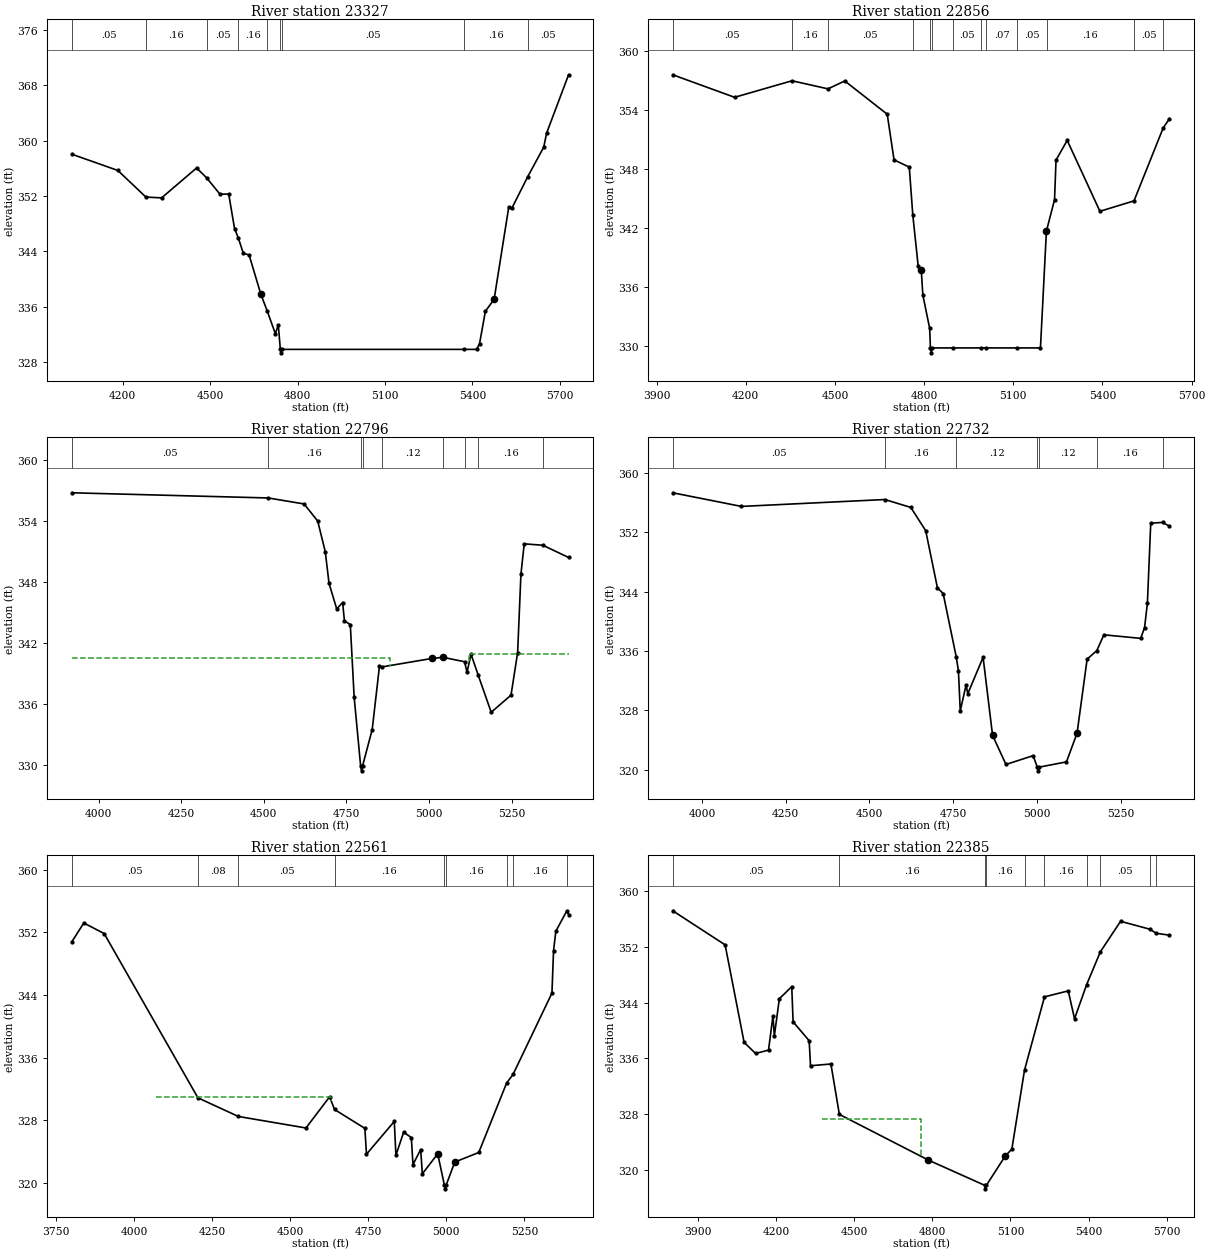
Type RM Length L Ch R = 1 ,23327   ,471,471,471
BEGIN DESCRIPTION:
Mapping XS 7a32266a
END DESCRIPTION:
XS GIS Cut Line= 2
      3658288.62     10593318.03       3658340.7     10591615.02
#Sta/Elev= 30
  4025.9  358.03  4183.8  355.68  4280.1  351.83  4333.9  351.72  4453.9  356.04
    4488  354.63    4534  352.25    4564  352.27    4584  347.29  4597.3  345.88
    4614  343.73    4634  343.46    4674  337.82  4696.3  335.34  4724.1  332.08
  4734.1  333.37  4741.1  329.82  4743.8  329.32  4747.1  329.82  5370.1  329.82
  5414.4  329.82  5424.4  330.66  5444.4  335.33  5474.4  337.06  5524.4  350.34
    5535  350.21  5589.9   354.8  5644.5  359.05  5654.5  361.09  5729.7  369.51
#Mann= 9 ,-1 , 0
  4025.9     .05       0  4280.1     .16       0    4488     .05       0
  4597.3     .16       0  4696.3     .05       0  4741.1    .033       0
  4747.1     .05       0  5370.1     .16       0  5589.9     .05       0
Bank Sta=4674,5474.4
XS Rating Curve= 0 ,0
Exp/Cntr=0.3,0.1

Type RM Length L Ch R = 1 ,22856   ,60,60,60
BEGIN DESCRIPTION:
JELLY SLOUGH 44.0
END DESCRIPTION:
XS GIS Cut Line= 3
      3658319.89     10593338.86      3658809.45     10592286.82
      3658830.28     10591776.42
#Sta/Elev= 30
  3954.2  357.59  4162.3   355.3  4355.4  356.98  4476.4  356.16    4533  356.96
  4675.8  353.58  4698.7  348.94    4750   348.2  4761.7  343.38    4780  338.11
  4790.2  337.76  4795.7  335.18  4818.6  331.81  4821.1  329.82  4823.9  329.32
  4827.1  329.82  4897.9  329.82  4991.6  329.82  5007.7  329.82    5114  329.82
  5191.3  329.82  5211.3  341.69    5212  341.77  5238.7   344.9  5243.7  348.92
  5281.3  350.92  5391.4  343.71    5506  344.77    5604  352.17  5625.4  353.13
#Mann= 13 ,-1 , 0
  3954.2     .05       0  4355.4     .16       0  4476.4     .05       0
  4761.7     .16       0  4821.1     .07       0  4827.1     .16       0
  4897.9     .05       0  4991.6     .12       0  5007.7     .07       0
    5114     .05       0    5212     .16       0    5506     .05       0
    5604     .08       0
Bank Sta=4790.2,5211.3
XS Rating Curve= 0 ,0
Exp/Cntr=0.3,0.1

Type RM Length L Ch R = 1 ,22796   ,64,64,64
BEGIN DESCRIPTION:
JELLY SLOUGH 43.0
END DESCRIPTION:
XS GIS Cut Line= 4
      3658371.95     10593411.83      3658788.62     10592469.11
      3658871.95     10592302.44      3658871.95     10592015.98
#Sta/Elev= 30
  3918.9  356.76  4513.3  356.25    4622  355.66  4663.1  353.98    4686  350.97
  4697.4  347.85  4720.7  345.34  4738.5  345.97    4744  344.17  4761.8   343.8
  4773.5  336.64    4793  329.92  4795.8  329.42    4799  329.92  4828.1  333.48
    4850   339.7  4857.9  339.64  5008.8  340.47  5042.2  340.58  5107.5  340.15
    5115  339.13  5127.3  340.88  5148.6  338.86  5188.2  335.18  5248.2  336.86
  5268.2  341.04  5278.2  348.74  5288.2  351.74  5344.7   351.6  5422.4   350.4
#Mann= 9 ,-1 , 0
  3918.9     .05       0  4513.3     .16       0    4793     .07       0
    4799     .16       0  4857.9     .12       0  5042.2     .07       0
  5107.5     .12       0  5148.6     .16       0  5344.7     .05       0
#XS Ineff= 2 , 0
       0 4881.02  340.51 5122.39       0  340.94
Permanent Ineff=
       T       T
Bank Sta=5008.8,5042.2
XS Rating Curve= 0 ,0
Exp/Cntr=0.3,0.1

Type RM Length L Ch R = 1 ,22732   ,171,171,171
BEGIN DESCRIPTION:
Mapping XS f2ebc4ba
END DESCRIPTION:
XS GIS Cut Line= 3
      3658398.01     10593443.04      3658908.41     10592364.94
      3658903.22      10592074.2
#Sta/Elev= 30
  3912.6  357.34  4117.7   355.5  4546.2  356.43  4623.7  355.36  4668.1  352.23
    4703  344.54  4720.3  343.74  4759.3   335.2  4765.8  333.34  4771.3  327.92
  4788.5  331.36    4794  330.26  4839.5  335.14  4867.8  324.62  4907.8  320.69
    4989  321.88  5001.3  320.33  5004.1  319.83  5007.3  320.33  5088.5  321.04
  5120.2  324.92  5150.2   334.9  5179.2  336.05  5200.2  338.18  5310.2   337.7
  5321.7  339.15  5330.2  342.42  5340.2  353.24  5375.5  353.34  5396.2  352.83
#Mann= 7 ,-1 , 0
  3912.6     .05       0  4546.2     .16       0  4759.3     .12       0
  5001.3     .07       0  5007.3     .12       0  5179.2     .16       0
  5375.5     .05       0
Bank Sta=4867.8,5120.2
XS Rating Curve= 0 ,0
Exp/Cntr=0.3,0.1

Type RM Length L Ch R = 1 ,22561   ,176,176,176
BEGIN DESCRIPTION:
Mapping XS ef7c8048
END DESCRIPTION:
XS GIS Cut Line= 5
      3659064.66     10593630.58      3659184.45     10593161.82
       3659090.7     10592635.78      3658976.12      10592338.9
      3658924.33     10592090.31
#Sta/Elev= 30
    3801   350.8  3839.4   353.2  3904.6  351.85  4204.7  330.88  4334.1   328.5
  4550.6  327.03  4626.3  331.01    4642  329.39  4739.2  326.98  4744.3  323.68
  4833.3  327.86  4838.6  323.55  4863.3  326.49  4887.9  325.81  4893.2  322.36
  4917.8  324.28  4923.2  321.18  4972.4  323.73  4993.6  319.76  4996.4  319.26
  4999.6  319.76    5027  322.68  5103.8   323.9    5193  332.77  5213.5  333.86
  5338.1  344.25  5343.2  349.68  5350.6  352.15  5385.8  354.76  5391.3  354.27
#Mann= 9 ,-1 , 0
    3801     .05       0  4204.7     .08       0  4334.1     .05       0
    4642     .16       0  4993.6     .07       0  4999.6     .16       0
    5193     .05       0  5213.5     .16       0  5385.8     .05       0
#XS Ineff= 1 ,-1
 4071.82 4630.91  331.02
Permanent Ineff=
       F
Bank Sta=4972.4,5027
XS Rating Curve= 0 ,0
Exp/Cntr=0.3,0.1

Type RM Length L Ch R = 1 ,22385   ,522,522,522
BEGIN DESCRIPTION:
JELLY SLOUGH 42.0
END DESCRIPTION:
XS GIS Cut Line= 4
      3659522.99     10593573.28      3659288.62     10592771.19
       3659153.2     10592265.99      3658950.08     10591755.59
#Sta/Elev= 30
  3802.8  357.17    4004  352.28  4076.9   338.3  4120.8   336.7  4170.7  337.18
  4187.8  342.11    4193   339.2  4212.3  344.55  4259.9  346.29  4265.1  341.24
  4326.8  338.53    4332  334.94  4410.3  335.19  4442.8  327.96  4784.4  321.41
  5001.3  317.78    5004  317.28  5007.3  317.78  5079.1  321.94  5105.4  322.99
    5154  334.32  5230.7  344.82  5321.9  345.68  5346.1  341.68  5392.5  346.57
  5445.1  351.27  5522.9  355.66  5636.1  354.52  5659.6  353.94  5710.8  353.67
#Mann= 10 ,-1 , 0
  3802.8     .05       0  4442.8     .16       0  5001.3     .07       0
  5007.3     .16       0    5154     .12       0  5230.7     .16       0
  5392.5     .08       0  5445.1     .05       0  5636.1     .08       0
  5659.6     .05       0
#XS Ineff= 1 ,-1
 4376.42 4755.68  327.33
Permanent Ineff=
       F
Bank Sta=4784.4,5079.1
XS Rating Curve= 0 ,0
Exp/Cntr=0.3,0.1

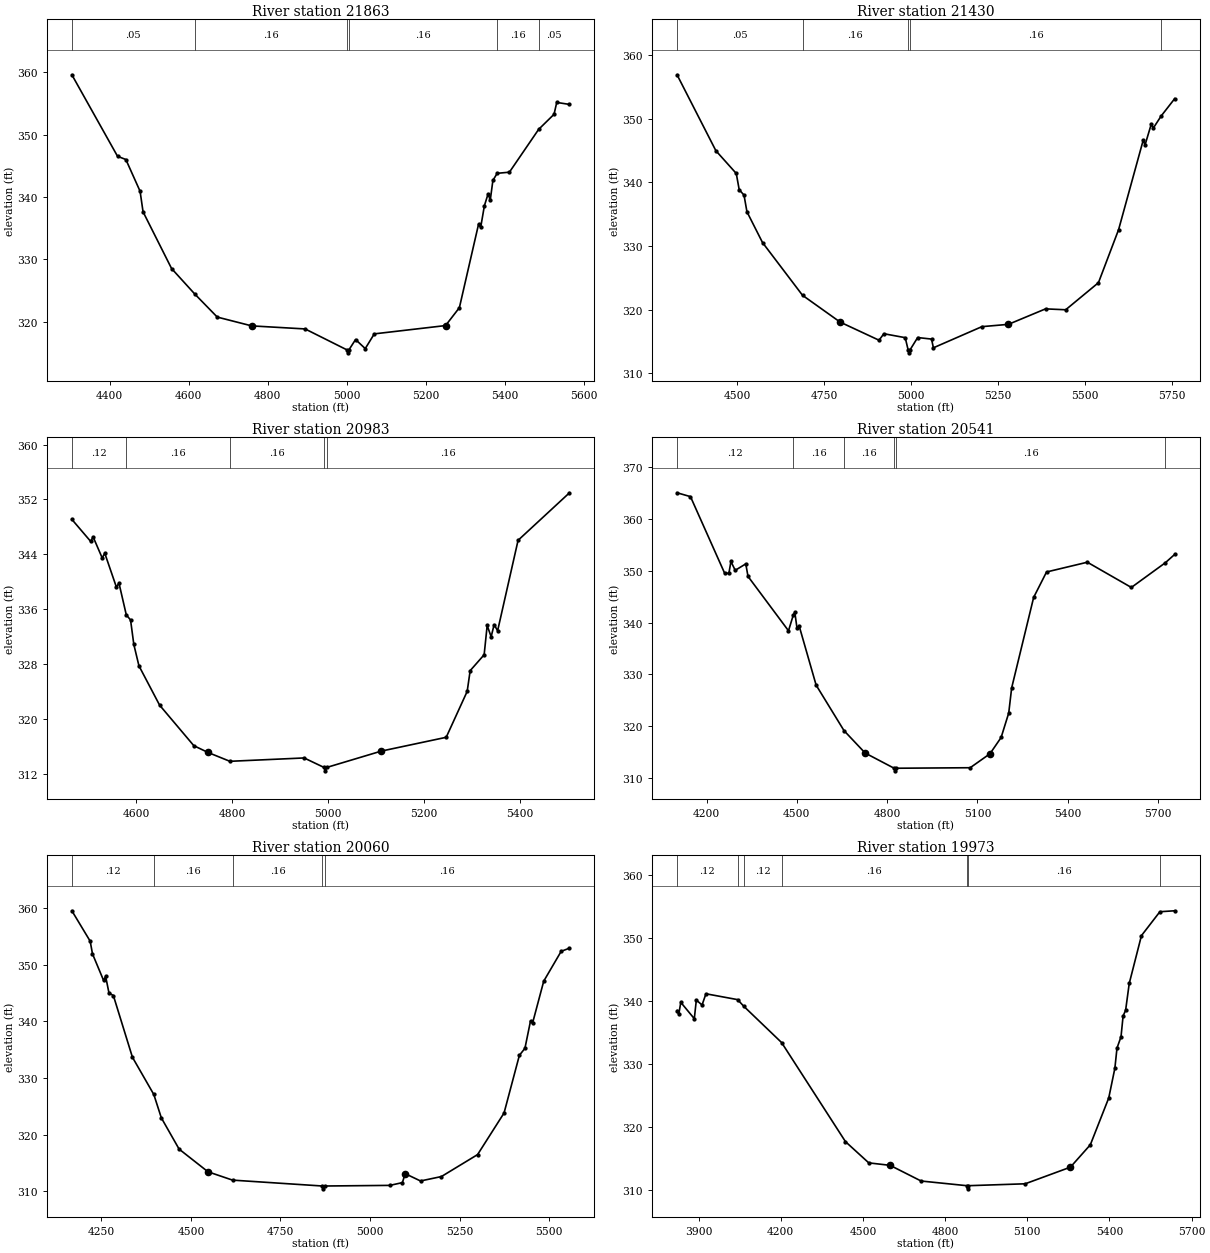
Type RM Length L Ch R = 1 ,21863   ,433,433,433
BEGIN DESCRIPTION:
JELLY SLOUGH 41.0
END DESCRIPTION:
XS GIS Cut Line= 3
      3660099.58     10592510.17      3659499.61     10592110.19
       3658999.6     10591910.18
#Sta/Elev= 30
    4304  359.58  4419.6  346.52  4440.7     346  4476.7  340.91  4484.2  337.62
  4556.4  328.53  4614.9  324.46    4672  320.75  4759.2  319.34  4894.4  318.85
  4999.5  315.52  5002.3  315.02  5005.5  315.52  5022.1  317.15  5046.6   315.7
  5069.5  318.06  5249.9  319.39  5284.9  322.26  5333.4  335.63  5338.8  335.13
  5348.2   338.6  5357.6   340.5    5363  339.46  5369.7  342.65  5380.6  343.79
  5411.5  343.97  5485.5  350.83  5524.5  353.25  5531.3  355.15  5563.6  354.83
#Mann= 6 ,-1 , 0
    4304     .05       0  4614.9     .16       0  4999.5     .07       0
  5005.5     .16       0  5380.6     .16       0  5485.5     .05       0
Bank Sta=4759.2,5249.9
XS Rating Curve= 0 ,0
Exp/Cntr=0.3,0.1

Type RM Length L Ch R = 1 ,21430   ,447,447,447
BEGIN DESCRIPTION:
JELLY SLOUGH 40.0
END DESCRIPTION:
XS GIS Cut Line= 3
       3660149.6     10592460.17      3659849.61     10591860.19
      3659149.59     10591560.18
#Sta/Elev= 30
  4326.5  356.87  4438.3  344.95    4497  341.38  4505.4  338.84  4519.3  337.98
  4527.7  335.37  4572.5  330.54  4687.7  322.26  4796.1  318.05  4907.9  315.21
  4921.8  316.23  4983.3  315.61  4991.5  313.73  4994.3  313.23  4997.5  313.73
  5019.1  315.63    5059  315.39  5064.4  314.02    5204  317.34  5280.2   317.7
  5387.2  320.13  5445.2  319.99  5539.5  324.24  5597.5  332.57  5668.2  346.58
  5673.7  345.87  5691.8  349.18  5697.2  348.49  5720.1  350.41  5758.9  353.12
#Mann= 5 ,-1 , 0
  4326.5     .05       0  4687.7     .16       0  4991.5     .07       0
  4997.5     .16       0  5720.1     .16       0
Bank Sta=4796.1,5280.2
XS Rating Curve= 0 ,0
Exp/Cntr=0.3,0.1

Type RM Length L Ch R = 1 ,20983   ,442,442,442
BEGIN DESCRIPTION:
JELLY SLOUGH 39.0
END DESCRIPTION:
XS GIS Cut Line= 3
      3660449.63      10591660.2      3659949.61     10591460.19
      3659549.64     10591160.21
#Sta/Elev= 30
  4465.8  349.08  4504.9  345.88  4510.2  346.52  4529.1  343.46  4534.5  344.14
  4558.7  339.21  4564.1  339.79  4579.4  335.15  4588.3  334.41  4595.1  330.84
  4605.8  327.72  4648.9  321.99  4720.3  316.08  4749.9  315.09  4795.6   313.8
  4950.5  314.29  4991.9  312.91  4994.7  312.41  4997.9  312.91  5111.6  315.29
    5247   317.3  5290.8     324    5297  327.02  5326.2  329.34  5332.5  333.61
  5340.8  331.96    5347  333.73  5354.3  332.84    5397  346.03  5504.3  352.96
#Mann= 5 ,-1 , 0
  4465.8     .12       0  4579.4     .16       0  4795.6     .16       0
  4991.9     .07       0  4997.9     .16       0
Bank Sta=4749.9,5111.6
XS Rating Curve= 0 ,0
Exp/Cntr=0.3,0.1

Type RM Length L Ch R = 1 ,20541   ,481,481,481
BEGIN DESCRIPTION:
JELLY SLOUGH 38.0
END DESCRIPTION:
XS GIS Cut Line= 4
      3660825.37     10591757.38      3660290.67     10591174.08
      3660019.84     10591028.24      3659500.82     10590834.48
#Sta/Elev= 30
  4102.1  364.98  4146.7  364.24  4260.2  349.49  4274.3  349.47  4281.1  351.75
  4295.3  350.05  4330.4  351.29  4337.8  348.88  4472.3  338.41    4488  341.39
  4493.2     342  4500.6  338.89  4507.4   339.4  4564.1  327.94  4656.6  319.19
  4726.9  314.87  4823.2  311.94    4826  311.44  4829.2  311.94  5075.8  312.04
  5141.5  314.73  5178.5  317.86  5203.8  322.58  5213.5   327.4  5286.6  344.84
  5329.4  349.73  5464.9  351.61  5611.1  346.75  5723.8   351.5    5755  353.11
#Mann= 6 ,-1 , 0
  4102.1     .12       0    4488     .16       0  4656.6     .16       0
  4823.2     .07       0  4829.2     .16       0  5723.8     .05       0
Bank Sta=4726.9,5141.5
XS Rating Curve= 0 ,0
Exp/Cntr=0.3,0.1

Type RM Length L Ch R = 1 ,20060   ,87,87,87
BEGIN DESCRIPTION:
JELLY SLOUGH 37.0
END DESCRIPTION:
XS GIS Cut Line= 3
       3660849.6     10591460.17      3660449.61     10590760.19
      3659949.61     10590460.19
#Sta/Elev= 30
  4167.6  359.54  4218.7  354.17  4225.2  351.93  4256.1  347.24  4261.9  347.95
  4271.2  345.02  4283.5  344.56  4336.7  333.66  4396.4  327.08  4417.4  322.95
    4467  317.43  4547.7  313.42  4616.2  311.95  4867.1  310.91  4869.9  310.41
  4873.1  310.91  5055.4  311.02  5090.4  311.51  5098.2  313.09    5141   311.8
  5199.3  312.58  5300.3  316.46  5374.2  323.81    5417     334  5432.5  335.24
  5448.1  340.08  5453.9  339.72    5485  347.11  5533.6  352.37  5556.9  352.94
#Mann= 5 ,-1 , 0
  4167.6     .12       0  4396.4     .16       0  4616.2     .16       0
  4867.1     .07       0  4873.1     .16       0
Bank Sta=4547.7,5098.2
XS Rating Curve= 0 ,0
Exp/Cntr=0.3,0.1

Type RM Length L Ch R = 1 ,19973   ,348,348,348
BEGIN DESCRIPTION:
Mapping XS 269879c1
END DESCRIPTION:
XS GIS Cut Line= 4
      3661362.01     10591446.86      3660594.69     10590742.03
      3659952.32     10590422.58      3659896.75     10590408.69
#Sta/Elev= 30
  3821.5  338.42  3827.8  337.85  3835.2  339.73  3884.5  337.14  3891.9  340.09
  3912.8  339.31    3927  341.09  4042.8  340.16  4064.8  339.12  4203.2  333.35
  4436.3  317.63  4521.4  314.26  4599.1  313.87  4712.5  311.38  4879.3  310.64
    4882  310.14  4885.3  310.64  5092.4  310.94  5257.5  313.58  5330.2  317.13
  5397.4  324.56  5419.8  329.28  5427.5  332.47  5442.2  334.27  5449.8  337.57
    5459  338.47  5472.2  342.73  5516.8  350.32  5584.1  354.11  5638.1  354.26
#Mann= 7 ,-1 , 0
  3821.5     .12       0  4042.8     .16       0  4064.8     .12       0
  4203.2     .16       0  4879.3     .07       0  4885.3     .16       0
  5584.1     .16       0
Bank Sta=4599.1,5257.5
XS Rating Curve= 0 ,0
Exp/Cntr=0.3,0.1

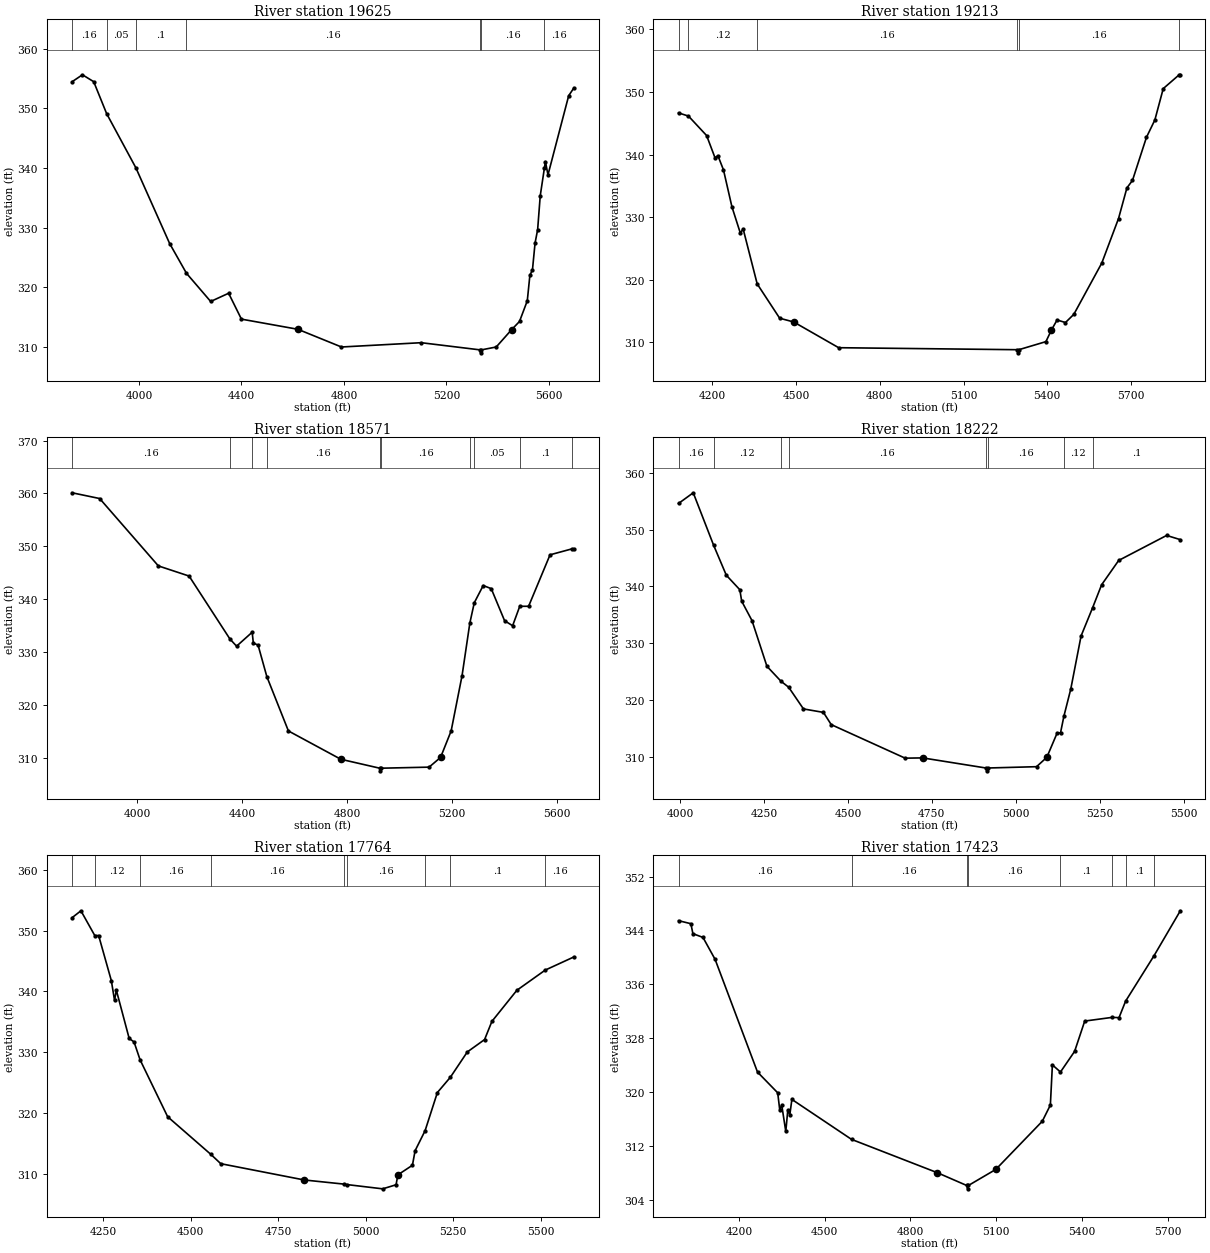
Type RM Length L Ch R = 1 ,19625   ,412,412,412
BEGIN DESCRIPTION:
JELLY SLOUGH 36.0
END DESCRIPTION:
XS GIS Cut Line= 3
       3661950.1     10590469.11      3660699.61     10590410.19
      3659999.59     10590310.19
#Sta/Elev= 30
  3738.6  354.46  3779.1  355.63  3823.1  354.47  3873.6  349.11  3987.6  340.04
  4119.5  327.34  4185.2  322.35  4279.7  317.62  4349.8     319  4399.8  314.66
  4620.1  312.96  4790.3  309.99  5101.6  310.71  5330.9  309.51  5333.7  309.01
  5336.9  309.51  5394.5  309.99  5455.1  312.92  5485.4  314.27  5515.8  317.74
  5525.9  322.01    5536  322.93  5546.1  327.41  5556.2  329.67  5566.3  335.33
  5582.5  339.96  5586.5  341.08  5596.6  338.85  5677.4  352.12  5697.6  353.42
#Mann= 7 ,-1 , 0
  3738.6     .16       0  3873.6     .05       0  3987.6      .1       0
  4185.2     .16       0  5330.9     .07       0  5336.9     .16       0
  5582.5     .16       0
Bank Sta=4620.1,5455.1
XS Rating Curve= 0 ,0
Exp/Cntr=0.3,0.1

Type RM Length L Ch R = 1 ,19213   ,642,642,642
BEGIN DESCRIPTION:
JELLY SLOUGH 35.0
END DESCRIPTION:
XS GIS Cut Line= 3
       3661699.6     10589910.19      3660799.61     10590010.19
       3659908.4     10589984.73
#Sta/Elev= 30
  4079.3  346.65  4114.9  346.14  4179.9  343.03  4210.1  339.46  4220.2  339.83
  4240.3  337.54  4270.5  331.65  4300.6  327.45  4310.7  328.11    4361  319.33
  4441.5  313.85  4491.8  313.25  4652.8  309.14    5292  308.82  5294.7  308.32
    5298  308.82    5395  310.11    5415  311.98    5435  313.57    5465  313.16
    5495  314.47  5595.1  322.66  5655.1  329.78  5685.1  334.67  5705.1  335.87
  5755.1  342.75  5785.2  345.52  5815.2  350.53  5871.3   352.7  5876.4  352.74
#Mann= 6 ,-1 , 0
  4079.3     .16       0  4114.9     .12       0    4361     .16       0
    5292     .07       0    5298     .16       0  5871.3     .16       0
Bank Sta=4491.8,5415
XS Rating Curve= 0 ,0
Exp/Cntr=0.3,0.1

Type RM Length L Ch R = 1 ,18571   ,349,349,349
BEGIN DESCRIPTION:
JELLY SLOUGH 34.0
END DESCRIPTION:
XS GIS Cut Line= 3
      3662283.77     10589937.98      3660915.67     10589493.52
      3660450.44     10589403.25
#Sta/Elev= 30
  3752.5  360.13  3857.7  359.04  4081.4  346.29  4198.5  344.37  4354.1  332.46
  4379.5   331.1  4438.9  333.74  4443.4  331.67  4461.3  331.32  4494.8  325.34
    4577  315.06  4776.8   309.7    4925  308.01  4927.7  307.51    4931  308.01
  5113.2  308.21  5156.9  310.05  5197.2  315.06  5238.9  325.55  5268.5  335.49
  5285.4  339.32  5319.4  342.58    5350  341.99  5400.9  335.92  5431.5  334.97
  5458.7  338.65  5492.4  338.65  5574.1  348.39  5658.7  349.53  5664.9  349.51
#Mann= 10 ,-1 , 0
  3752.5     .16       0  4354.1     .12       0  4438.9     .16       0
  4494.8     .16       0    4925     .07       0    4931     .16       0
  5268.5     .12       0  5285.4     .05       0  5458.7      .1       0
  5658.7     .05       0
Bank Sta=4776.8,5156.9
XS Rating Curve= 0 ,0
Exp/Cntr=0.3,0.1

Type RM Length L Ch R = 1 ,18222   ,458,458,458
BEGIN DESCRIPTION:
JELLY SLOUGH 33.0
END DESCRIPTION:
XS GIS Cut Line= 3
      3661999.63     10588860.18      3661099.61     10589260.19
      3660599.62     10589360.19
#Sta/Elev= 30
  3995.5  354.59  4039.3  356.47  4100.1  347.22  4137.8  341.96  4178.1   339.4
  4183.6  337.39  4214.4  333.96  4258.8  325.93  4300.4  323.31  4323.7  322.23
  4367.6  318.42  4427.1  317.81  4450.3  315.66  4670.6  309.75  4722.6   309.8
  4911.1  308.02  4913.8  307.52  4917.1  308.02    5062  308.25  5092.6   309.9
  5123.2  314.16  5133.4  314.21  5143.6  317.17    5164  321.93  5194.6  331.26
  5228.9  336.22  5255.8  340.27  5306.7  344.56  5449.5  348.96  5490.3  348.22
#Mann= 8 ,-1 , 0
  3995.5     .16       0  4100.1     .12       0  4300.4     .16       0
  4323.7     .16       0  4911.1     .07       0  4917.1     .16       0
  5143.6     .12       0  5228.9      .1       0
Bank Sta=4722.6,5092.6
XS Rating Curve= 0 ,0
Exp/Cntr=0.3,0.1

Type RM Length L Ch R = 1 ,17764   ,341,341,341
BEGIN DESCRIPTION:
JELLY SLOUGH 32.0
END DESCRIPTION:
XS GIS Cut Line= 3
      3661899.58     10588760.19      3660957.34     10588951.85
      3660599.62     10589260.18
#Sta/Elev= 30
  4161.1  352.11  4186.4  353.25    4226  349.17    4237  349.18  4273.3  341.75
  4282.5  338.49  4287.6  340.18  4324.3  332.23  4338.2  331.66  4355.4  328.72
  4434.2  319.35  4557.9  313.14    4586  311.62  4824.4  308.94  4937.8  308.26
  4946.8  308.18  5048.6  307.48  5086.9  308.15    5092  309.78  5133.6  311.36
  5141.3  313.76  5169.8  317.05  5204.9  323.33  5242.2  325.86  5290.4  330.01
  5339.8  332.05  5360.7  335.04    5432  340.16  5513.2  343.49  5594.9  345.65
#Mann= 9 ,-1 , 0
  4161.1     .16       0    4226     .12       0  4355.4     .16       0
  4557.9     .16       0  4937.8     .07       0  4946.8     .16       0
  5169.8     .12       0  5242.2      .1       0  5513.2     .16       0
Bank Sta=4824.4,5092
XS Rating Curve= 0 ,0
Exp/Cntr=0.3,0.1

Type RM Length L Ch R = 1 ,17423   ,234,234,234
BEGIN DESCRIPTION:
Mapping XS ebe22fbe
END DESCRIPTION:
XS GIS Cut Line= 2
      3661634.64     10588004.16      3660400.23     10589254.19
#Sta/Elev= 30
    3988  345.45  4031.2     345  4038.3  343.52  4073.6  342.96    4116   339.7
  4264.5  322.95  4335.2  319.87  4342.3  317.34  4349.3  318.04  4363.5  314.13
  4370.6  317.33  4377.6  316.59  4384.8  318.89  4593.7  312.95  4893.9     308
  4996.9   306.1  4999.7   305.6  5002.9   306.1  5098.9  308.49  5261.5  315.64
  5289.8  318.05  5296.9  324.02  5325.2  322.96  5374.7  326.03  5410.1  330.53
  5506.2  331.08  5530.2  331.04  5553.2  333.49  5652.7  340.24  5744.8  346.92
#Mann= 8 ,-1 , 0
    3988     .16       0  4593.7     .16       0  4996.9     .07       0
  5002.9     .16       0  5325.2      .1       0  5506.2     .16       0
  5553.2      .1       0  5652.7     .16       0
Bank Sta=4893.9,5098.9
XS Rating Curve= 0 ,0
Exp/Cntr=0.3,0.1

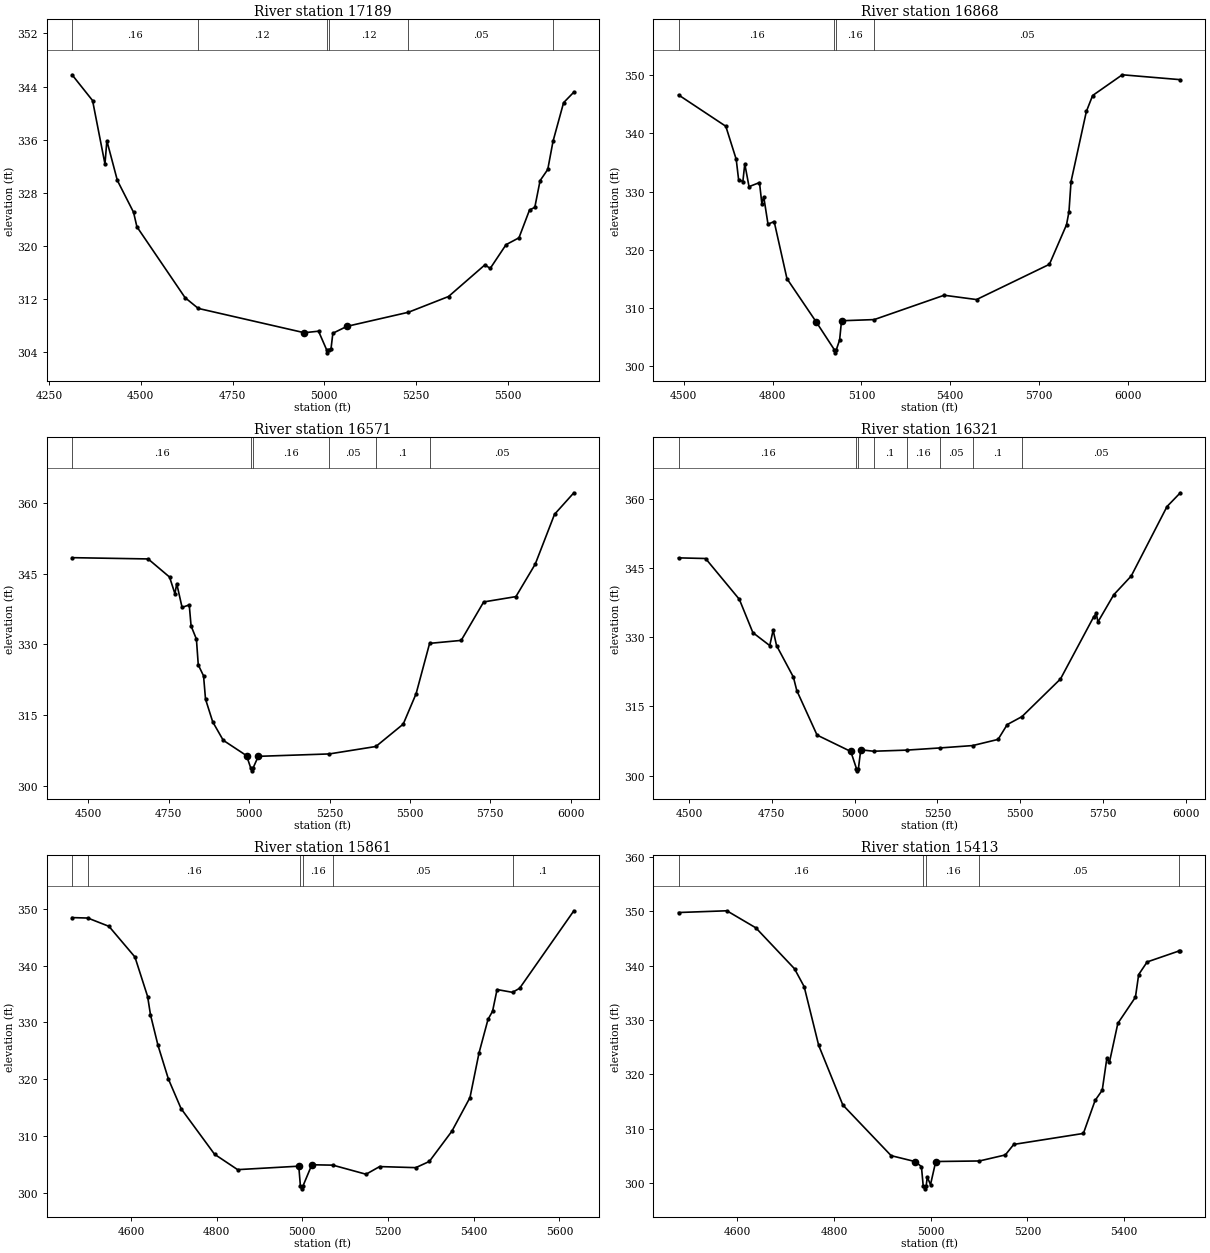
Type RM Length L Ch R = 1 ,17189   ,321,321,321
BEGIN DESCRIPTION:
JELLY SLOUGH 31.0
END DESCRIPTION:
XS GIS Cut Line= 3
       3660999.6     10587860.22      3660799.61     10588560.19
       3660399.6      10589060.2
#Sta/Elev= 30
  4312.4  345.78  4368.3   341.9  4402.1  332.35  4407.3  335.84  4435.9  329.87
  4480.1  325.07  4489.2  322.89  4620.5  312.22  4656.5   310.6  4945.5  306.94
  4984.5  307.17  5006.2  304.41  5008.9  303.91  5012.2  304.41  5018.3  304.42
  5023.5  306.86    5062   307.9  5229.5  310.02  5338.9  312.39  5438.2  317.16
  5452.6  316.62  5495.8   320.2    5531  321.23  5559.8  325.42  5574.2  325.82
  5588.6  329.84  5609.5  331.52  5623.9  335.77  5652.7  341.58  5680.7  343.17
#Mann= 6 ,-1 , 0
  4312.4     .16       0  4656.5     .12       0  5006.2     .07       0
  5012.2     .12       0  5229.5     .05       0  5623.9      .1       0
Bank Sta=4945.5,5062
XS Rating Curve= 0 ,0
Exp/Cntr=0.3,0.1

Type RM Length L Ch R = 1 ,16868   ,297,297,297
BEGIN DESCRIPTION:
Mapping XS ffbf7ae9
END DESCRIPTION:
XS GIS Cut Line= 3
      3661012.56     10587828.51      3660616.74     10588328.49
      3659720.89       10588891.
#Sta/Elev= 30
  4482.1  346.62  4641.8  341.24    4677  335.56  4685.1  332.06  4699.5  331.75
  4705.9  334.78  4720.3  330.87  4755.6  331.57  4763.6  327.96    4770  329.12
  4784.4  324.42  4805.2  324.88  4848.5  315.06  4947.9  307.59    5009  302.83
  5011.7  302.33    5015  302.83  5026.4  304.54  5032.8  307.84  5143.3  308.04
  5379.5  312.22    5489  311.48  5735.2  317.53    5793  324.32  5801.3  326.55
  5808.3  331.73  5860.1  343.78  5881.3  346.52  5981.5  350.08  6177.6  349.24
#Mann= 4 ,-1 , 0
  4482.1     .16       0    5009     .07       0    5015     .16       0
  5143.3     .05       0
Bank Sta=4947.9,5032.8
XS Rating Curve= 0 ,0
Exp/Cntr=0.3,0.1

Type RM Length L Ch R = 1 ,16571   ,250,250,250
BEGIN DESCRIPTION:
JELLY SLOUGH 30.0
END DESCRIPTION:
XS GIS Cut Line= 3
      3660999.58      10587760.2      3660512.89     10588007.41
      3659499.64     10588060.19
#Sta/Elev= 30
  4449.4  348.42  4685.9  348.15  4752.6   344.3  4769.3  340.75  4774.9   342.9
  4791.5  337.86  4813.8  338.39  4819.5  333.93  4836.1  331.12  4841.9  325.64
  4858.3  323.32  4864.4  318.38  4886.8  313.55  4919.5  309.64  4991.9  306.38
  5005.6  303.65  5008.3  303.15  5011.6  303.65  5028.6  306.23  5249.2  306.74
  5394.2  308.32  5479.2  313.07  5519.3  319.53  5561.3  330.22  5659.5  330.85
  5729.5  339.02  5829.7  340.15  5889.8  347.05  5949.8  357.63  6009.9   362.2
#Mann= 6 ,-1 , 0
  4449.4     .16       0  5005.6     .07       0  5011.6     .16       0
  5249.2     .05       0  5394.2      .1       0  5561.3     .05       0
Bank Sta=4991.9,5028.6
XS Rating Curve= 0 ,0
Exp/Cntr=0.3,0.1

Type RM Length L Ch R = 1 ,16321   ,460,460,460
BEGIN DESCRIPTION:
JELLY SLOUGH 29.0
END DESCRIPTION:
XS GIS Cut Line= 3
      3660999.66     10587660.18      3660499.61     10587760.19
      3659499.65     10587860.18
#Sta/Elev= 30
  4468.7  347.29  4550.3  347.15  4652.3  338.28  4693.1  331.05  4744.1  328.23
  4754.3  331.59  4764.5  328.25  4815.5  321.38  4825.7  318.46  4886.9  308.79
  4988.7  305.23  5005.8  301.52  5008.6  301.02  5011.8  301.52  5018.8  305.59
  5057.4  305.28  5157.1  305.52  5256.9  305.99  5356.7  306.51  5433.4  307.85
    5461  311.07  5505.5   312.8  5621.8  320.98  5722.3  334.51  5729.9  335.23
  5734.9  333.37  5782.6  339.27  5835.4  343.35  5943.4  358.44  5983.6  361.43
#Mann= 8 ,-1 , 0
  4468.7     .16       0  5005.8     .07       0  5011.8     .16       0
  5057.4      .1       0  5157.1     .16       0  5256.9     .05       0
  5356.7      .1       0  5505.5     .05       0
Bank Sta=4988.7,5018.8
XS Rating Curve= 0 ,0
Exp/Cntr=0.3,0.1

Type RM Length L Ch R = 1 ,15861   ,448,448,448
BEGIN DESCRIPTION:
JELLY SLOUGH 28.0
END DESCRIPTION:
XS GIS Cut Line= 3
      3660899.56     10587110.21      3660399.61     10587310.19
      3659799.63      10587110.2
#Sta/Elev= 30
  4462.7  348.46  4499.5  348.38  4548.8  346.92  4609.4  341.52    4639  334.56
  4645.7  331.34  4663.2  325.96  4687.5  320.03  4717.1  314.82  4795.2  306.79
    4849  304.08  4991.7  304.69  4995.5   301.2  4998.2   300.7  5001.5   301.2
  5022.2  304.94  5071.3  304.87  5148.7  303.27  5180.4  304.62  5264.7  304.43
  5296.3  305.52    5349  310.85  5391.2  316.77  5412.3  324.63  5433.3  330.54
  5443.9  331.97  5454.4  335.79  5490.5   335.3  5507.1  336.02  5633.6  349.66
#Mann= 6 ,-1 , 0
  4462.7     .05       0  4499.5     .16       0  4995.5     .07       0
  5001.5     .16       0  5071.3     .05       0  5490.5      .1       0
Bank Sta=4991.7,5022.2
XS Rating Curve= 0 ,0
Exp/Cntr=0.3,0.1

Type RM Length L Ch R = 1 ,15413   ,407,407,407
BEGIN DESCRIPTION:
JELLY SLOUGH 27.0
END DESCRIPTION:
XS GIS Cut Line= 3
      3660949.58     10586860.19      3660449.61     10586860.19
       3659949.6     10587060.19
#Sta/Elev= 30
  4478.1  349.81  4578.1  350.13  4638.1  346.99  4718.1  339.46  4738.1  336.16
  4768.1  325.37  4818.1  314.38  4918.1  305.05  4968.1  303.95  4980.8  303.03
  4984.5  299.44  4987.2  298.94  4990.5  299.44  4992.9  301.09  4999.6  299.72
  5010.4  303.97  5100.7  304.07  5154.4  305.18  5171.9  307.12    5316  309.14
  5340.2  315.21    5355   317.1  5364.5  322.96  5369.8   322.2  5387.3  329.41
  5423.7  334.22  5430.4  338.39  5447.9  340.71  5514.8  342.76  5516.6  342.76
#Mann= 5 ,-1 , 0
  4478.1     .16       0  4984.5     .07       0  4990.5     .16       0
  5100.7     .05       0  5514.8      .1       0
Bank Sta=4968.1,5010.4
XS Rating Curve= 0 ,0
Exp/Cntr=0.3,0.1