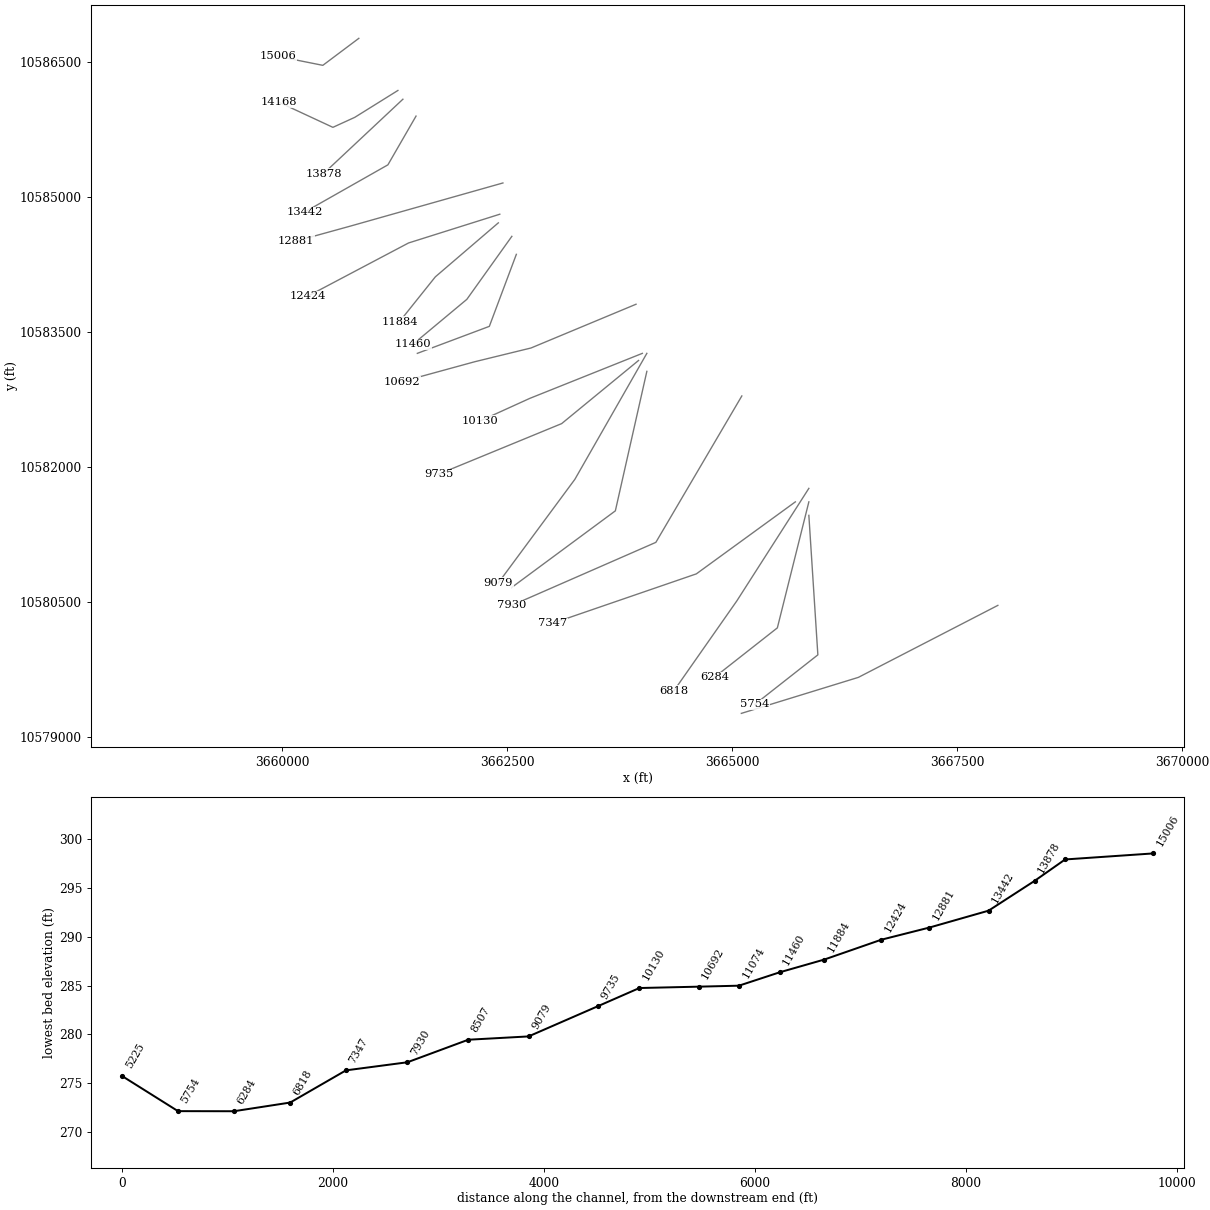
HEC-RAS study JELLY SLOUGH.prj: JELLY SLOUGH Base Level Engineering

--- JELLY SLOUGH.g01 (geometry) --- (continued)

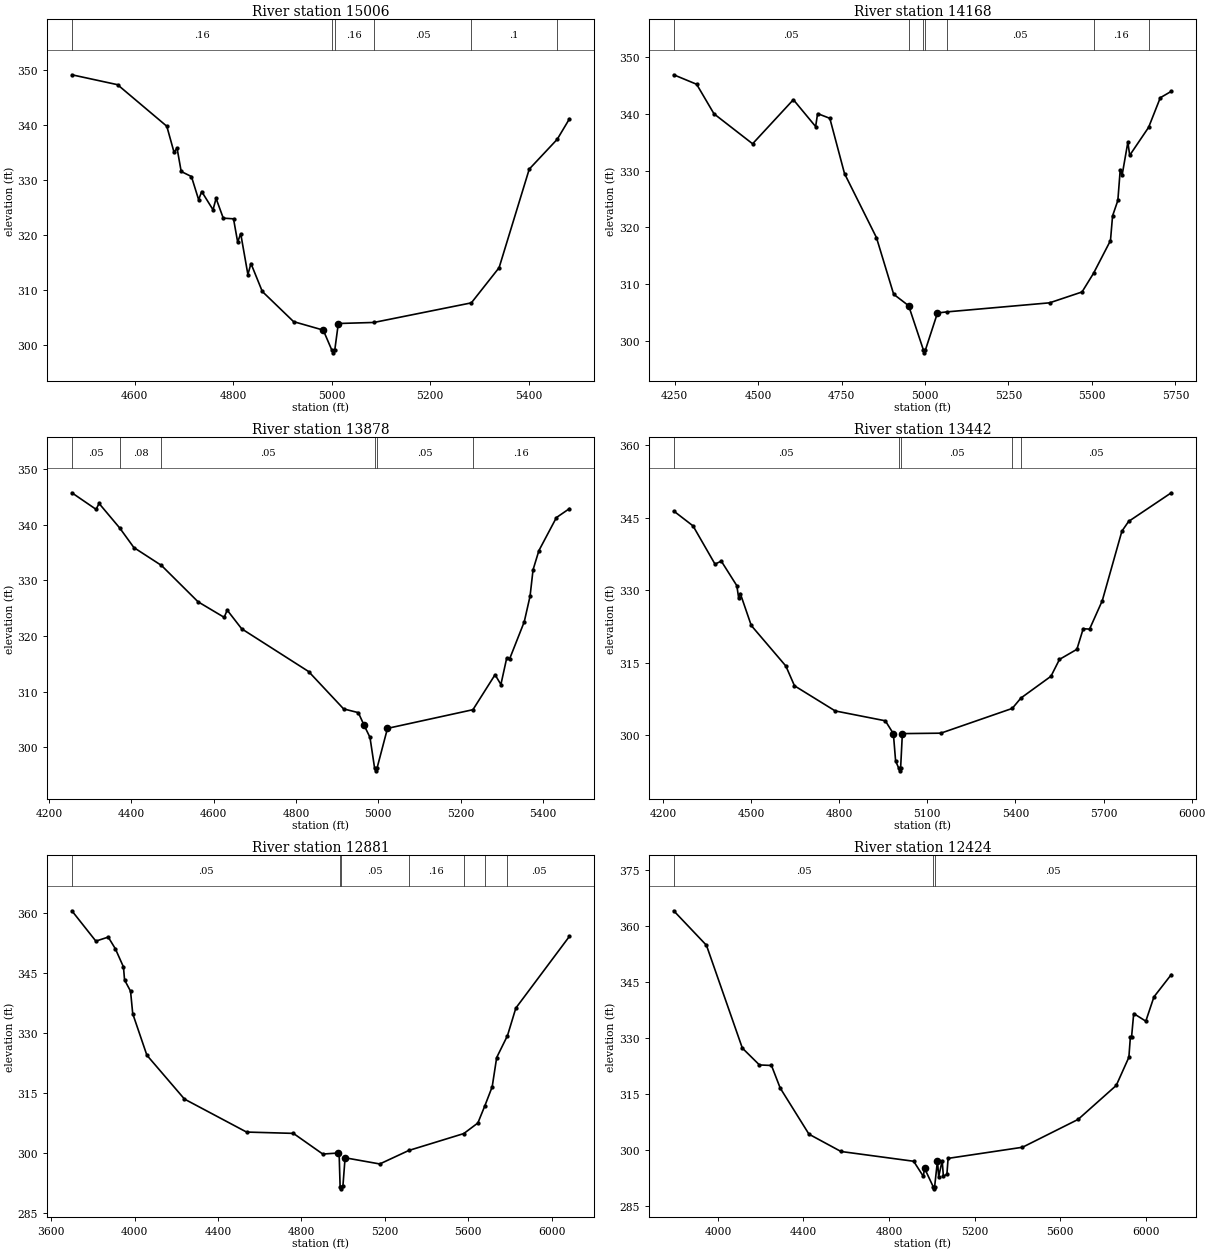
Type RM Length L Ch R = 1 ,15006   ,838,838,838
BEGIN DESCRIPTION:
JELLY SLOUGH 26.0
END DESCRIPTION:
XS GIS Cut Line= 3
      3660849.61     10586760.19      3660449.61     10586460.19
      3659949.61     10586560.19
#Sta/Elev= 30
  4472.6  349.07  4565.3  347.27  4665.3  339.72  4679.9  335.01  4686.1  335.74
  4694.5   331.5  4715.3  330.58  4729.9  326.37  4736.1  327.86  4759.1  324.54
  4765.3  326.61  4779.9  323.02  4800.7   322.9  4809.1  318.68  4815.3   320.2
  4829.9  312.77  4836.1  314.78  4859.1   309.7  4922.6  304.22  4982.8  302.68
  5000.2  299.05  5002.9  298.55  5006.2  299.05  5013.4  303.88  5085.6  304.07
  5283.4  307.63  5339.7  314.02  5400.9  331.93  5457.7  337.35  5482.5  341.07
#Mann= 6 ,-1 , 0
  4472.6     .16       0  5000.2     .07       0  5006.2     .16       0
  5085.6     .05       0  5283.4      .1       0  5457.7     .05       0
Bank Sta=4982.8,5013.4
XS Rating Curve= 0 ,0
Exp/Cntr=0.3,0.1

Type RM Length L Ch R = 1 ,14168   ,290,290,290
BEGIN DESCRIPTION:
JELLY SLOUGH 25.0
END DESCRIPTION:
XS GIS Cut Line= 4
      3661283.76     10586181.04      3660804.56     10585882.41
      3660561.51      10585771.3      3659964.41     10586049.02
#Sta/Elev= 30
  4247.4  346.85  4316.1  345.18  4368.1  339.98  4483.7  334.71  4605.8  342.47
  4672.5  337.74  4678.4  340.02    4715  339.19    4759  329.47  4854.7   318.2
  4906.2  308.24  4951.1  306.22  4995.3  298.43  4998.1  297.93  5001.3  298.43
  5037.4  304.94  5064.7  305.13  5373.3  306.73  5470.4  308.64    5505  311.94
  5555.6  317.68  5561.9  322.03  5577.7  324.74  5584.8  330.13  5590.3  329.13
  5607.7     335  5613.2  332.68  5669.8   337.6  5704.8  342.81  5737.8  343.94
#Mann= 7 ,-1 , 0
  4247.4     .05       0  4951.1     .16       0  4995.3     .07       0
  5001.3     .16       0  5064.7     .05       0    5505     .16       0
  5669.8      .1       0
Bank Sta=4951.1,5037.4
XS Rating Curve= 0 ,0
Exp/Cntr=0.3,0.1

Type RM Length L Ch R = 1 ,13878   ,436,436,436
BEGIN DESCRIPTION:
JELLY SLOUGH 24.0
END DESCRIPTION:
XS GIS Cut Line= 2
      3661339.26     10586083.78      3660457.33      10585257.4
#Sta/Elev= 30
  4255.7  345.75  4314.5  342.77  4321.8  343.83  4372.2  339.39  4406.4  335.89
  4473.3  332.68  4562.2  326.14  4625.7  323.34    4633  324.64  4668.2  321.28
  4830.8  313.59  4915.8  306.87  4951.5   306.2  4965.6  303.91  4979.8  301.75
    4991  296.23  4993.7  295.73    4997  296.23  5022.3  303.37  5229.9  306.73
  5283.6  313.02  5297.8  311.26    5312  316.05  5319.3  315.93  5354.5  322.54
  5368.6  327.14  5375.9   331.9  5390.1  335.35  5432.6  341.29  5464.3   342.9
#Mann= 6 ,-1 , 0
  4255.7     .05       0  4372.2     .08       0  4473.3     .05       0
    4991     .03       0    4997     .05       0  5229.9     .16       0
Bank Sta=4965.6,5022.3
XS Rating Curve= 0 ,0
Exp/Cntr=0.3,0.1

Type RM Length L Ch R = 1 ,13442   ,561,561,561
BEGIN DESCRIPTION:
JELLY SLOUGH 23.0
END DESCRIPTION:
XS GIS Cut Line= 3
      3661485.11      10585896.3      3661172.62     10585354.63
      3660243.32     10584827.57
#Sta/Elev= 30
    4237  346.42  4302.8  343.34  4377.5  335.44    4399  336.05  4451.9  330.97
  4457.9   328.5  4463.7  329.35    4501  322.74  4618.7  314.36  4648.1  310.27
  4786.7  305.07  4957.3  303.03  4984.7  300.37  4992.3  294.72  5003.3  293.18
  5006.1  292.68  5009.3  293.18  5015.3  300.38  5146.2  300.47  5389.3  305.59
  5418.9  307.74  5521.1  312.24  5550.1  315.73  5609.3  317.81  5630.9  322.08
  5652.5  321.99  5695.8  327.88  5762.5  342.25  5785.5  344.27  5930.7  350.19
#Mann= 5 ,-1 , 0
    4237     .05       0  5003.3     .03       0  5009.3     .05       0
  5389.3     .16       0  5418.9     .05       0
Bank Sta=4984.7,5015.3
XS Rating Curve= 0 ,0
Exp/Cntr=0.3,0.1

Type RM Length L Ch R = 1 ,12881   ,457,457,457
BEGIN DESCRIPTION:
JELLY SLOUGH 22.0
END DESCRIPTION:
XS GIS Cut Line= 3
      3662450.38     10585153.24      3660755.95     10584674.08
      3660153.24     10584507.81
#Sta/Elev= 30
  3699.1  360.59  3814.2  352.99  3873.5     354  3907.5  351.09  3946.6  346.52
  3951.8  343.26  3980.5  340.46    3991  334.81  4058.9  324.41  4239.1  313.43
  4536.8  305.17  4761.4  304.84  4902.4  299.66  4975.5  299.92  4980.7  299.85
  4985.5  291.45  4988.3  290.95  4991.5  291.45  4998.9  291.63  5009.3  298.73
  5175.6  297.18  5314.8  300.56  5578.4  304.79    5646  307.44    5680  311.81
  5714.7  316.51  5736.3  323.84    5788  329.32  5828.1  336.22  6085.2  354.19
#Mann= 7 ,-1 , 0
  3699.1     .05       0  4985.5     .03       0  4991.5     .05       0
  5314.8     .16       0  5578.4     .05       0    5680     .16       0
    5788     .05       0
Bank Sta=4975.5,5009.3
XS Rating Curve= 0 ,0
Exp/Cntr=0.3,0.1

Type RM Length L Ch R = 1 ,12424   ,540,540,540
BEGIN DESCRIPTION:
JELLY SLOUGH 21.0
END DESCRIPTION:
XS GIS Cut Line= 3
      3662415.65     10584806.01      3661401.78     10584486.58
      3660284.18     10583896.54
#Sta/Elev= 30
  3793.3     364  3946.4  354.78  4114.2  327.31  4194.1  322.81  4250.5  322.66
  4291.2  316.64  4425.9   304.3  4575.5  299.68  4915.3  297.07  4960.5  293.04
  4966.3  295.18  5007.3   290.2  5010.1   289.7  5013.3   290.2  5026.7  297.26
  5032.3  292.93  5048.7  297.23  5054.3  293.12  5070.7  293.54  5076.4  297.84
  5424.2  300.81  5684.3  308.25  5862.7  317.33  5921.7  324.86  5928.8  330.32
  5934.4  330.33  5944.3  336.54  6000.9   334.5  6038.9  340.99  6120.1  346.96
#Mann= 3 ,-1 , 0
  3793.3     .05       0  5007.3     .03       0  5013.3     .05       0
Bank Sta=4966.3,5026.7
XS Rating Curve= 0 ,0
Exp/Cntr=0.3,0.1

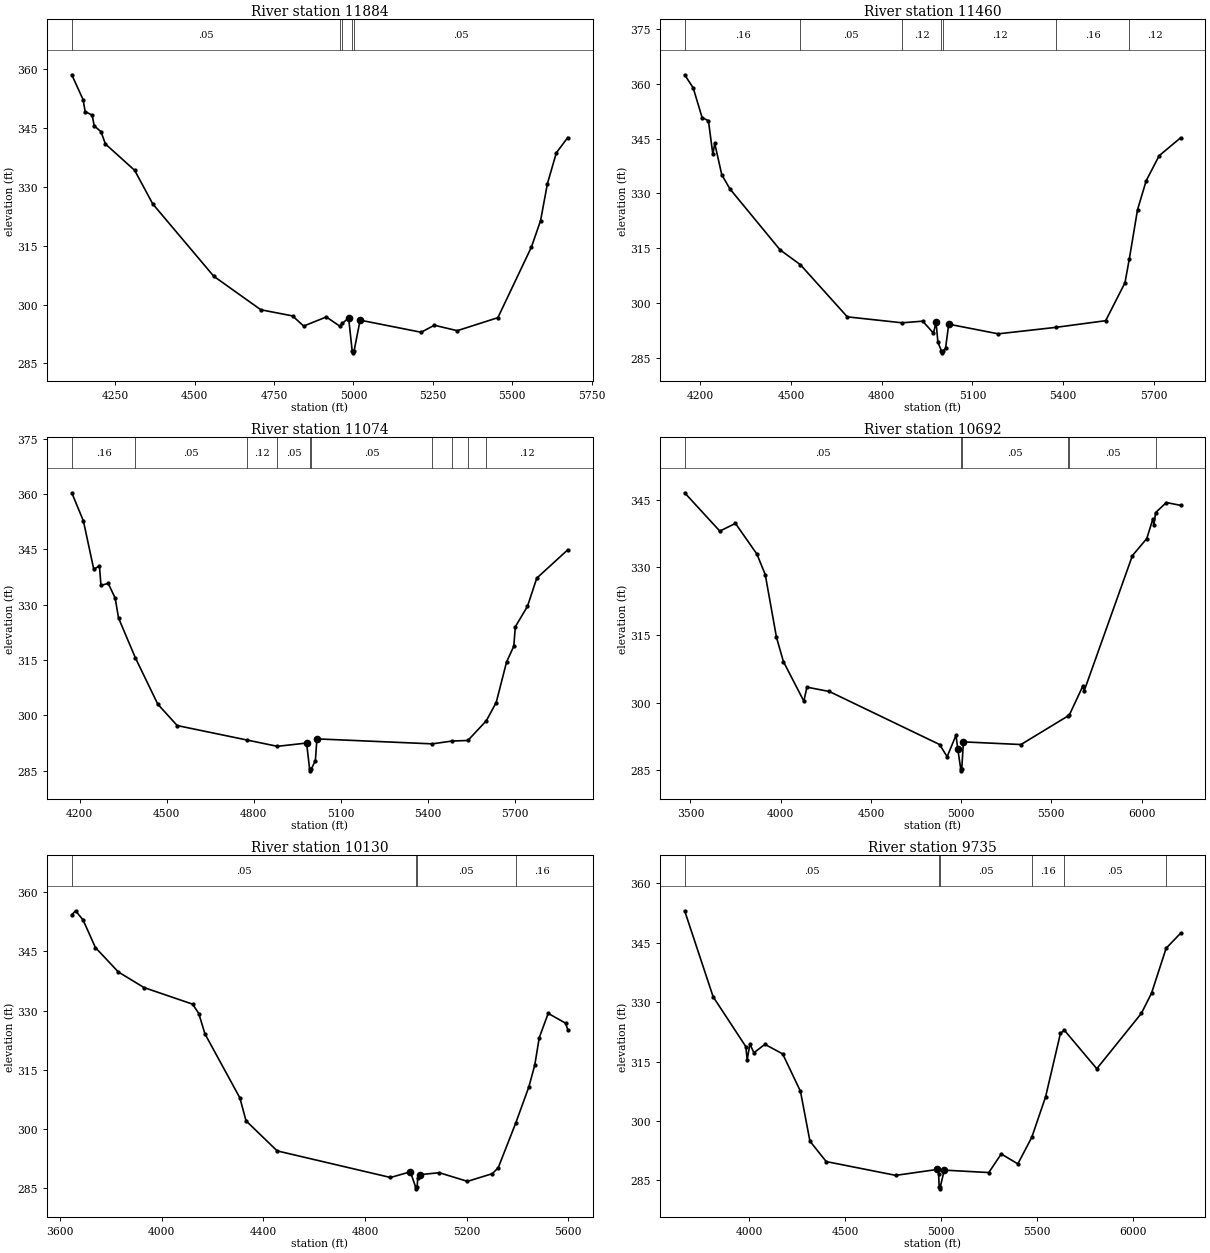
Type RM Length L Ch R = 1 ,11884   ,424,424,424
BEGIN DESCRIPTION:
JELLY SLOUGH 20.0
END DESCRIPTION:
XS GIS Cut Line= 3
      3662399.58     10584710.16      3661699.61     10584110.19
      3661299.62     10583610.21
#Sta/Elev= 30
  4112.7   358.6  4148.3  352.27  4154.9  349.21  4176.9   348.3  4183.4  345.58
  4204.9  344.06  4218.6  340.95  4310.8  334.22  4367.8  325.65  4559.9  307.21
  4708.1  298.66    4808  297.09  4843.1   294.5  4914.4  296.82  4957.3  294.46
    4965  295.19  4984.7  296.58  4995.9  288.17  4998.7  287.67  5001.9  288.17
  5020.9  296.01  5213.1  292.92  5254.7  294.71  5326.8  293.32  5454.8  296.64
  5560.5  314.66  5589.3  321.41  5610.9  330.84  5638.9  338.68  5674.9   342.6
#Mann= 5 ,-1 , 0
  4112.7     .05       0  4957.3     .12       0    4965     .05       0
  4995.9     .03       0  5001.9     .05       0
Bank Sta=4984.7,5020.9
XS Rating Curve= 0 ,0
Exp/Cntr=0.3,0.1

Type RM Length L Ch R = 1 ,11460   ,386,386,386
BEGIN DESCRIPTION:
JELLY SLOUGH 19.0
END DESCRIPTION:
XS GIS Cut Line= 3
      3662549.62      10584560.2      3662049.61     10583860.19
      3661449.59     10583360.17
#Sta/Elev= 30
  4147.6  362.47  4175.9  358.88  4205.4  350.76  4226.3  349.89    4241  340.69
  4247.2  343.68  4270.5   335.1  4297.5  331.23  4463.4  314.55  4530.7  310.48
  4685.9  296.21  4867.4  294.58  4935.3  295.03    4971  291.76  4979.6   294.7
  4985.7  289.29  4997.5  286.86  5000.2  286.36  5003.5  286.86  5011.1  287.65
  5021.5  294.21  5185.5  291.56  5375.7  293.33  5540.9  295.16  5604.7  305.53
  5619.2  312.09  5646.3  325.54    5675  333.48  5717.9  340.32  5788.9  345.22
#Mann= 7 ,-1 , 0
  4147.6     .16       0  4530.7     .05       0  4867.4     .12       0
  4997.5     .07       0  5003.5     .12       0  5375.7     .16       0
  5619.2     .12       0
Bank Sta=4979.6,5021.5
XS Rating Curve= 0 ,0
Exp/Cntr=0.3,0.1

Type RM Length L Ch R = 1 ,11074   ,382,382,382
BEGIN DESCRIPTION:
JELLY SLOUGH 18.0
END DESCRIPTION:
XS GIS Cut Line= 3
      3662599.62     10584360.21      3662299.61     10583560.19
      3661499.63      10583260.2
#Sta/Elev= 30
  4173.2  360.32  4213.3  352.68  4248.9  339.61  4268.5  340.49  4273.8  335.21
  4298.7  335.79  4322.7  331.78  4334.3   326.4  4391.8  315.69  4469.6  303.04
  4536.3  297.26    4778  293.32  4881.6  291.63  4982.2  292.52  4992.6  285.49
  4995.3  284.99  4998.6  285.49  5012.5  287.78  5017.8  293.65  5415.3   292.3
  5482.8  293.06    5538  293.22  5601.5  298.57  5635.5   303.5  5671.1  314.45
    5696  318.74  5701.4  324.02  5743.2  329.56  5775.2  337.19    5882  344.87
#Mann= 10 ,-1 , 0
  4173.2     .16       0  4391.8     .05       0    4778     .12       0
  4881.6     .05       0  4992.6     .03       0  4998.6     .05       0
  5415.3     .12       0  5482.8     .16       0    5538     .05       0
  5601.5     .12       0
Bank Sta=4982.2,5017.8
XS Rating Curve= 0 ,0
Exp/Cntr=0.3,0.1

Type RM Length L Ch R = 1 ,10692   ,562,562,562
BEGIN DESCRIPTION:
JELLY SLOUGH 17.0
END DESCRIPTION:
XS GIS Cut Line= 4
      3663929.54     10583806.01      3662762.89     10583319.91
      3662137.89     10583167.13      3661325.89     10582945.04
#Sta/Elev= 30
  3467.7  346.52  3662.6  338.03  3749.3  339.73  3868.5  332.92  3914.5  328.38
  3976.8  314.46  4015.3  309.09  4128.5  300.33  4145.3  303.44  4269.3  302.48
    4881  290.72  4922.6  288.02  4971.7  292.77    4982  289.62  4997.8  285.39
  5000.5  284.89  5003.8  285.39  5012.9  291.31    5332  290.72  5595.3  297.12
  5599.9  297.26  5673.8  303.59  5682.3  302.62  5949.7   332.6  6029.1  336.37
  6063.6  340.78  6068.8  339.46  6078.2  342.13  6137.8  344.36  6216.8  343.73
#Mann= 6 ,-1 , 0
  3467.7     .05       0  4997.8     .03       0  5003.8     .05       0
  5595.3     .08       0  5599.9     .05       0  6078.2     .12       0
Bank Sta=4982,5012.9
XS Rating Curve= 0 ,0
Exp/Cntr=0.3,0.1

Type RM Length L Ch R = 1 ,10130   ,395,395,395
BEGIN DESCRIPTION:
JELLY SLOUGH 16.0
END DESCRIPTION:
XS GIS Cut Line= 3
      3663999.65      10583260.2      3662749.61     10582760.19
       3662199.6     10582510.18
#Sta/Elev= 30
  3647.1  354.31    3662  355.32  3691.6  352.98    3740     346  3830.2  339.79
  3931.2  335.83  4122.4  331.62  4146.6  329.24  4170.9  324.06  4308.2  307.83
  4332.4  302.01  4454.9  294.38  4900.5  287.63  4978.6  289.07  4999.2  285.25
    5002  284.75  5005.2  285.25  5007.7  287.54  5015.4  288.35  5092.3  288.84
  5203.2  286.65    5301   288.6  5324.1   290.1  5392.6  301.37  5444.9  310.68
    5468  316.19  5485.5  323.12  5520.7  329.28  5588.8   326.8  5597.6  325.18
#Mann= 4 ,-1 , 0
  3647.1     .05       0  4999.2     .03       0  5005.2     .05       0
  5392.6     .16       0
Bank Sta=4978.6,5015.4
XS Rating Curve= 0 ,0
Exp/Cntr=0.3,0.1

Type RM Length L Ch R = 1 ,9735    ,656,656,656
BEGIN DESCRIPTION:
JELLY SLOUGH 15.0
END DESCRIPTION:
XS GIS Cut Line= 3
      3663957.36     10583181.04      3663103.17     10582479.63
      3661735.16     10581917.15
#Sta/Elev= 30
    3665  353.03  3813.5  331.34  3984.2  318.73  3990.7  315.38  4005.1  319.38
  4025.9  317.21  4083.3  319.34  4175.8  316.92  4268.4   307.5  4317.9  294.91
  4402.6  289.76    4765  286.28  4979.5  287.76  4988.6  286.73    4991  283.38
  4993.8  282.88    4997  283.38    5018   287.6  5249.9  286.99  5314.7  291.68
  5401.2  289.18  5473.8  295.88  5545.9  306.11  5623.2  322.11  5643.4  322.91
  5812.5  313.18  6044.4  327.12  6097.7  332.22    6174  343.58  6249.4  347.37
#Mann= 6 ,-1 , 0
    3665     .05       0    4991     .03       0    4997     .05       0
  5473.8     .16       0  5643.4     .05       0    6174     .16       0
Bank Sta=4979.5,5018
XS Rating Curve= 0 ,0
Exp/Cntr=0.3,0.1

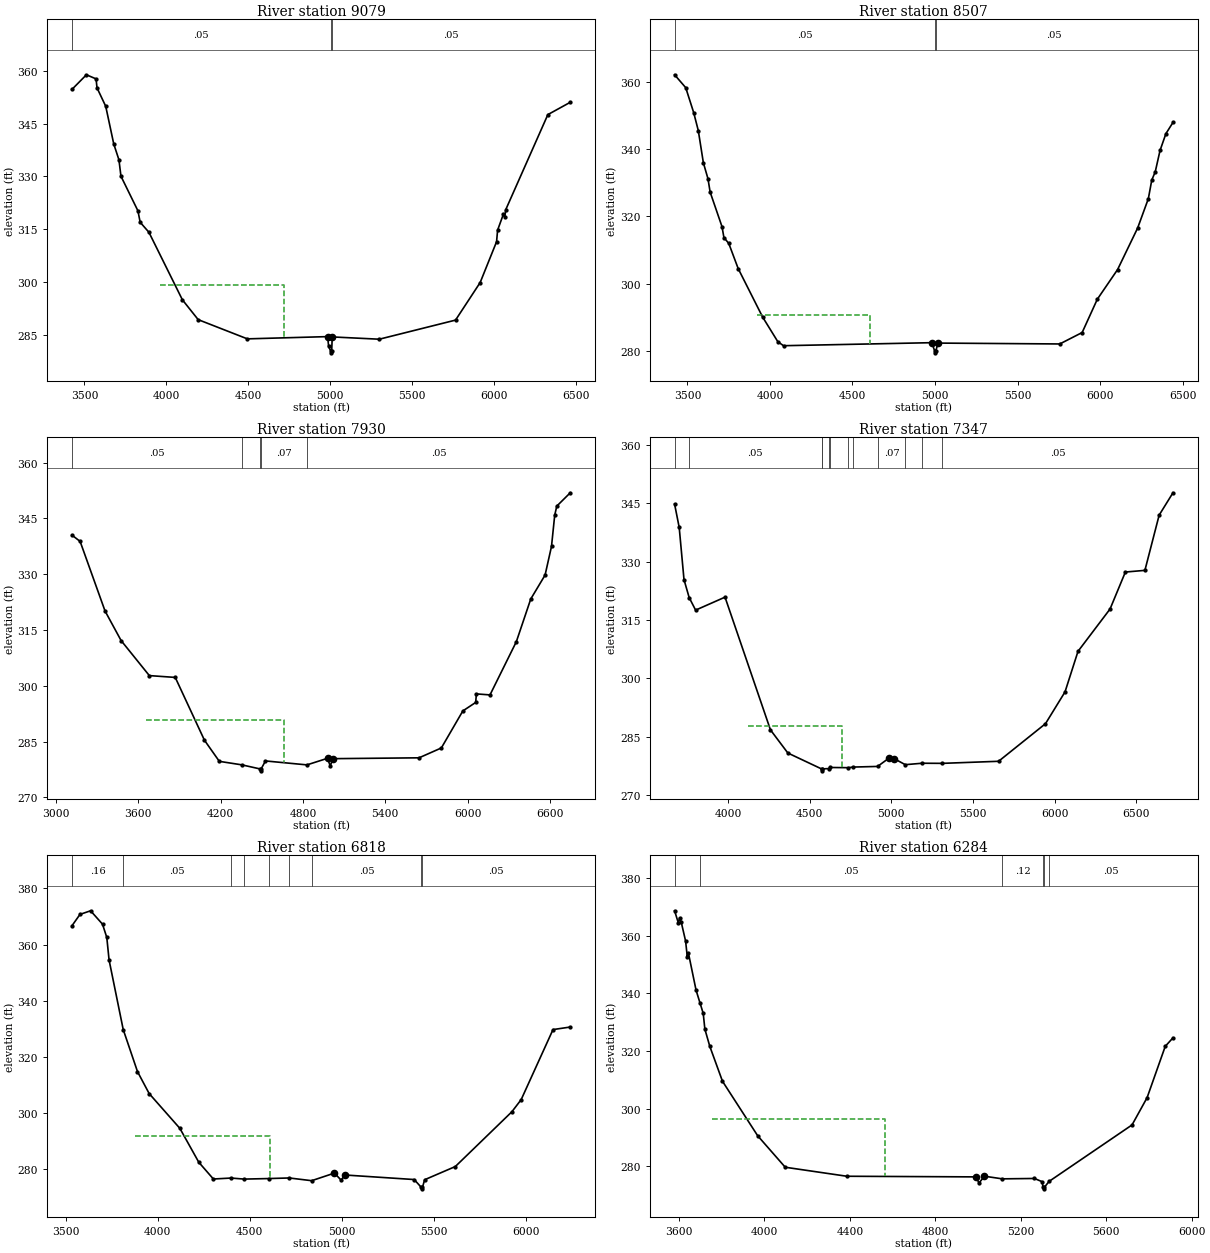
Type RM Length L Ch R = 1 ,9079    ,572,572,572
BEGIN DESCRIPTION:
JELLY SLOUGH 14.0
END DESCRIPTION:
XS GIS Cut Line= 3
      3664049.61      10583260.2      3663249.61     10581860.19
      3662399.61     10580710.19
#Sta/Elev= 30
  3423.5  354.77  3512.1  358.95  3571.1  357.78  3576.8  355.23  3630.1  349.97
  3679.1  339.24  3710.7  334.74    3723  330.07  3826.6  320.22  3840.3  316.96
  3893.6  314.12    4098  294.89  4194.5  289.24  4494.6  283.77  4984.9  284.41
  4990.6  281.65  5003.4  280.29  5006.2  279.79  5009.4  280.29  5012.9  284.32
    5300  283.67  5765.6  289.11  5915.9   299.8  6016.1  311.42  6022.4  314.72
  6057.8  319.27  6066.2  318.52  6072.5  320.59  6329.2  347.61    6466  351.12
#Mann= 3 ,-1 , 0
  3423.5     .05       0  5003.4     .03       0  5009.4     .05       0
#XS Ineff= 1 ,-1
 3960.51 4718.18  299.16
Permanent Ineff=
       F
Bank Sta=4984.9,5012.9
XS Rating Curve= 0 ,0
Exp/Cntr=0.3,0.1

Type RM Length L Ch R = 1 ,8507    ,577,577,577
BEGIN DESCRIPTION:
JELLY SLOUGH 13.0
END DESCRIPTION:
XS GIS Cut Line= 3
      3664049.62     10583060.23      3663699.61     10581510.19
      3662549.61     10580660.19
#Sta/Elev= 30
  3422.3  362.12  3489.7  358.29    3538  350.86  3565.9  345.52  3596.6  335.95
  3624.5  331.21  3637.6  327.24  3709.4  316.98  3721.1  313.72  3750.4  311.99
  3807.5   304.5  3955.4   290.1  4047.7  282.76  4082.1  281.57  4980.6  282.47
  4998.1  279.95  5000.9  279.45  5004.1  279.95  5018.7  282.35  5755.6  282.09
  5891.3  285.49  5983.1  295.39  6105.7  304.19  6227.4  316.56  6292.2  325.28
    6313  330.82  6333.9  333.25  6363.1  339.62  6398.6  344.61  6441.4  347.95
#Mann= 3 ,-1 , 0
  3422.3     .05       0  4998.1     .03       0  5004.1     .05       0
#XS Ineff= 1 ,-1
 3922.73 4608.81  290.57
Permanent Ineff=
       F
Bank Sta=4980.6,5018.7
XS Rating Curve= 0 ,0
Exp/Cntr=0.3,0.1

Type RM Length L Ch R = 1 ,7930    ,583,583,583
BEGIN DESCRIPTION:
JELLY SLOUGH 12.0
END DESCRIPTION:
XS GIS Cut Line= 3
      3665104.92     10582786.94      3664149.61     10581160.19
      3662549.65      10580460.2
#Sta/Elev= 30
  3115.9  340.51  3175.8  338.81  3357.5   320.1  3474.7  312.15  3680.4  302.74
  3869.3  302.25  4082.3  285.36  4190.6  279.69  4354.6  278.75  4489.2  277.64
  4491.9  277.14  4495.2  277.64  4526.9   279.8  4829.2  278.74  4979.2  280.51
  4999.5  278.39  5016.8  280.41  5646.4  280.64    5809  283.29  5965.7  293.24
  6059.2  295.52  6064.7  297.82  6163.7  297.55  6355.9  311.87  6460.8  323.33
  6565.2  329.76    6612  337.47  6635.4  345.85  6650.6   348.3  6748.8  351.88
#Mann= 5 ,-1 , 0
  3115.9     .05       0  4354.6     .07       0  4489.2     .03       0
  4495.2     .07       0  4829.2     .05       0
#XS Ineff= 1 ,-1
 3659.09 4661.36  290.76
Permanent Ineff=
       F
Bank Sta=4979.2,5016.8
XS Rating Curve= 0 ,0
Exp/Cntr=0.3,0.1

Type RM Length L Ch R = 1 ,7347    ,529,529,529
BEGIN DESCRIPTION:
JELLY SLOUGH 11.0
END DESCRIPTION:
XS GIS Cut Line= 3
      3665699.63     10581610.21      3664599.61     10580810.19
      3662999.58     10580260.18
#Sta/Elev= 30
  3672.5  344.72  3700.7  338.74  3730.1  325.35  3761.7  320.75  3801.2  317.53
  3981.3  320.86  4259.5  286.82  4366.1  280.88  4572.2  276.81  4574.9  276.31
  4578.2  276.81  4617.6  276.89  4625.4  277.17  4736.6  277.12  4768.1  277.28
  4915.7  277.44  4983.2  279.51  5019.2  279.38  5085.3  277.89  5188.5  278.26
    5313  278.23  5656.6  278.76  5943.8   288.4  6063.4  296.55    6143  306.96
  6339.3  317.82  6433.1   327.3  6552.7  327.73    6640   341.9  6724.6  347.63
#Mann= 12 ,-1 , 0
  3672.5     .16       0  3761.7     .05       0  4572.2     .07       0
  4578.2     .05       0  4617.6     .07       0  4625.4     .12       0
  4736.6     .07       0  4768.1     .12       0  4915.7     .07       0
  5085.3     .05       0  5188.5     .07       0    5313     .05       0
#XS Ineff= 1 ,-1
 4120.45 4695.17  287.74
Permanent Ineff=
       F
Bank Sta=4983.2,5019.2
XS Rating Curve= 0 ,0
Exp/Cntr=0.3,0.1

Type RM Length L Ch R = 1 ,6818    ,534,534,534
BEGIN DESCRIPTION:
JELLY SLOUGH 10.0
END DESCRIPTION:
XS GIS Cut Line= 3
      3665849.59     10581760.17      3665049.61     10580510.19
      3664349.62      10579510.2
#Sta/Elev= 30
  3534.7  366.64  3578.6  370.72  3636.1  372.01  3700.9  367.24  3724.1   362.5
  3736.5  354.48  3813.2  329.73  3890.7  314.74  3954.1  306.92  4120.7  294.54
  4223.3  282.48  4302.5  276.51    4398  276.85    4470  276.48  4602.1  276.67
  4714.4  276.88  4835.8  275.91  4959.6  278.62  4995.9   276.1  5015.8  277.94
  5392.4  276.32  5431.2  273.51    5434  273.01  5437.2  273.51    5449  276.25
  5615.6  280.95  5922.5  300.45    5973  304.78  6145.7  329.71  6239.4  330.62
#Mann= 9 ,-1 , 0
  3534.7     .16       0  3813.2     .05       0    4398     .12       0
    4470     .05       0  4602.1     .12       0  4714.4     .07       0
  4835.8     .05       0  5431.2     .03       0  5437.2     .05       0
#XS Ineff= 1 ,-1
    3875 4607.95  291.79
Permanent Ineff=
       F
Bank Sta=4959.6,5015.8
XS Rating Curve= 0 ,0
Exp/Cntr=0.3,0.1

Type RM Length L Ch R = 1 ,6284    ,530,530,530
BEGIN DESCRIPTION:
JELLY SLOUGH 9.0
END DESCRIPTION:
XS GIS Cut Line= 3
      3665849.61     10581610.18      3665499.61     10580210.19
      3664799.61     10579660.19
#Sta/Elev= 30
  3579.2  368.69  3597.2  364.35  3602.4  366.19  3610.1  364.81  3630.7  358.16
  3638.5  352.78  3643.6  354.11  3679.7  341.12  3698.9  336.49  3713.2  333.06
  3720.9  327.59  3744.1  321.59  3803.4  309.48  3968.3  290.54  4097.2  279.62
  4385.8  276.49  4991.4  276.27  5004.2   274.1  5029.5  276.51  5113.5  275.59
  5263.9  275.72  5300.6  274.58    5304  272.62  5306.7  272.12    5310  272.62
  5332.6  274.71  5720.9  294.32  5791.4  303.79  5876.4  321.62  5912.5  324.56
#Mann= 6 ,-1 , 0
  3579.2     .16       0  3698.9     .05       0  5113.5     .12       0
    5304     .03       0    5310     .12       0  5332.6     .05       0
#XS Ineff= 1 ,-1
 3754.26  4562.5  296.35
Permanent Ineff=
       F
Bank Sta=4991.4,5029.5
XS Rating Curve= 0 ,0
Exp/Cntr=0.3,0.1

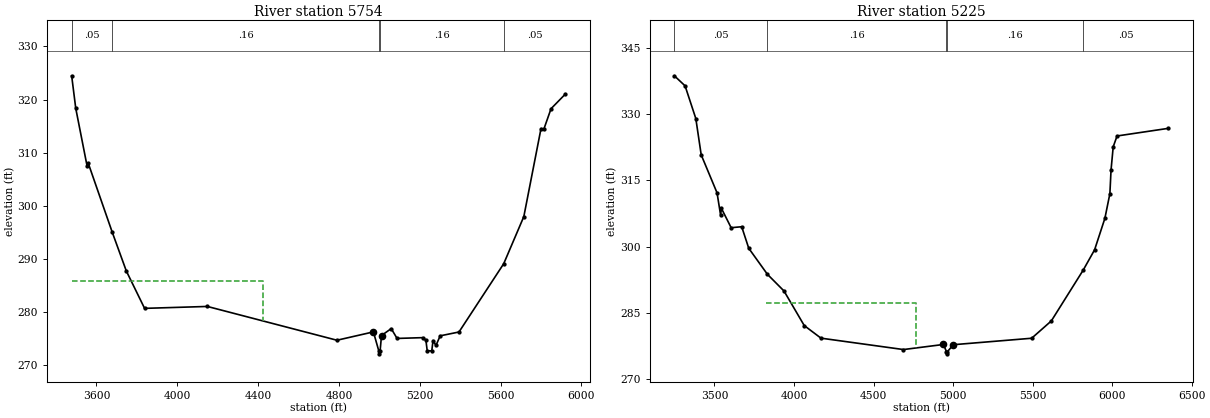
Type RM Length L Ch R = 1 ,5754    ,529,529,529
BEGIN DESCRIPTION:
JELLY SLOUGH 8.0
END DESCRIPTION:
XS GIS Cut Line= 3
      3665849.61     10581460.21      3665949.61     10579910.19
      3665249.59     10579360.17
#Sta/Elev= 30
  3477.7  324.47  3497.8  318.36  3554.1  307.46  3559.1  308.08  3678.1  295.06
  3748.3  287.71  3838.5  280.69  4149.1  281.05  4790.4  274.69  4970.8  276.26
  4997.9  272.63  5000.6  272.13  5003.9  272.63  5010.9  275.58    5059  276.88
  5087.9  275.03  5216.2  275.18  5230.7  274.67    5237  272.73  5259.6  272.67
  5265.9  274.64  5280.4  273.71  5301.2  275.52  5394.3  276.24  5615.7   289.1
  5715.1  297.96  5800.1  314.52  5814.5  314.45  5849.8  318.27  5921.2  321.05
#Mann= 5 ,-1 , 0
  3477.7     .05       0  3678.1     .16       0  4997.9     .03       0
  5003.9     .16       0  5615.7     .05       0
#XS Ineff= 1 ,-1
 3460.23  4423.3 285.889
Permanent Ineff=
       F
Bank Sta=4970.8,5010.9
XS Rating Curve= 0 ,0
Exp/Cntr=0.3,0.1

Type RM Length L Ch R = 1 ,5225    ,558,558,558
BEGIN DESCRIPTION:
JELLY SLOUGH 7.0
END DESCRIPTION:
XS GIS Cut Line= 3
      3667949.57     10580460.17      3666399.61     10579660.19
      3665099.58     10579260.18
#Sta/Elev= 30
  3247.7  338.68  3315.2   336.4  3382.7     329  3416.6  320.77  3516.2  312.17
  3538.3  307.17  3543.9  308.64  3604.8  304.28  3671.2   304.5  3715.5  299.62
  3832.8  293.73  3937.1  289.95  4064.4  282.12  4169.6  279.27  4688.1  276.69
  4939.4  277.84  4958.5  276.22  4961.3  275.72  4964.5  276.22  5002.4  277.79
  5494.1  279.25  5617.7  283.17  5818.5   294.7  5889.8  299.28  5954.5  306.41
  5985.9     312  5993.1  317.33  6006.8  322.61    6031  325.05  6352.1  326.77
#Mann= 5 ,-1 , 0
  3247.7     .05       0  3832.8     .16       0  4958.5     .07       0
  4964.5     .16       0  5818.5     .05       0
#XS Ineff= 1 ,-1
  3823.3 4769.89287.1212
Permanent Ineff=
       F
Bank Sta=4939.4,5002.4
XS Rating Curve= 0 ,0
Exp/Cntr=0.3,0.1