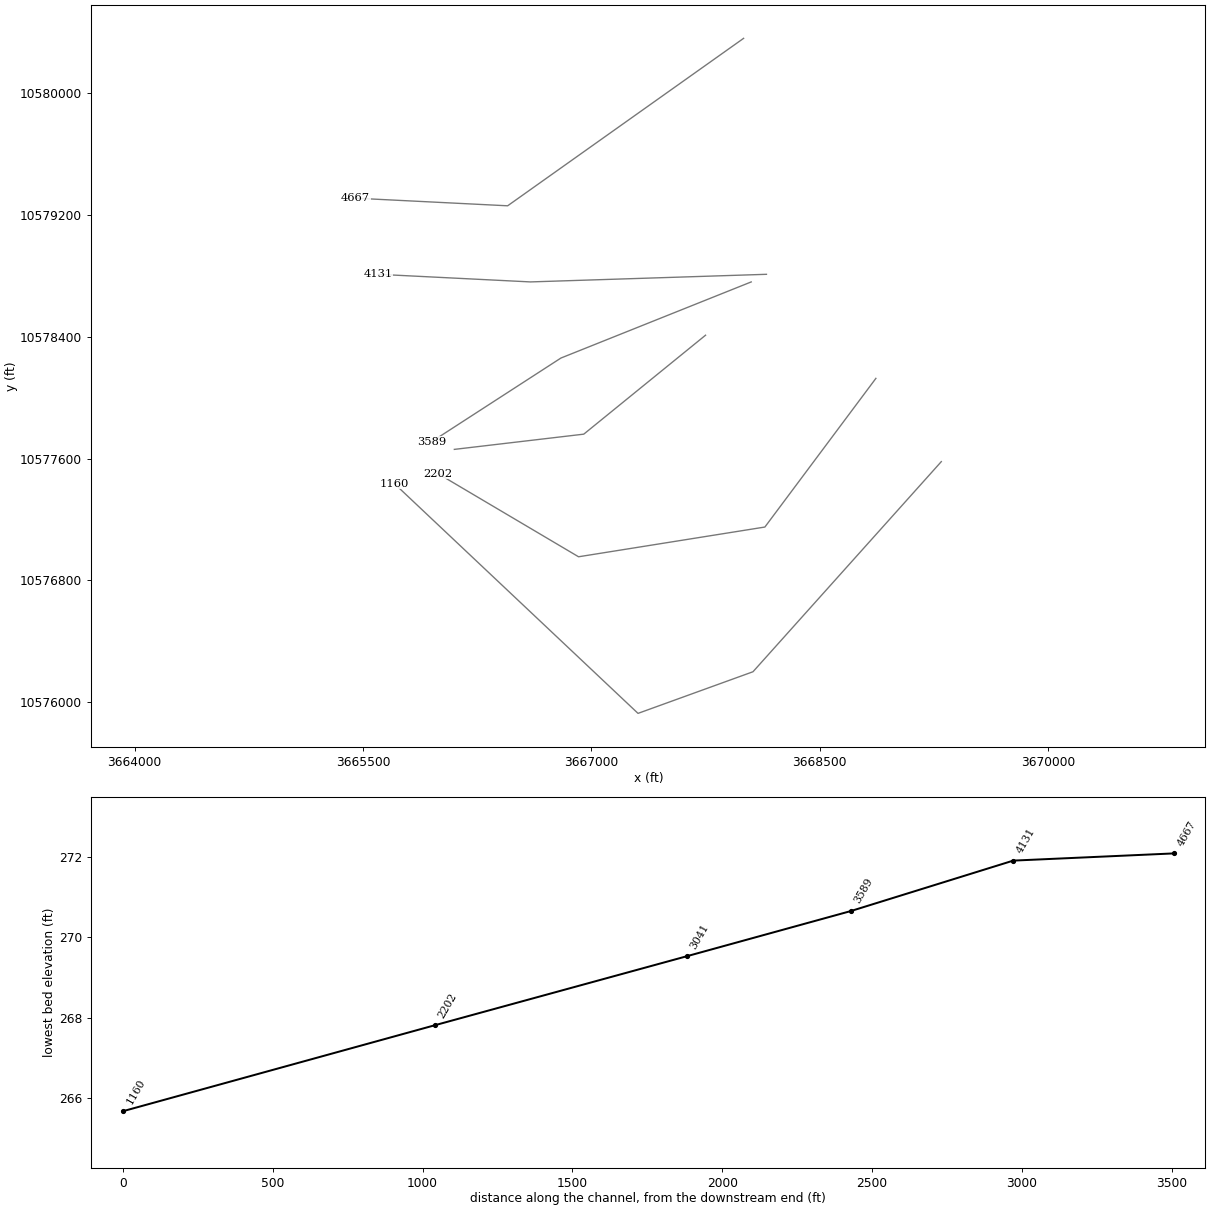
HEC-RAS study JELLY SLOUGH.prj: JELLY SLOUGH Base Level Engineering

--- JELLY SLOUGH.g01 (geometry) --- (continued)

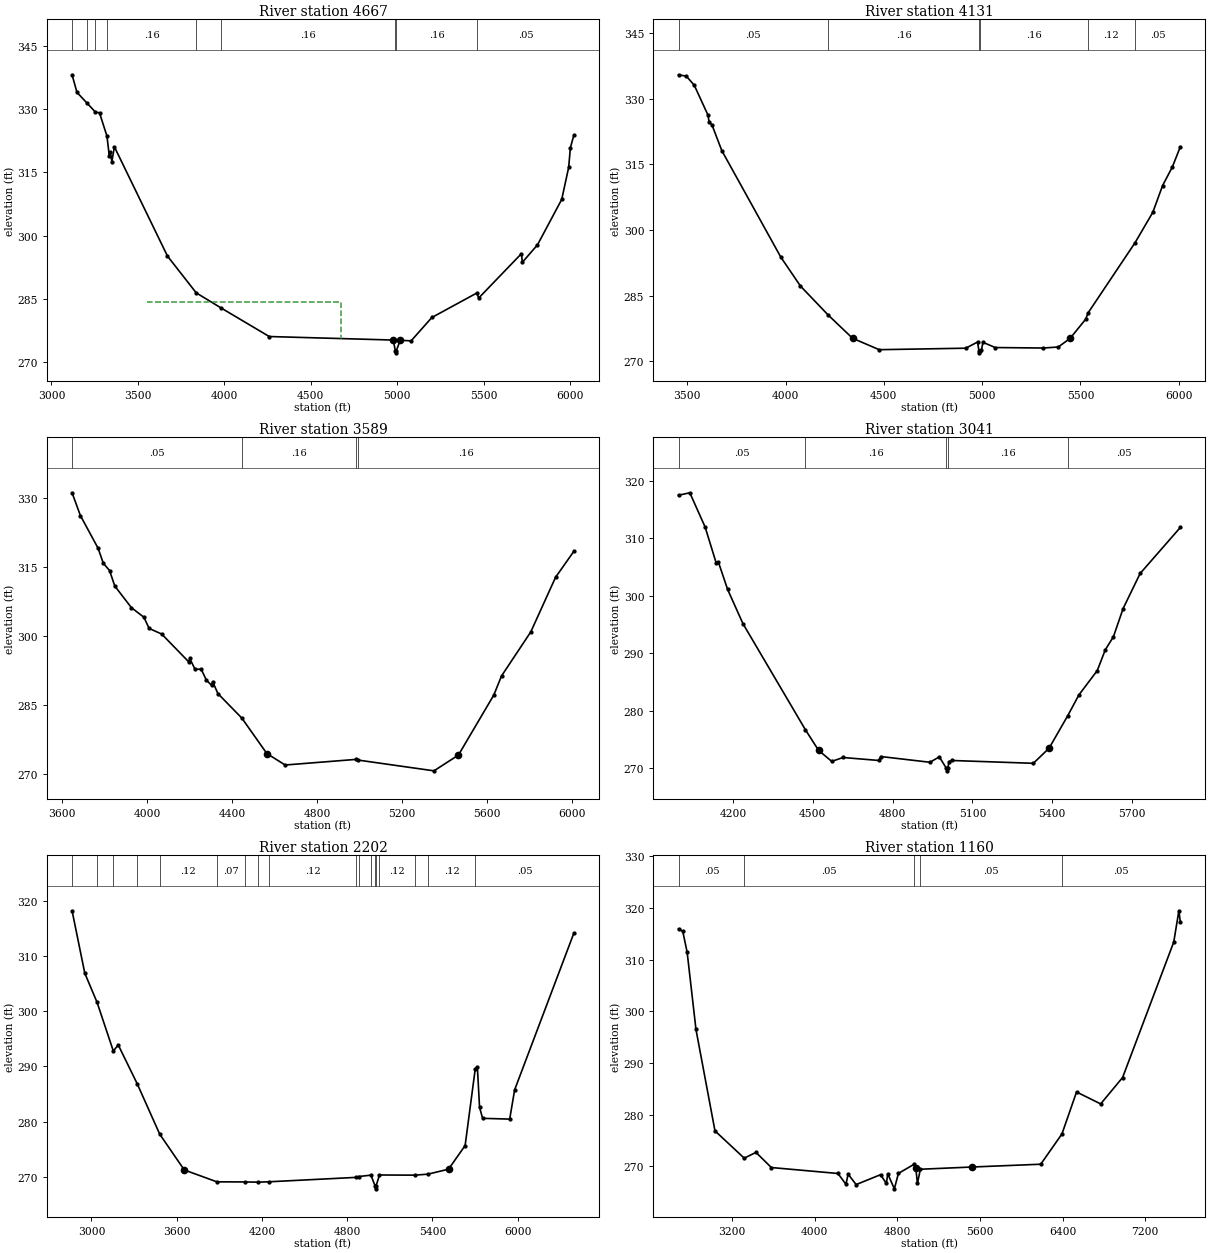
Type RM Length L Ch R = 1 ,4667    ,536,536,536
BEGIN DESCRIPTION:
JELLY SLOUGH 6.0
END DESCRIPTION:
XS GIS Cut Line= 3
      3667999.58     10580360.17      3666449.61     10579260.19
      3665449.58     10579310.19
#Sta/Elev= 30
  3119.3  338.24  3147.6  334.06  3203.1  331.62  3254.3  329.37    3278  329.18
  3321.1  323.65  3334.6  318.89  3340.7  319.82  3349.3  317.58  3364.1   321.1
  3671.1  295.11  3837.2  286.37  3979.2  282.82  4259.7  275.98  4976.9  275.14
  4988.6   272.6  4991.4   272.1  4994.6   272.6  5016.9  275.09    5080  274.95
  5200.1  280.51  5460.5  286.34  5470.5  285.12  5718.3   295.7  5723.3  293.63
  5810.9  297.79  5951.1   308.6  5991.1   316.2  6001.1  320.88  6021.2  323.88
#Mann= 9 ,-1 , 0
  3119.3     .05       0  3203.1     .08       0  3254.3     .05       0
  3321.1     .16       0  3837.2     .05       0  3979.2     .16       0
  4988.6     .07       0  4994.6     .16       0  5460.5     .05       0
#XS Ineff= 1 ,-1
 3552.84 4672.44   284.2
Permanent Ineff=
       F
Bank Sta=4976.9,5016.9
XS Rating Curve= 0 ,0
Exp/Cntr=0.3,0.1

Type RM Length L Ch R = 1 ,4131    ,542,542,542
BEGIN DESCRIPTION:
JELLY SLOUGH 5.0
END DESCRIPTION:
XS GIS Cut Line= 3
       3668149.6     10578810.19      3666599.61     10578760.19
      3665599.56     10578810.19
#Sta/Elev= 30
  3455.7  335.45  3495.7  335.12  3535.7  333.06  3605.8   326.2  3610.8  324.75
  3625.8  323.99  3675.8  318.12    3976  293.78    4076  287.17  4216.1  280.59
  4340.5  275.26  4476.2  272.64  4916.5  272.98  4976.5  274.39  4983.5  272.42
  4986.2  271.92  4989.5  272.42  4996.5  272.61    5004  274.32  5066.6  273.13
  5309.4  273.02    5387  273.25  5447.1  275.22  5527.2  279.65  5537.2  280.95
  5777.5  297.08  5867.6     304  5917.6  310.14  5967.7  314.43  6007.8  319.01
#Mann= 6 ,-1 , 0
  3455.7     .05       0  4216.1     .16       0  4983.5     .07       0
  4989.5     .16       0  5537.2     .12       0  5777.5     .05       0
Bank Sta=4340.5,5447.1
XS Rating Curve= 0 ,0
Exp/Cntr=0.3,0.1

Type RM Length L Ch R = 1 ,3589    ,548,548,548
BEGIN DESCRIPTION:
JELLY SLOUGH 4.0
END DESCRIPTION:
XS GIS Cut Line= 3
       3668049.6     10578760.19      3666799.61     10578260.19
      3665949.61     10577710.19
#Sta/Elev= 30
  3648.1   331.2  3687.1  326.25  3770.6  319.11  3794.8  315.87  3824.5  314.26
  3848.7  310.91  3926.8   306.2    3986  304.09  4010.2  301.67  4069.5  300.44
    4196  294.41  4201.4  295.13  4225.7   292.8  4255.3  292.78  4279.5   290.4
  4303.7  289.29  4309.1  290.07  4333.4  287.49  4446.4  282.13  4563.6  274.43
  4649.7  271.93    4985  273.16  4994.4  272.99  5349.3  270.66  5464.3   274.1
  5630.5  287.16  5666.8  291.32  5804.3  300.91  5920.7  312.79  6006.8  318.46
#Mann= 4 ,-1 , 0
  3648.1     .05       0  4446.4     .16       0    4985     .07       0
  4994.4     .16       0
Bank Sta=4563.6,5464.3
XS Rating Curve= 0 ,0
Exp/Cntr=0.3,0.1

Type RM Length L Ch R = 1 ,3041    ,839,839,839
BEGIN DESCRIPTION:
JELLY SLOUGH 3.0
END DESCRIPTION:
XS GIS Cut Line= 3
      3667749.64     10578410.21      3666949.61     10577760.19
      3666099.59     10577660.19
#Sta/Elev= 30
  3994.9  317.45  4037.3  317.88  4094.8  311.93  4136.7  305.64  4144.4  305.88
  4179.5  301.07    4237  295.13  4471.7  276.69  4521.5  273.09    4571  271.17
  4613.4  271.85  4748.4  271.33  4755.1  272.02  4940.2  271.02  4975.4  271.96
  5001.2  270.03  5003.9  269.53  5007.2  270.03  5012.1  271.14  5022.5  271.33
    5329  270.84  5388.2  273.47  5458.7  279.15  5500.2  282.73  5569.4  286.97
  5599.6  290.59  5629.9  292.83  5666.4  297.74  5730.5  303.85  5881.6  311.85
#Mann= 5 ,-1 , 0
  3994.9     .05       0  4471.7     .16       0  5001.2     .07       0
  5007.2     .16       0  5458.7     .05       0
Bank Sta=4521.5,5388.2
XS Rating Curve= 0 ,0
Exp/Cntr=0.3,0.1

Type RM Length L Ch R = 1 ,2202    ,1042,1042,1042
BEGIN DESCRIPTION:
JELLY SLOUGH 2.0
END DESCRIPTION:
XS GIS Cut Line= 4
      3668868.45     10578126.63      3668139.31      10577150.1
      3666915.35     10576954.79      3665990.85     10577501.68
#Sta/Elev= 30
  2863.4  318.21    2953  306.89  3039.1  301.63  3153.8  292.79  3188.5  293.89
    3322  286.85  3480.4  277.72  3653.4  271.23  3882.7  269.08  4078.4  269.06
  4171.8  269.02  4251.2  269.09  4865.4  269.89  4880.7  270.04  4967.1  270.29
    4997  268.31  4999.7  267.81    5003  268.31  5027.4  270.32  5276.2  270.29
  5368.3  270.47  5513.5  271.37  5630.3  275.66  5701.6  289.57  5716.3  289.94
  5731.9  282.58  5753.4  280.59    5944  280.45  5978.9  285.76  6395.7  314.16
#Mann= 18 ,-1 , 0
  2863.4     .05       0  3039.1     .16       0  3153.8     .05       0
    3322     .16       0  3480.4     .12       0  3882.7     .07       0
  4078.4     .12       0  4171.8     .07       0  4251.2     .12       0
  4865.4     .07       0  4880.7     .12       0  4967.1     .07       0
    4997     .07       0    5003     .07       0  5027.4     .12       0
  5276.2     .07       0  5368.3     .12       0  5701.6     .05       0
Bank Sta=3653.4,5513.5
XS Rating Curve= 0 ,0
Exp/Cntr=0.3,0.1

Type RM Length L Ch R = 1 ,1160    ,0,0,0
BEGIN DESCRIPTION:
JELLY SLOUGH 1.0
END DESCRIPTION:
XS GIS Cut Line= 4
      3669298.18     10577579.81      3668061.19     10576199.58
      3667305.98     10575926.14      3665705.26     10577435.76
#Sta/Elev= 30
  2683.4  315.93  2724.3  315.46  2766.9   311.4  2852.2  296.48  3036.1  276.87
  3319.4  271.59    3433  272.71  3581.8  269.78  4226.2  268.63    4304  266.54
  4324.9   268.5  4402.6  266.48  4638.7   268.4  4694.7  266.71  4708.7  268.56
  4772.2  265.66  4811.9  268.65  4959.9  270.37 4979.36  269.74  4995.8  266.71
  5024.2  269.45  5524.3  269.88  6189.1  270.42  6394.2  276.26  6535.8  284.39
  6769.2  282.08  6981.6  287.19  7476.8  313.39  7526.2  319.43  7540.3  317.25
#Mann= 5 ,-1 , 0
  2683.4     .05       0  3319.4     .05       0  4959.9     .03       0
  5024.2     .05       0  6394.2     .05       0
Bank Sta=4979.36,5524.3
XS Rating Curve= 0 ,0
Exp/Cntr=0.3,0.1

Chan Stop Cuts=-1
Use User Specified Reach Order=0
Composite Channel Slope=5