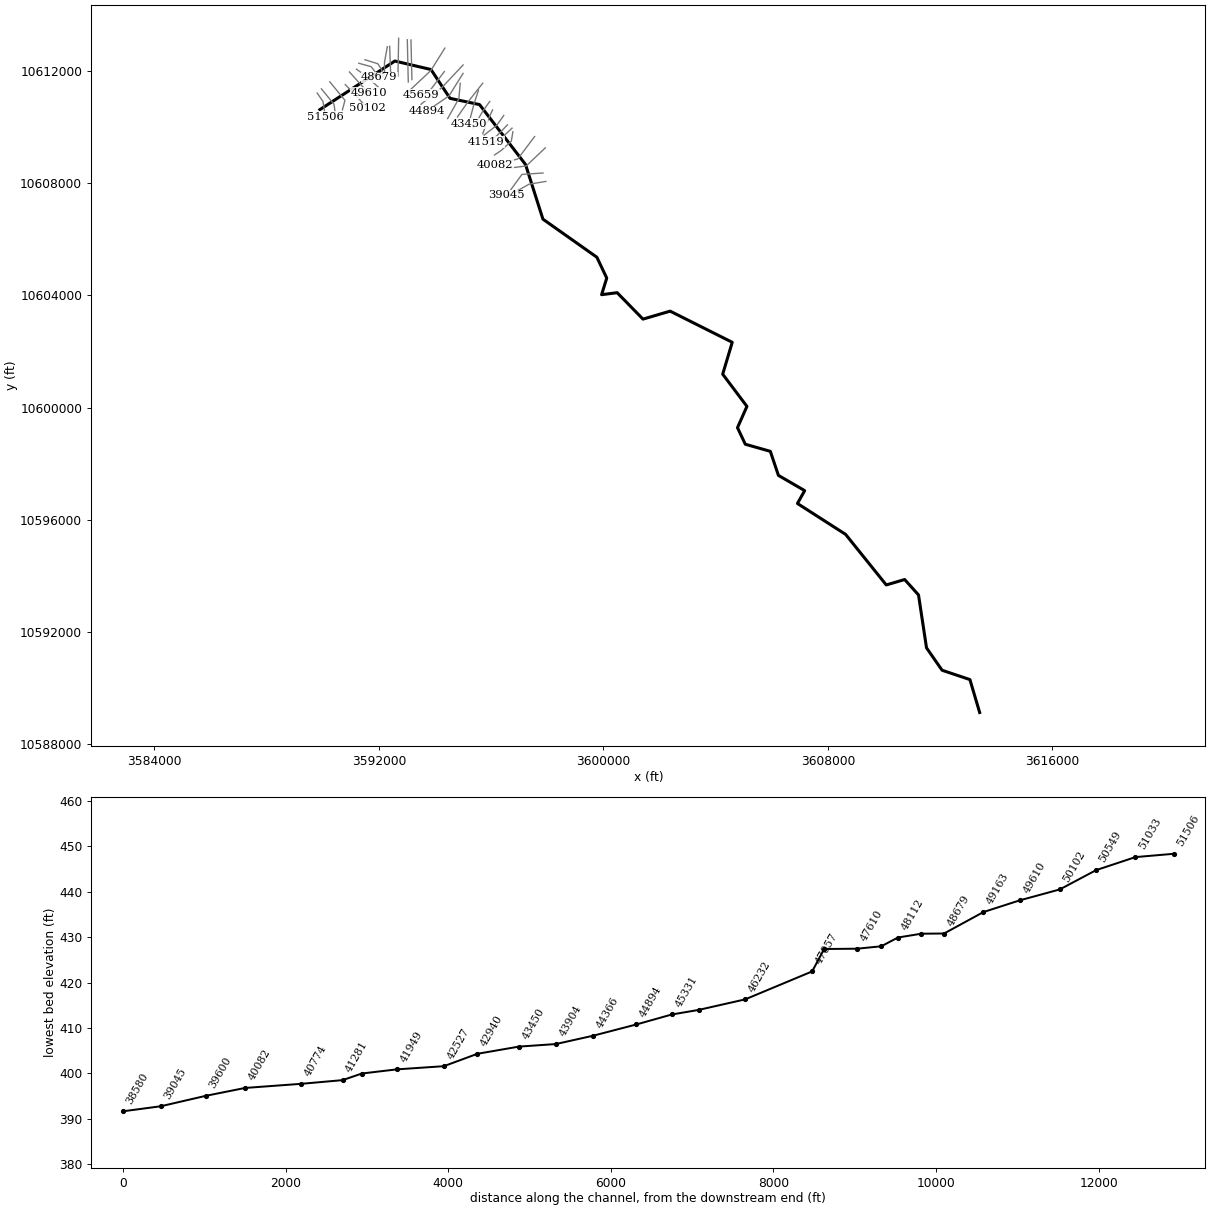
--- MIMS CREEK.prj (project) ---

Proj Title=MIMS CREEK Base Level Engineering
Current Plan=p01
Default Exp/Contr=0.3,0.1
English Units
Geom File=g01
Flow File=f01
Plan File=p01
Y Axis Title=Elevation
X Axis Title(PF)=Main Channel Distance
X Axis Title(XS)=Station
BEGIN DESCRIPTION:
MIMS CREEK
END DESCRIPTION:
DSS File=dss
DSS Export Rating Curves= 0
DSS Export Rating Curve Sorted= 0
DSS Export Volume Flow Curves= 0
DXF OffsetX= 0
DXF OffsetY= 0
DXF ScaleX= 1
DXF ScaleY= 10

--- MIMS CREEK.p01 (plan) ---

Plan Title=Multiple Run
Program Version=4.10
Short Identifier=Multiple Run
Geom File=g01
Flow File=f01
Subcritical Flow
K Sum by GR= 0
Std Step Tol= 0.01
Critical Tol= 0.01
Num of Std Step Trials= 20
Max Error Tol= 0.3
Flow Tol Ratio= 0.001
Split Flow NTrial= 30
Split Flow Tol= 0.02
Split Flow Ratio= 0.02
Log Output Level= 0
Friction Slope Method= 1
Unsteady Friction Slope Method= 2
Unsteady Bridges Friction Slope Method= 1
Parabolic Critical Depth
Global Vel Dist= 1 , 1 , 1
Global Log Level= 0
CheckData=True
Encroach Param=-1 ,0,0, 0
BEGIN DESCRIPTION:
Multiple Run
END DESCRIPTION:
Computation Interval=1HOUR
Output Interval=1HOUR
Run HTab= 0
Run UNet= 0
Run PostProcess= 0
Run WQNet= 0
UNET Theta= 1
UNET Theta Warmup= 1
UNET ZTol= 0.02
UNET ZSATol= 0.05
UNET MxIter= 20
UNET MaxInSteps= 0
UNET DtIC= 0
UNET DtMin= 0
UNET MaxCRTS= 20
UNET WFStab= 2
UNET SFStab= 1
UNET WFX= 1
UNET SFX= 1
UNET DSS MLevel= 4
UNET DZMax Abort= 100
UNET Convert EG Bridges= 0
UNET Use Existing IB Tables=-1
UNET Froude Reduction=False
UNET Froude Limit= 1
UNET Froude Power= 10
UNET Time Slicing=0,0, 5
UNET Junction Losses=0
Instantaneous Interval=1HOUR
DSS File=dss
Write IC File= 0
Write IC File at Sim End=0
Echo Input=False
Echo Parameters=False
Echo Output=False
Write Detailed= 0
WQ AD Non Conservative
WQ ULTIMATE=-1
WQ Max Comp Step=1HOUR
WQ Output Interval=15MIN
WQ Output Selected Increments= 0
WQ Output face flow=0
WQ Output face velocity=0
WQ Output face area=0
WQ Output face dispersion=0
WQ Output cell volume=0
WQ Output cell surface area=0
WQ Output cell continuity=0
WQ Output cumulative cell continuity=0
WQ Output face conc=0
WQ Output face dconc_dx=0
WQ Output face courant=0
WQ Output face peclet=0
WQ Output face adv mass=0
WQ Output face disp mass=0
WQ Output cell mass=0
WQ Output cell source sink temp=0
WQ Output cell source sink nsm=0
WQ Output MaxMinRange=-1
WQ Daily Max Min Mean=-1
WQ Daily Range=0
WQ Daily Time=0
WQ Create Restart=0
WQ Fixed Restart=0
WQ System Summary=0
WQ Use Fixed Temperature=0
Sorting and Armoring Iterations= 10
XS Update Threshold= 0.02
Hydraulics Update Threshold= 0.02
Energy Slope Method= 1
Volume Change Method= 0
XS Weighting Method= 0
Number of US Weighted Cross Sections= 1
Number of DS Weighted Cross Sections= 1
Upstream XS Weight=0.25
Main XS Weight=0.5
Downstream XS Weight=0.25
Number of DS XS's Weighted with US Boundary= 1
Upstream Boundary Weight= 1
Weight of XSs Associated with US Boundary= 0
Number of US XS's Weighted with DS Boundary= 1
Downstream Boundary Weight= 0.5
Weight of XSs Associated with DS Boundary= 0.5
Sediment Output Level= 4
Mass or Volume Output= 0
Output Increment Type= 1
Profile and TS Output Increment= 10
XS Output Flag= 0
XS Output Increment= 10
Disregard all LS=0
Disregard all Conn=0
Disregard all Breaches=0
Disregard all Pumps=0

--- MIMS CREEK.f01 (steady flow) ---

Flow Title=Multiple
Program Version=4.10
Number of Profiles= 7
Profile Names=10-year,25-year,50-year,1pct_min,100-year,1pct_plu,500-year
River Rch & RM=MIMS CREEK,Reach-1         ,51506
     844    1140    1381    1222    1653    2235    2358
River Rch & RM=MIMS CREEK,Reach-1         ,48112
    1221    1684    2069    1854    2507    3391    3669
River Rch & RM=MIMS CREEK,Reach-1         ,46232
    1780    2499    3105    2810    3800    5139    5675
River Rch & RM=MIMS CREEK,Reach-1         ,40082
    2680    3820    4795    4375    5917    8002    8988
River Rch & RM=MIMS CREEK,Reach-1         ,30673
    3350    4821    6088    5587    7556   10218   11607
River Rch & RM=MIMS CREEK,Reach-1         ,29011
    3941    5691    7203    6620    8953   12108   13795
River Rch & RM=MIMS CREEK,Reach-1         ,28350
    3941    5691    7203    6620    8953   12108   13795
River Rch & RM=MIMS CREEK,Reach-1         ,22137
    3944    5688    7194    6606    8934   12083   13743
River Rch & RM=MIMS CREEK,Reach-1         ,20646
    4036    5821    7362    6759    9140   12361   14054
River Rch & RM=MIMS CREEK,Reach-1         ,16229
    4830    7000    8881    8174   11055   14950   17084
River Rch & RM=MIMS CREEK,Reach-1         ,12152
    5678    8264   10514    9700   13118   17741   20367
River Rch & RM=MIMS CREEK,Reach-1         ,7804
    5678    8264   10514    9700   13118   17741   20367
Boundary for River Rch & Prof#=MIMS CREEK,Reach-1         , 1
Up Type= 0
Dn Type= 3
Dn Slope=0.0006
Boundary for River Rch & Prof#=MIMS CREEK,Reach-1         , 2
Up Type= 0
Dn Type= 3
Dn Slope=0.0006
Boundary for River Rch & Prof#=MIMS CREEK,Reach-1         , 3
Up Type= 0
Dn Type= 3
Dn Slope=0.0006
Boundary for River Rch & Prof#=MIMS CREEK,Reach-1         , 4
Up Type= 0
Dn Type= 3
Dn Slope=0.0006
Boundary for River Rch & Prof#=MIMS CREEK,Reach-1         , 5
Up Type= 0
Dn Type= 3
Dn Slope=0.0006
Boundary for River Rch & Prof#=MIMS CREEK,Reach-1         , 6
Up Type= 0
Dn Type= 3
Dn Slope=0.0006
Boundary for River Rch & Prof#=MIMS CREEK,Reach-1         , 7
Up Type= 0
Dn Type= 3
Dn Slope=0.0006
DSS Import GetInterval= 0
DSS Import GetPeak= 0
DSS Import FillOption= 0

--- MIMS CREEK.g01 (geometry) ---

Geom Title=Existing Conditions
Program Version=4.10

River Reach=MIMS CREEK      ,Reach-1
Reach XY= 30
      3589896.75       10610619.      3592568.75       10612350.
       3593856.5       10612047.      3594533.75       10611021.
      3595586.25       10610798.      3597225.25       10608663.
       3597845.5       10606715.        3599767.       10605359.
       3600119.5       10604616.      3599936.25       10604024.
      3600490.75       10604095.      3601411.25       10603153.
      3602378.75       10603437.        3604592.       10602327.
        3604252.       10601191.      3605115.25       10600043.
      3604778.75       10599284.      3605057.75       10598694.
      3605949.75       10598441.      3606237.75       10597584.
      3607173.25       10597041.      3606915.75       10596583.
      3608632.63     10595481.29      3610081.06     10593679.93
      3610737.25       10593873.       3611230.5       10593324.
      3611515.25       10591439.        3612070.       10590640.
       3613062.5       10590307.      3613409.75       10589133.

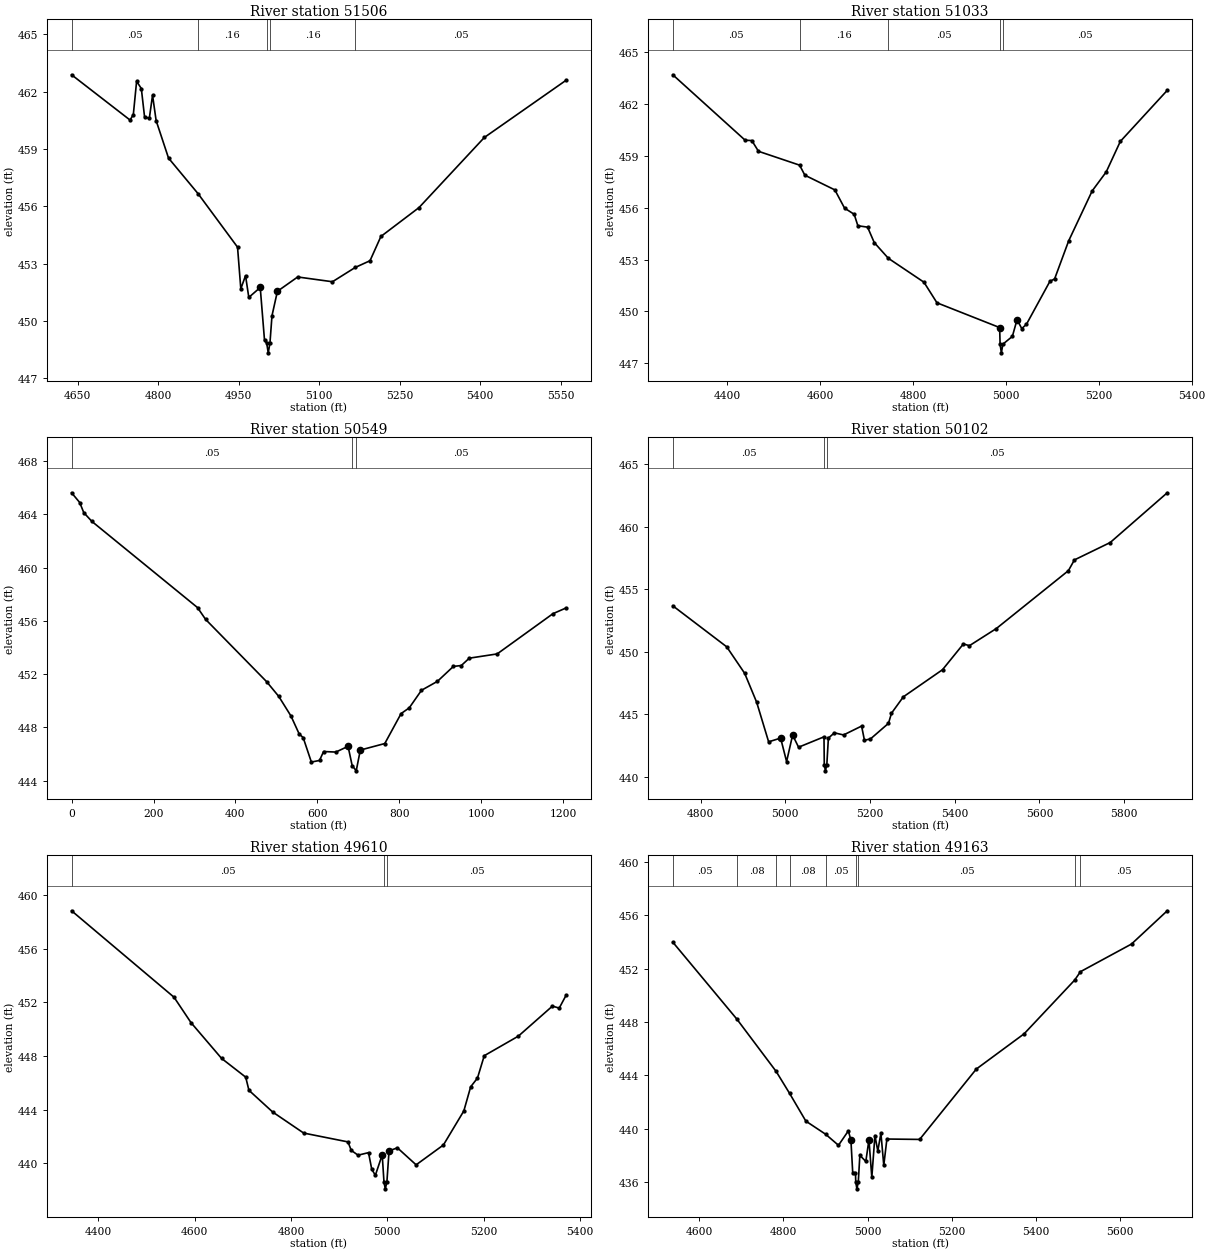
Type RM Length L Ch R = 1 ,51506   ,473,473,473
BEGIN DESCRIPTION:
MIMS CREEK 70.0
END DESCRIPTION:
XS GIS Cut Line= 3
      3589799.62     10611210.18        3590004.       10610912.
       3590099.6     10610360.22
#Sta/Elev= 30
  4638.5  462.89  4747.5  460.52  4753.6  460.81  4759.7  462.55  4768.5  462.17
  4774.5  460.69  4783.4  460.61  4789.4  461.82  4796.1  460.49  4819.2  458.53
  4874.2  456.67  4947.8  453.87  4953.9  451.69  4962.7  452.38  4968.8  451.24
  4990.1  451.76  4998.1  448.99  5002.2  448.84    5005  448.34  5008.2  448.84
    5012  450.28  5022.1  451.56  5059.9  452.31  5124.7  452.06  5167.3  452.81
  5194.7  453.16    5215  454.43    5286  455.94  5407.8  459.61    5560   462.6
#Mann= 5 ,-1 , 0
  4638.5     .05       0  4874.2     .16       0  5002.2     .07       0
  5008.2     .16       0  5167.3     .05       0
Bank Sta=4990.1,5022.1
XS Rating Curve= 0 ,0
Exp/Cntr=0.3,0.1

Type RM Length L Ch R = 1 ,51033   ,484,484,484
BEGIN DESCRIPTION:
MIMS CREEK 69.0
END DESCRIPTION:
XS GIS Cut Line= 3
      3589949.64     10611360.16      3590399.61     10610810.19
       3590449.6     10610460.23
#Sta/Elev= 30
  4283.2  463.67  4438.9  459.89  4453.3  459.87  4467.6  459.25  4556.1  458.45
  4567.4  457.87    4632  457.02  4652.8  455.97  4673.6  455.61  4681.5  454.95
  4702.4  454.87  4716.7  453.98  4747.1  453.07  4823.7  451.69  4851.7   450.5
  4986.6  449.07  4987.6  448.11  4990.3  447.61  4993.6  448.11    5014  448.56
  5024.1  449.53  5034.2  449.01  5044.3  449.26  5094.8  451.74  5104.9  451.88
  5135.2  454.08  5185.7  456.96    5216  458.06  5246.3  459.82  5347.3  462.77
#Mann= 5 ,-1 , 0
  4283.2     .05       0  4556.1     .16       0  4747.1     .05       0
  4987.6     .03       0  4993.6     .05       0
Bank Sta=4986.6,5024.1
XS Rating Curve= 0 ,0
Exp/Cntr=0.3,0.1

Type RM Length L Ch R = 1 ,50549   ,447,447,447
BEGIN DESCRIPTION:
MIMS CREEK 68.0
END DESCRIPTION:
XS GIS Cut Line= 3
     3590249.609    10611610.189     3590789.718    10610949.627
     3590699.609    10610610.189
#Sta/Elev= 30
       0  465.62   19.83  464.89   29.75  464.13   49.58  463.47  307.42     457
  327.26  456.11  476.01  451.44  505.76  450.33  535.56  448.86  555.47  447.52
  565.43  447.23  585.35   445.4  605.27  445.52  615.23  446.19   645.1  446.15
  674.98  446.58  684.94  445.14   694.9  444.74  704.85   446.3  764.61  446.79
  804.44  449.04  824.36  449.47  854.24  450.79  893.13  451.46  932.02  452.58
  951.47  452.65  970.91   453.2 1038.98  453.52  1175.1  456.54 1207.05  456.97
#Mann= 3 ,-1 , 0
       0     .05       0  684.94     .03       0   694.9     .05       0
Bank Sta=674.98,704.85
XS Rating Curve= 0 ,0
Exp/Cntr=0.3,0.1

Type RM Length L Ch R = 1 ,50102   ,492,492,492
BEGIN DESCRIPTION:
MIMS CREEK 67.0
END DESCRIPTION:
XS GIS Cut Line= 3
     3590799.609    10611510.189     3591049.609    10611260.188
     3591599.609    10610660.189
#Sta/Elev= 30
  4734.4  453.69  4861.7  450.41  4904.1  448.29  4932.4  445.98  4960.7  442.81
    4989  443.11  5003.1  441.23  5017.3  443.35  5031.4  442.38  5091.4  443.21
  5092.1  440.99  5094.8  440.49  5098.1  440.99  5101.8  443.11    5116  443.53
  5137.6  443.36  5180.2  444.07  5186.9  442.94  5201.1  443.04  5243.7  444.29
  5250.8   445.1  5278.8  446.41  5371.3  448.58  5420.6  450.64  5434.8   450.5
  5498.3  451.87  5668.5   456.5  5682.7  457.36  5767.2  458.75  5901.9  462.73
#Mann= 3 ,-1 , 0
  4734.4     .05       0  5092.1     .03       0  5098.1     .05       0
Bank Sta=4989,5017.3
XS Rating Curve= 0 ,0
Exp/Cntr=0.3,0.1

Type RM Length L Ch R = 1 ,49610   ,447,447,447
BEGIN DESCRIPTION:
MIMS CREEK 66.0
END DESCRIPTION:
XS GIS Cut Line= 3
       3590949.6      10611960.2      3591399.61     10611460.19
      3591649.58     10611210.22
#Sta/Elev= 30
  4344.8  458.83  4557.5  452.38  4592.6  450.49  4656.1  447.82  4706.2  446.42
  4712.9  445.44  4762.2  443.82  4826.5  442.25  4918.5  441.59  4925.2  440.96
  4939.4   440.6  4961.1  440.79  4967.8  439.55  4975.3   439.1  4989.5  440.63
  4993.2  438.59  4995.9  438.09  4999.2  438.59  5003.7  440.92    5021  441.15
  5059.9  439.88  5116.5  441.36  5158.9   443.9  5173.1   445.7  5187.2  446.35
  5201.3  448.02  5272.1  449.48  5342.8  451.72  5356.9  451.57    5371  452.52
#Mann= 3 ,-1 , 0
  4344.8     .05       0  4993.2     .03       0  4999.2     .05       0
Bank Sta=4989.5,5003.7
XS Rating Curve= 0 ,0
Exp/Cntr=0.3,0.1

Type RM Length L Ch R = 1 ,49163   ,484,484,484
BEGIN DESCRIPTION:
MIMS CREEK 65.0
END DESCRIPTION:
XS GIS Cut Line= 3
      3591199.64     10612060.16      3591549.61     10611810.19
      3592099.63     10611310.17
#Sta/Elev= 30
  4537.9  453.98  4689.9  448.22  4783.2   444.3    4815  442.66  4853.7  440.58
  4900.5   439.6  4931.1  438.77  4954.5  439.85  4960.6  439.16  4964.9  436.72
  4971.4  436.72  4972.1  436.01  4974.8  435.51  4978.1  436.01  4981.8  438.02
    4996  437.56  5003.4  439.19  5010.2  436.37  5017.6   439.5  5024.4  438.35
  5031.8  439.67  5038.6  437.27    5046  439.24  5123.7  439.21  5258.2  444.48
  5371.7  447.12  5491.6  451.14  5505.4  451.77  5626.5  453.84  5711.3  456.33
#Mann= 9 ,-1 , 0
  4537.9     .05       0  4689.9     .08       0  4783.2     .05       0
    4815     .08       0  4900.5     .05       0  4972.1     .03       0
  4978.1     .05       0  5491.6     .08       0  5505.4     .05       0
Bank Sta=4960.6,5003.4
XS Rating Curve= 0 ,0
Exp/Cntr=0.3,0.1

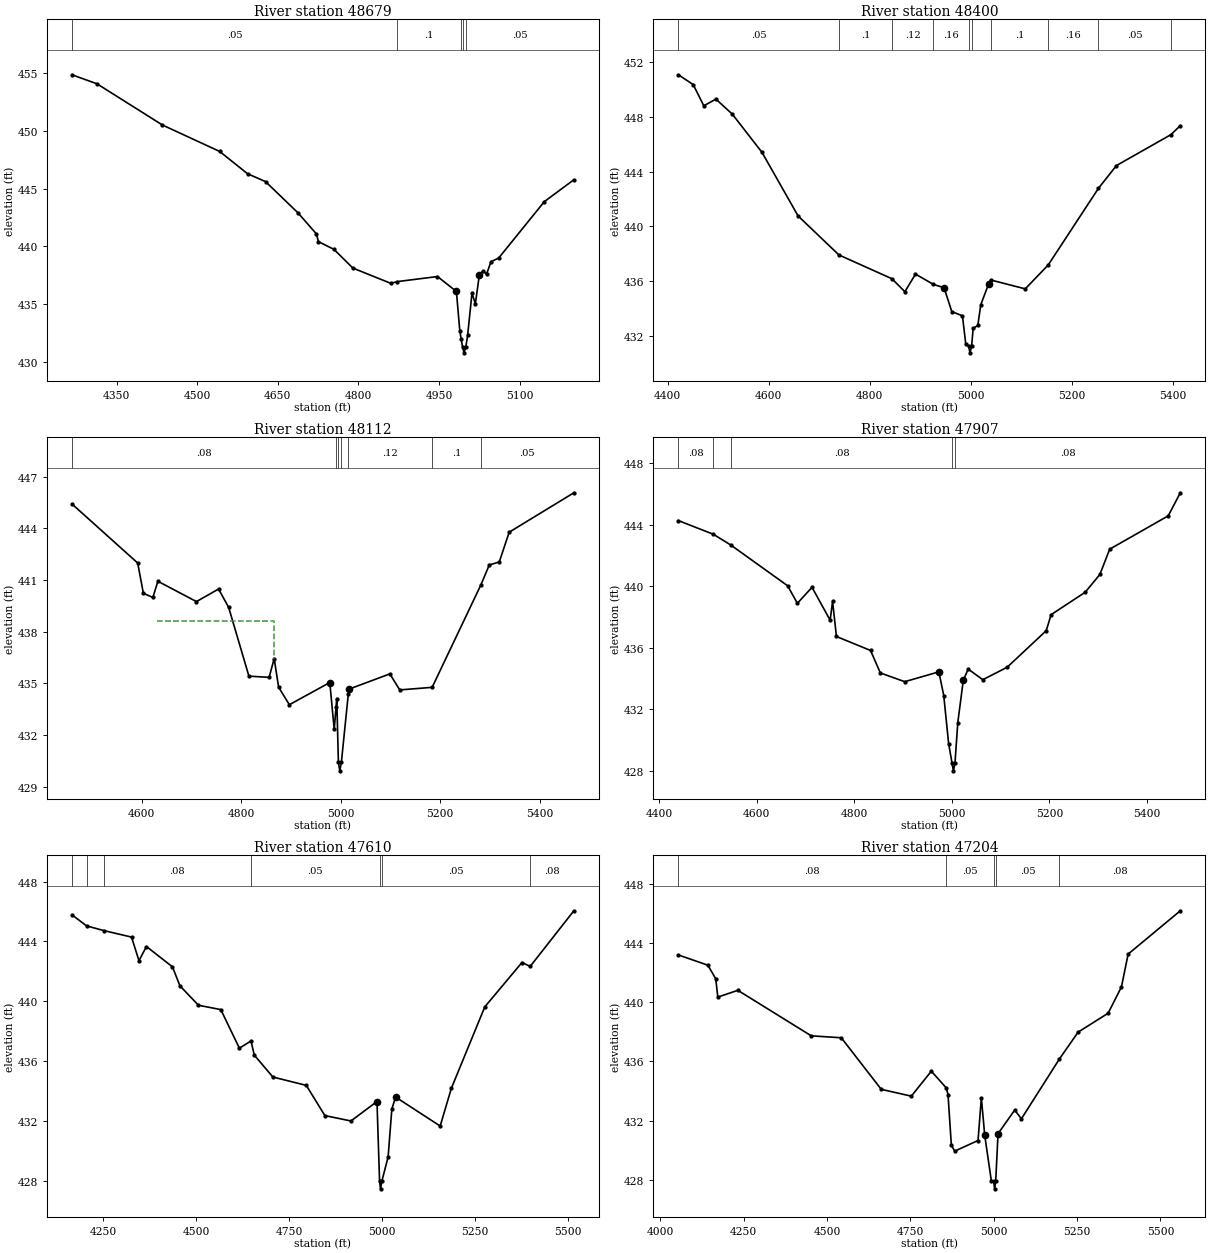
Type RM Length L Ch R = 1 ,48679   ,279,279,279
BEGIN DESCRIPTION:
Mapping XS 807b26af
END DESCRIPTION:
XS GIS Cut Line= 3
      3591284.66     10612270.71        3591723.     10612149.18
      3592018.12     10611771.61
#Sta/Elev= 30
  4266.8  454.84  4313.4  454.06    4435   450.5  4541.7  448.21  4593.6  446.28
  4627.1   445.6    4687  442.92  4721.7  441.08  4725.5  440.41  4754.4  439.74
  4789.7  438.12  4860.3   436.8  4872.1  436.95  4947.1  437.39  4982.3   436.1
  4988.7  432.66  4991.3  431.96  4993.8  431.29  4996.6  430.79  4999.8  431.29
  5003.2   432.3  5011.3  435.96  5017.6  435.03    5025  437.52  5032.1  437.89
  5038.4  437.59  5046.6  438.67    5061  438.99    5146  443.87  5200.9  445.76
#Mann= 5 ,-1 , 0
  4266.8     .05       0  4872.1      .1       0  4991.3     .05       0
  4993.8     .03       0  4999.8     .05       0
Bank Sta=4982.3,5025
XS Rating Curve= 0 ,0
Exp/Cntr=0.3,0.1

Type RM Length L Ch R = 1 ,48400   ,288,288,288
BEGIN DESCRIPTION:
MIMS CREEK 64.0
END DESCRIPTION:
XS GIS Cut Line= 4
      3591501.62     10612396.59      3591961.71     10612253.35
       3592100.6     10612036.34      3592135.28     10611784.94
#Sta/Elev= 30
  4421.1  451.09  4450.4  450.37  4471.4  448.82  4495.3  449.31  4527.8  448.21
  4586.6  445.41    4658  440.76  4738.8  437.91  4843.7  436.17  4869.3  435.22
  4890.3  436.51  4925.6  435.76  4946.9  435.51  4962.1  433.77  4983.2  433.46
  4989.8  431.39  4995.4  431.25  4998.2  430.75  5001.4  431.25  5004.4  432.54
  5013.6  432.75  5019.6  434.28  5034.8  435.77  5039.2  436.08  5107.5  435.43
  5152.8  437.17  5252.3  442.78    5288  444.45  5395.8  446.71  5414.4  447.37
#Mann= 10 ,-1 , 0
  4421.1     .05       0  4738.8      .1       0  4843.7     .12       0
  4925.6     .16       0  4995.4     .07       0  5001.4     .16       0
  5039.2      .1       0  5152.8     .16       0  5252.3     .05       0
  5395.8     .08       0
Bank Sta=4946.9,5034.8
XS Rating Curve= 0 ,0
Exp/Cntr=0.3,0.1

Type RM Length L Ch R = 1 ,48112   ,205,205,205
BEGIN DESCRIPTION:
MIMS CREEK 63.0
END DESCRIPTION:
XS GIS Cut Line= 3
      3592299.62     10612860.24      3592199.61     10612310.19
      3592199.61     10611860.15
#Sta/Elev= 30
  4459.8  445.41    4592  441.98  4603.4  440.22  4622.5  439.98  4632.6  440.92
  4710.1  439.74  4754.6  440.47  4774.9   439.4  4815.6  435.41  4856.2  435.34
  4866.4  436.43  4875.3  434.77  4896.9  433.75  4978.2  435.04  4987.1  432.32
  4990.8  433.62  4992.2  434.11  4995.5  430.41  4998.3  429.91  5001.5  430.41
  5015.4  434.36  5016.3  434.65  5098.9  435.54  5118.9  434.61    5184  434.76
    5282  440.71  5298.9  441.87  5318.9  442.04  5338.9  443.77  5468.9  446.06
#Mann= 7 ,-1 , 0
  4459.8     .08       0  4990.8     .05       0  4995.5     .04       0
  5001.5     .05       0  5015.4     .12       0    5184      .1       0
    5282     .05       0
#XS Ineff= 1 ,-1
 4630.45  4866.4  438.64
Permanent Ineff=
       F
Bank Sta=4978.2,5016.3
XS Rating Curve= 0 ,0
Exp/Cntr=0.3,0.1

Type RM Length L Ch R = 1 ,47907   ,297,297,297
BEGIN DESCRIPTION:
MIMS CREEK 62.0
END DESCRIPTION:
XS GIS Cut Line= 2
      3592382.72     10612874.03      3592421.78     10611845.37
#Sta/Elev= 30
  4439.2  444.26  4510.9  443.37  4546.7  442.67  4663.2  440.02  4683.2  438.88
  4713.2  439.92  4750.4  437.78  4755.4     439  4763.3  436.72  4833.3  435.81
  4853.3  434.35  4903.4  433.78  4973.4  434.42  4983.4  432.88  4993.4  429.75
  5000.4  428.48  5003.2  427.98  5006.4  428.48  5012.2  431.12  5023.5  433.87
  5033.5   434.6  5063.5  433.91  5113.5  434.72  5193.6   437.1  5203.6  438.14
  5273.6   439.6  5303.7  440.76  5323.7   442.4  5443.8  444.57  5468.6  446.07
#Mann= 5 ,-1 , 0
  4439.2     .08       0  4510.9     .05       0  4546.7     .08       0
  5000.4     .07       0  5006.4     .08       0
Bank Sta=4973.4,5023.5
XS Rating Curve= 0 ,0
Exp/Cntr=0.3,0.1

Type RM Length L Ch R = 1 ,47610   ,406,406,406
BEGIN DESCRIPTION:
Mapping XS cef9cb82
END DESCRIPTION:
XS GIS Cut Line= 2
       3592703.9      10613160.5      3592677.86     10611810.65
#Sta/Elev= 30
  4165.8  445.78  4205.1  445.04  4250.8  444.73  4326.1  444.29  4346.1  442.71
  4366.2  443.66  4436.2   442.3  4456.2  441.03  4506.2  439.73  4566.2  439.44
  4616.2  436.86  4647.5  437.34  4656.2   436.4  4706.2  434.93  4796.2  434.37
  4846.2  432.35  4916.3  431.99  4986.3  433.29  4993.3  427.95    4996  427.45
  4999.3  427.95  5016.3  429.59  5026.3  432.79  5036.3  433.59  5156.3  431.65
  5186.3  434.17  5276.3  439.62  5376.3  442.59  5398.5  442.33  5515.9  446.05
#Mann= 7 ,-1 , 0
  4165.8     .08       0  4205.1     .05       0  4250.8     .08       0
  4647.5     .05       0  4993.3     .04       0  4999.3     .05       0
  5398.5     .08       0
Bank Sta=4986.3,5036.3
XS Rating Curve= 0 ,0
Exp/Cntr=0.3,0.1

Type RM Length L Ch R = 1 ,47204   ,147,147,147
BEGIN DESCRIPTION:
MIMS CREEK 61.0
END DESCRIPTION:
XS GIS Cut Line= 2
      3593012.06     10613108.37      3593046.75     10611603.77
#Sta/Elev= 30
  4054.8   443.2    4143  442.51  4166.7  441.59    4173  440.35    4233  440.81
  4453.1  437.73  4543.1   437.6  4663.1  434.11  4753.2  433.65  4813.2  435.34
  4857.9  434.21  4863.2  433.76  4873.2  430.34  4883.2  429.93  4953.2  430.65
  4963.2  433.53  4973.2  431.02  4993.2  427.91  5000.2  427.88    5003  427.38
  5006.2  427.88  5013.2  431.11  5063.2  432.71  5083.3  432.12  5197.4  436.17
  5253.3  437.98  5343.3  439.26  5383.3  441.04  5403.3  443.26  5559.8  446.19
#Mann= 5 ,-1 , 0
  4054.8     .08       0  4857.9     .05       0  5000.2     .03       0
  5006.2     .05       0  5197.4     .08       0
Bank Sta=4973.2,5013.2
XS Rating Curve= 0 ,0
Exp/Cntr=0.3,0.1

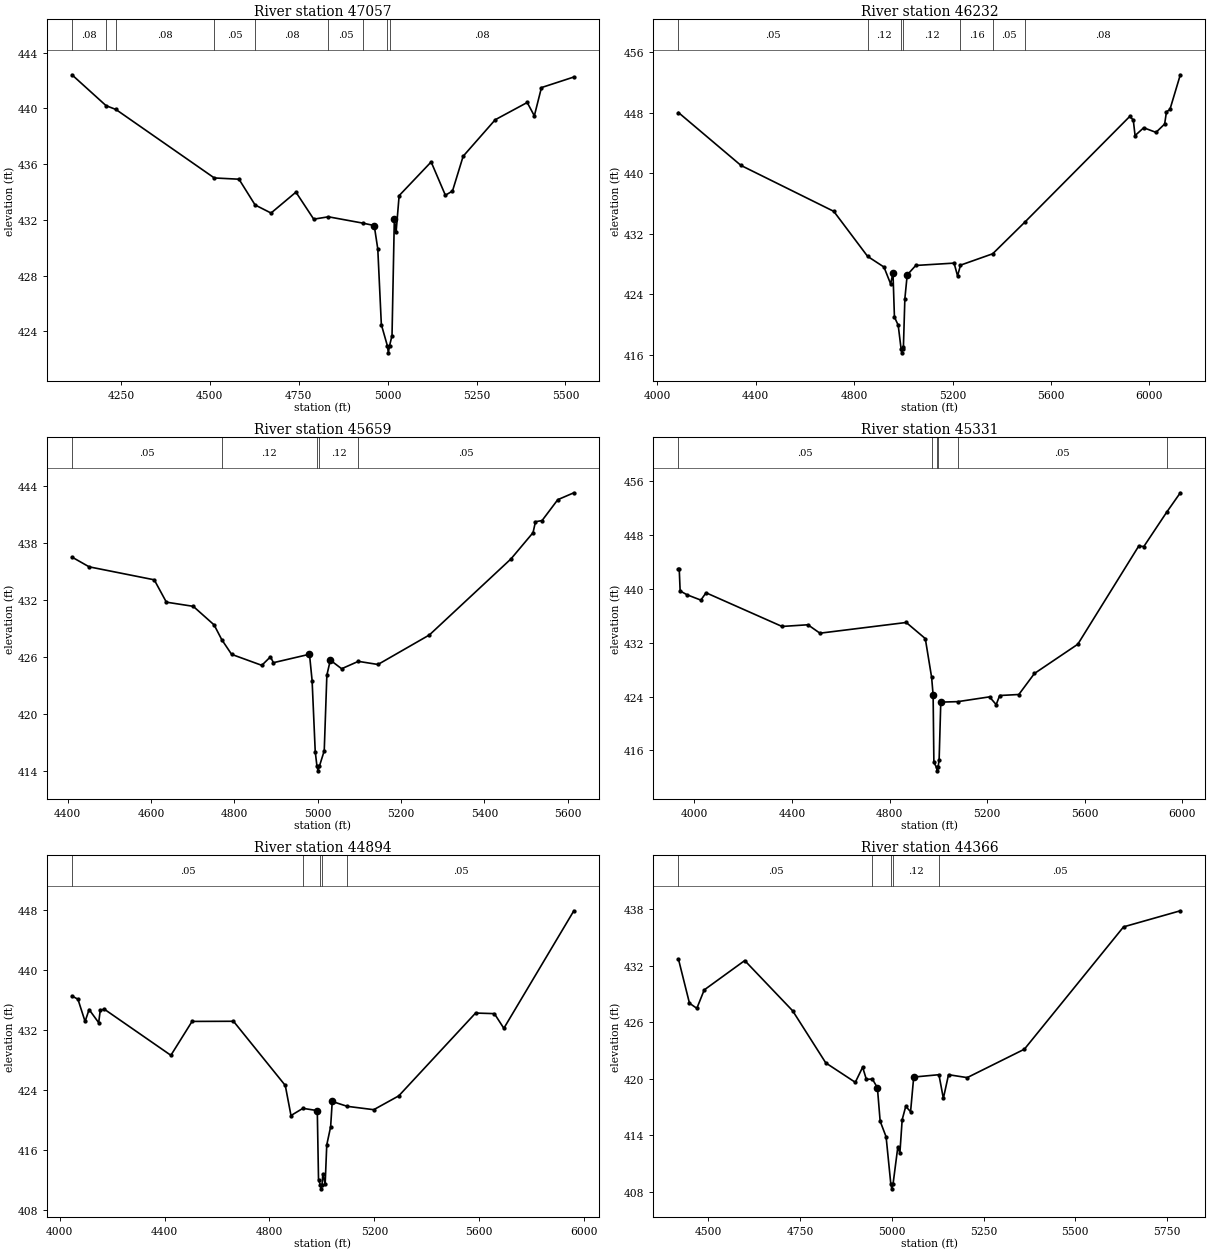
Type RM Length L Ch R = 1 ,47057   ,825,825,825
BEGIN DESCRIPTION:
MIMS CREEK 60.0
END DESCRIPTION:
XS GIS Cut Line= 2
      3593142.27     10613099.69      3593176.99     10611689.12
#Sta/Elev= 30
  4112.5  442.42  4208.5   440.2    4236  439.93  4512.7  435.01  4582.1  434.92
  4627.4  433.07  4672.2  432.49  4742.2  433.99  4792.2  432.05  4833.5  432.22
  4931.5  431.76  4962.3  431.59  4972.3  429.91  4982.3  424.48  4999.3  422.95
    5002  422.45  5005.3  422.95  5012.3  423.69  5018.8  432.03  5023.8  431.13
  5032.3  433.74  5122.3  436.16  5162.3  433.77  5182.3  434.07  5212.3  436.57
  5302.4  439.19  5392.4  440.43  5412.4  439.47  5432.4   441.5  5523.5  442.26
#Mann= 9 ,-1 , 0
  4112.5     .08       0  4208.5     .05       0    4236     .08       0
  4512.7     .05       0  4627.4     .08       0  4833.5     .05       0
  4931.5     .08       0  4999.3     .07       0  5005.3     .08       0
Bank Sta=4962.3,5018.8
XS Rating Curve= 0 ,0
Exp/Cntr=0.3,0.1

Type RM Length L Ch R = 1 ,46232   ,573,573,573
BEGIN DESCRIPTION:
MIMS CREEK 59.0
END DESCRIPTION:
XS GIS Cut Line= 3
      3594349.62     10612810.21      3593849.61     10612010.19
      3593049.62      10611260.2
#Sta/Elev= 30
  4085.6     448  4339.8  441.02  4717.1  434.96  4854.6  429.02  4921.1  427.61
  4948.2  425.38  4957.7  426.86  4963.6  421.01  4978.9  419.94  4990.7  416.79
  4993.4  416.29  4996.7  416.79  5000.1  417.05    5006  423.43  5015.5  426.57
  5050.3  427.82  5206.1  428.13  5220.2  426.44  5232.1  427.86  5362.9  429.36
  5493.7  433.54  5920.2  447.49  5934.4  447.01  5941.7  444.96  5976.9  445.99
  6026.7  445.38  6061.9  446.48  6069.2  448.09  6083.3   448.4  6125.6  452.98
#Mann= 7 ,-1 , 0
  4085.6     .05       0  4854.6     .12       0  4990.7     .07       0
  4996.7     .12       0  5232.1     .16       0  5362.9     .05       0
  5493.7     .08       0
Bank Sta=4957.7,5015.5
XS Rating Curve= 0 ,0
Exp/Cntr=0.3,0.1

Type RM Length L Ch R = 1 ,45659   ,328,328,328
BEGIN DESCRIPTION:
MIMS CREEK 58.0
END DESCRIPTION:
XS GIS Cut Line= 3
      3594331.51     10611975.58       3593845.4     10611333.21
      3593498.13     10611137.88
#Sta/Elev= 30
  4410.6  436.54  4451.9  435.51    4608  434.14  4637.1  431.78  4701.6  431.34
  4751.6  429.38    4770  427.82  4793.6  426.27    4866  425.11  4886.8  426.01
  4893.9  425.39  4980.4  426.28  4986.7   423.5  4994.2     416  4998.3  414.47
    5001  413.97  5004.3  414.47  5015.8  416.09  5022.1  424.07  5030.4  425.66
  5057.5  424.75  5097.6  425.53  5144.7   425.2  5268.1  428.32  5463.8  436.35
  5516.7  439.12  5522.5  440.27  5538.4   440.4    5576   442.6  5614.6  443.33
#Mann= 5 ,-1 , 0
  4410.6     .05       0    4770     .12       0  4998.3     .07       0
  5004.3     .12       0  5097.6     .05       0
Bank Sta=4980.4,5030.4
XS Rating Curve= 0 ,0
Exp/Cntr=0.3,0.1

Type RM Length L Ch R = 1 ,45331   ,437,437,437
BEGIN DESCRIPTION:
MIMS CREEK 57.0
END DESCRIPTION:
XS GIS Cut Line= 3
      3594999.59     10612210.17      3594249.61     10611410.19
      3593499.63     10610810.21
#Sta/Elev= 30
  3934.8  442.88  3938.2  442.88  3941.9  439.67  3970.2   439.1  4026.8  438.31
  4047.9   439.4  4359.5   434.4  4465.5  434.65  4514.8   433.4  4868.5  434.99
  4946.6   432.6  4972.6  426.83 4978.69  424.21  4981.8  414.21  4992.9  413.47
  4995.7  412.97  4998.9  413.47  5003.3   414.6  5010.1  423.17  5079.9  423.24
  5209.8  423.95  5237.1   422.8  5251.5  424.15  5329.9   424.3  5393.9  427.42
  5571.6  431.76  5821.3  446.33  5842.2  446.26  5935.2  451.32  5991.8  454.24
#Mann= 6 ,-1 , 0
  3934.8     .05       0  4972.6     .12       0  4992.9     .07       0
  4998.9     .12       0  5079.9     .05       0  5935.2     .08       0
Bank Sta=4978.69,5010.1
XS Rating Curve= 0 ,0
Exp/Cntr=0.3,0.1

Type RM Length L Ch R = 1 ,44894   ,528,528,528
BEGIN DESCRIPTION:
MIMS CREEK 56.0
END DESCRIPTION:
XS GIS Cut Line= 3
      3594999.58     10611910.15      3594499.61     10611110.19
      3593699.59     10610560.17
#Sta/Elev= 30
  4046.6  436.56  4069.5  436.11  4096.7  433.14    4112  434.74  4148.6  432.98
  4154.5  434.64  4169.8  434.79  4423.9  428.62  4504.7  433.15  4662.7  433.17
  4860.2  424.59    4882  420.57  4927.4  421.53  4982.3  421.23    4987  411.99
  4994.4  411.27  4997.1  410.77  5000.4  411.27  5003.5  412.79  5012.3  411.39
  5018.4  416.64  5033.2  419.07  5039.3  422.45  5096.3   421.8  5197.6  421.35
  5293.1   423.2    5586  434.27  5657.7  434.19  5693.8  432.23  5960.8  447.94
#Mann= 5 ,-1 , 0
  4046.6     .05       0  4927.4     .16       0  4994.4     .07       0
  5000.4     .16       0  5096.3     .05       0
Bank Sta=4982.3,5039.3
XS Rating Curve= 0 ,0
Exp/Cntr=0.3,0.1

Type RM Length L Ch R = 1 ,44366   ,462,462,462
BEGIN DESCRIPTION:
MIMS CREEK 55.0
END DESCRIPTION:
XS GIS Cut Line= 3
      3594899.61     10611560.16      3594849.61     10611010.19
      3594448.68     10610300.21
#Sta/Elev= 30
  4418.5  432.74  4448.6  428.04  4468.7  427.49  4488.8  429.45  4599.2  432.57
  4729.8  427.23  4820.1  421.69  4900.5  419.63  4920.5  421.24  4930.6  419.94
  4946.9  419.98  4960.7  419.06  4968.2   415.5  4984.4  413.84  4997.3  408.81
  5000.1  408.31  5003.3  408.81  5016.3  412.74    5022  412.13  5028.2  415.66
  5037.9  417.07  5051.1  416.51  5059.6  420.19  5128.4  420.44  5140.4  417.92
  5154.5  420.44  5205.4  420.13  5361.2  423.15  5631.4  436.15  5786.1  437.86
#Mann= 5 ,-1 , 0
  4418.5     .05       0  4946.9     .12       0  4997.3     .07       0
  5003.3     .12       0  5128.4     .05       0
Bank Sta=4960.7,5059.6
XS Rating Curve= 0 ,0
Exp/Cntr=0.3,0.1

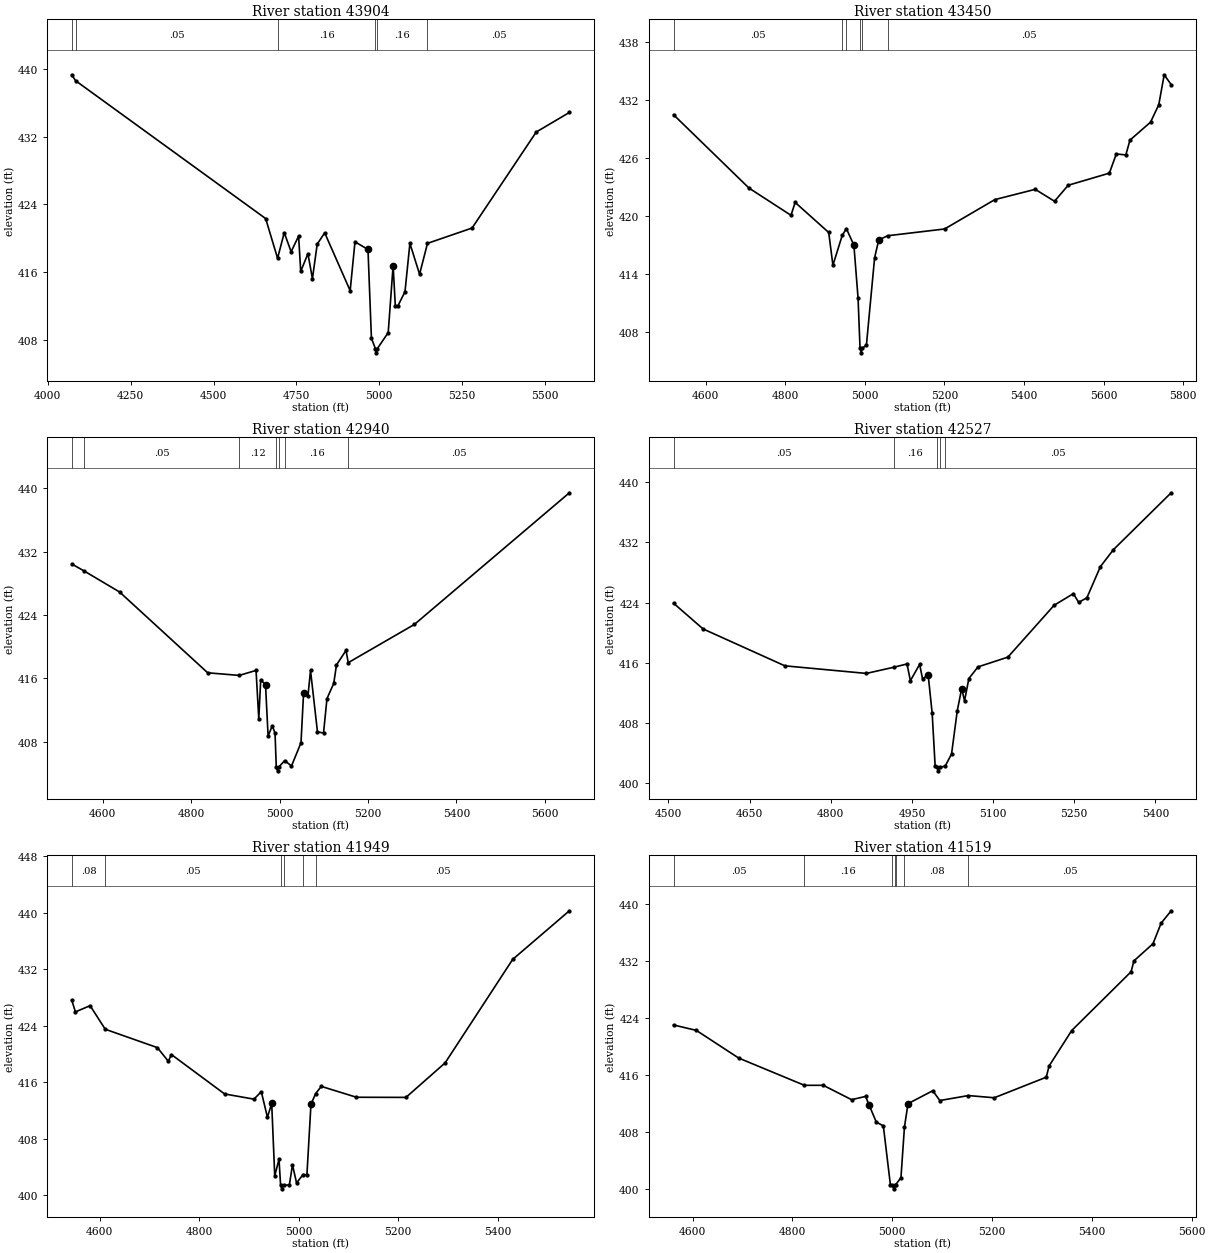
Type RM Length L Ch R = 1 ,43904   ,454,454,454
BEGIN DESCRIPTION:
MIMS CREEK 54.0
END DESCRIPTION:
XS GIS Cut Line= 3
      3595699.61     10611560.19      3595149.61     10610860.19
      3594799.58     10610360.15
#Sta/Elev= 30
  4072.4   439.3    4084   438.6  4657.1  422.32  4693.1  417.63  4713.2  420.65
    4734   418.4  4756.5  420.25  4762.9  416.08  4784.6  418.17  4798.2  415.22
  4812.6   419.3  4835.2  420.63    4912   413.8  4926.5  419.57  4965.7  418.67
  4976.1  408.18    4988  406.96  4990.7  406.46    4994  406.96  5026.7  408.85
  5041.5  416.77  5048.1  412.03  5056.4  412.04  5077.3  413.68  5092.1  419.39
  5121.3  415.74  5145.1  419.39  5279.6   421.2  5473.1  432.54    5573  434.85
#Mann= 6 ,-1 , 0
  4072.4     .08       0    4084     .05       0  4693.1     .16       0
    4988     .07       0    4994     .16       0  5145.1     .05       0
Bank Sta=4965.7,5041.5
XS Rating Curve= 0 ,0
Exp/Cntr=0.3,0.1

Type RM Length L Ch R = 1 ,43450   ,510,510,510
BEGIN DESCRIPTION:
MIMS CREEK 53.0
END DESCRIPTION:
XS GIS Cut Line= 3
      3595549.61      10611310.2      3595399.61     10610860.19
       3595199.6     10610110.15
#Sta/Elev= 30
    4519  430.47  4708.7   422.9  4814.2  420.09  4824.7  421.42    4909  418.32
  4919.6  414.94  4943.1  418.03  4953.5  418.71  4972.3  417.01  4982.8  411.54
  4987.7   406.4  4990.5   405.9  4993.7   406.4  5003.7  406.67  5024.4  415.72
  5034.7  417.54  5056.9  417.98  5200.3  418.68  5326.5  421.71    5428  422.77
  5476.5  421.54  5510.8  423.19  5614.3  424.44  5631.8  426.42  5655.7  426.32
  5666.1  427.85  5717.8   429.7  5738.5   431.5  5752.1  434.59  5769.6  433.58
#Mann= 6 ,-1 , 0
    4519     .05       0  4943.1     .16       0  4953.5     .12       0
  4987.7     .07       0  4993.7     .12       0  5056.9     .05       0
Bank Sta=4972.3,5034.7
XS Rating Curve= 0 ,0
Exp/Cntr=0.3,0.1

Type RM Length L Ch R = 1 ,42940   ,413,413,413
BEGIN DESCRIPTION:
MIMS CREEK 52.0
END DESCRIPTION:
XS GIS Cut Line= 3
      3595949.63     10610910.22      3595699.61     10610560.19
       3595349.6     10609960.17
#Sta/Elev= 30
  4530.4  430.44    4558  429.57  4638.6   426.9  4837.7   416.7  4908.9  416.37
    4947     417  4953.2  410.87  4957.5   415.8  4968.4   415.2  4974.2  408.73
  4983.7  409.99  4989.9   409.1  4992.7  404.82  4995.5  404.32  4998.7  404.82
  5011.7  405.61  5027.1  404.93  5048.6  407.87  5054.4  414.15  5064.3  413.76
  5070.1  416.99  5085.8  409.25  5099.5  409.09  5107.3  413.44  5122.6  415.36
  5128.8  417.69  5150.3  419.52  5155.4  417.98    5305  422.81  5655.2  439.43
#Mann= 7 ,-1 , 0
  4530.4     .08       0    4558     .05       0  4908.9     .12       0
  4992.7     .07       0  4998.7     .12       0  5011.7     .16       0
  5155.4     .05       0
Bank Sta=4968.4,5054.4
XS Rating Curve= 0 ,0
Exp/Cntr=0.3,0.1

Type RM Length L Ch R = 1 ,42527   ,578,578,578
BEGIN DESCRIPTION:
MIMS CREEK 51.0
END DESCRIPTION:
XS GIS Cut Line= 3
      3596049.59     10610610.15      3595849.61     10610160.19
      3595699.61     10609760.19
#Sta/Elev= 30
  4509.5  423.91  4564.2  420.48  4715.3  415.57  4865.8  414.56  4916.4  415.38
    4941  415.82  4947.2  413.59  4964.3  415.76  4969.8  413.81    4980  414.41
  4987.5  409.24    4993  402.19  4996.2  402.09  4998.9  401.59  5002.2  402.09
  5011.4   402.2  5023.3  403.84  5033.9  409.61    5042  412.54  5047.3  410.91
  5055.3  413.88  5072.2  415.43  5127.4  416.73  5212.8  423.63  5248.4  425.18
  5258.2  424.02  5273.4  424.63  5298.3  428.77  5322.3  431.03  5429.1  438.61
#Mann= 5 ,-1 , 0
  4509.5     .05       0  4916.4     .16       0  4996.2     .07       0
  5002.2     .16       0  5011.4     .05       0
Bank Sta=4980,5042
XS Rating Curve= 0 ,0
Exp/Cntr=0.3,0.1

Type RM Length L Ch R = 1 ,41949   ,430,430,430
BEGIN DESCRIPTION:
MIMS CREEK 50.0
END DESCRIPTION:
XS GIS Cut Line= 3
      3596449.62     10610410.21      3596199.61     10610060.19
      3595749.63      10609710.2
#Sta/Elev= 30
    4544  427.62  4551.4  425.95  4580.9  426.83  4611.4  423.49  4716.1  420.89
  4738.2  418.95  4744.3  419.91  4851.2  414.33  4910.2  413.59    4925  414.65
  4937.3  411.03  4945.9  412.98    4952  402.74  4960.6  405.07  4963.8  401.39
  4966.5  400.89  4969.8  401.39  4981.4  401.45  4987.7  404.28  4995.9  401.72
  5008.9  402.91  5016.7  402.88  5024.8  412.85  5034.1  414.37  5045.6   415.4
  5116.2  413.86  5215.7  413.84  5294.5  418.73  5430.2  433.38  5544.2  440.27
#Mann= 6 ,-1 , 0
    4544     .08       0  4611.4     .05       0  4963.8     .04       0
  4969.8     .05       0  5008.9     .16       0  5034.1     .05       0
Bank Sta=4945.9,5024.8
XS Rating Curve= 0 ,0
Exp/Cntr=0.3,0.1

Type RM Length L Ch R = 1 ,41519   ,238,238,238
BEGIN DESCRIPTION:
MIMS CREEK 49.0
END DESCRIPTION:
XS GIS Cut Line= 3
      3596579.79     10610074.56      3596193.49     10609675.23
      3595803.76     10609467.37
#Sta/Elev= 30
  4561.6  423.01  4607.3  422.25  4692.2  418.36  4823.9  414.53  4861.8  414.53
  4918.4  412.51  4946.6  412.97  4953.8  411.72    4968  409.36  4982.1  408.83
  4996.3  400.52  5000.2  400.48    5003  399.98  5006.2  400.48  5006.5  400.53
  5017.4  401.55  5024.4  408.65  5031.5  411.95  5081.2  413.77  5095.3  412.39
  5152.5  413.09  5204.4  412.78  5308.6  415.67  5314.3  417.25  5359.6  422.23
  5478.6  430.49  5484.3  432.02  5522.5  434.43  5538.8  437.32  5558.9  439.06
#Mann= 7 ,-1 , 0
  4561.6     .05       0  4823.9     .16       0  5000.2     .07       0
  5006.2     .16       0  5006.5     .05       0  5024.4     .08       0
  5152.5     .05       0
Bank Sta=4953.8,5031.5
XS Rating Curve= 0 ,0
Exp/Cntr=0.3,0.1

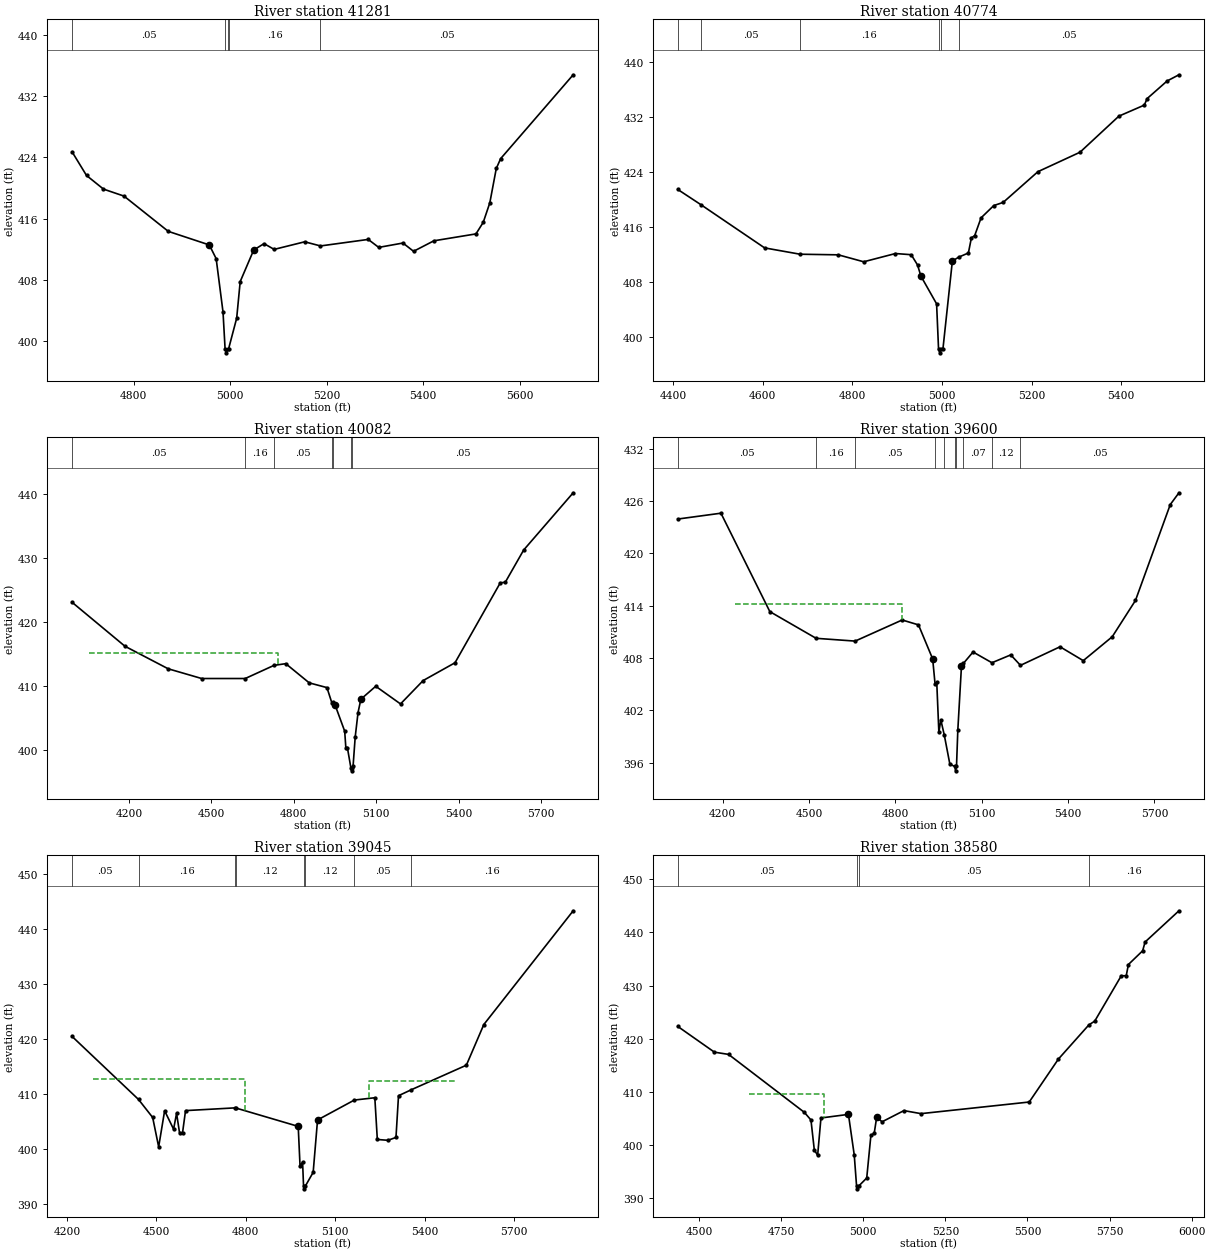
Type RM Length L Ch R = 1 ,41281   ,507,507,507
BEGIN DESCRIPTION:
Mapping XS 3afd36b4
END DESCRIPTION:
XS GIS Cut Line= 3
      3596744.73     10609957.37      3596414.84     10609649.18
      3595925.64     10609324.49
#Sta/Elev= 30
  4672.3  424.74  4702.3  421.65  4737.5  419.87    4780  418.96  4871.8  414.36
  4956.8  412.59    4971   410.8  4985.2  403.84  4989.5  399.02  4992.2  398.52
  4995.5  399.02  4996.7  399.03  5013.5  403.04  5020.8  407.81  5048.8  411.93
  5070.2  412.76  5091.2  412.01  5154.5     413  5187.2  412.46  5286.1  413.31
  5307.9  412.27  5358.1  412.84  5380.1  411.76  5422.2  413.13  5509.4  414.03
  5524.5  415.54  5538.1  418.08  5551.5  422.56  5560.5  423.84  5710.9  434.78
#Mann= 5 ,-1 , 0
  4672.3     .05       0  4989.5     .07       0  4995.5     .05       0
  4996.7     .16       0  5187.2     .05       0
Bank Sta=4956.8,5048.8
XS Rating Curve= 0 ,0
Exp/Cntr=0.3,0.1

Type RM Length L Ch R = 1 ,40774   ,692,692,692
BEGIN DESCRIPTION:
MIMS CREEK 48.0
END DESCRIPTION:
XS GIS Cut Line= 4
      3596775.09     10609831.49      3596718.66     10609492.93
      3596362.76     10609167.41      3596119.68     10609002.47
#Sta/Elev= 30
    4410  421.48    4462  419.25  4603.9  412.98  4683.1  412.06  4768.5  411.97
  4825.2  410.96  4896.1  412.16  4931.3  411.99  4945.5  410.49  4952.9  408.88
    4988  404.84  4992.4  398.21  4995.2  397.71  4998.4  398.21  5002.2   398.3
  5023.2  411.06  5037.2  411.63    5059  412.24  5065.7  414.44  5073.1  414.77
  5087.3  417.35  5115.7  419.14  5136.7   419.6  5214.3  424.07  5308.3   426.9
  5395.1  432.15    5452  433.76  5458.1   434.7  5502.9  437.27  5529.3  438.17
#Mann= 6 ,-1 , 0
    4410     .08       0    4462     .05       0  4683.1     .16       0
  4992.4     .07       0  4998.4     .16       0  5037.2     .05       0
Bank Sta=4952.9,5023.2
XS Rating Curve= 0 ,0
Exp/Cntr=0.3,0.1

Type RM Length L Ch R = 1 ,40082   ,482,482,482
BEGIN DESCRIPTION:
MIMS CREEK 47.0
END DESCRIPTION:
XS GIS Cut Line= 3
      3597549.62     10609660.21      3596949.61     10608860.19
      3596149.65      10608660.2
#Sta/Elev= 30
  3992.4  423.13  4185.1  416.26  4342.4  412.74  4464.3  411.22    4623  411.22
  4727.5  413.27  4770.5  413.54    4856  410.54  4920.5   409.8    4938  407.46
  4941.6  407.53  4949.7  407.13  4985.1  402.99  4989.3  400.39    4995  400.39
  5007.5   397.3  5010.2   396.8  5013.5   397.3  5015.6  397.52  5023.3  402.07
  5033.7  405.91    5044  407.99  5098.1  410.01  5188.3  407.25  5270.7   410.9
  5386.7  413.68  5551.6  426.17  5569.7  426.25  5636.7  431.29    5817  440.23
#Mann= 7 ,-1 , 0
  3992.4     .05       0    4623     .16       0  4727.5     .05       0
    4938     .16       0  4941.6     .05       0  5007.5     .03       0
  5013.5     .05       0
#XS Ineff= 1 ,-1
 4053.98  4742.4  415.16
Permanent Ineff=
       F
Bank Sta=4949.7,5044
XS Rating Curve= 0 ,0
Exp/Cntr=0.3,0.1

Type RM Length L Ch R = 1 ,39600   ,555,555,555
BEGIN DESCRIPTION:
MIMS CREEK 46.0
END DESCRIPTION:
XS GIS Cut Line= 3
      3597927.48     10609254.45      3597249.61     10608610.19
      3596449.63     10608510.19
#Sta/Elev= 30
  4043.8  423.93  4193.7   424.6  4363.6  413.32  4524.3  410.26    4660  409.94
  4823.5  412.36  4880.1   411.8  4929.4   407.9  4937.6  405.06  4943.6   405.2
  4950.9  399.51  4957.8   400.9  4969.8  399.17  4989.1  395.84  5006.2  395.57
    5009  395.07  5012.2  395.57  5016.8  399.74  5029.4  407.04  5036.1  407.38
  5069.7  408.69  5135.3  407.46  5200.7  408.36  5234.5  407.16    5372  409.29
  5452.7   407.7  5553.4  410.44  5634.1   414.6    5755  425.59  5785.2  426.94
#Mann= 10 ,-1 , 0
  4043.8     .05       0  4524.3     .16       0    4660     .05       0
  4937.6     .16       0  4969.8     .12       0  5006.2     .07       0
  5012.2     .12       0  5036.1     .07       0  5135.3     .12       0
  5234.5     .05       0
#XS Ineff= 1 ,-1
 4242.39  4823.5  414.19
Permanent Ineff=
       F
Bank Sta=4929.4,5029.4
XS Rating Curve= 0 ,0
Exp/Cntr=0.3,0.1

Type RM Length L Ch R = 1 ,39045   ,465,465,465
BEGIN DESCRIPTION:
MIMS CREEK 45.0
END DESCRIPTION:
XS GIS Cut Line= 3
      3597849.66     10608360.19      3597099.61     10608310.19
      3596549.59     10607560.16
#Sta/Elev= 30
  4216.7   420.5  4439.8  409.03  4487.3  405.75  4507.4  400.41  4527.4  406.97
  4557.5  403.62  4567.5  406.51  4577.5  402.95  4587.6  402.99  4597.6     407
  4764.2   407.5  4765.3  407.49  4975.7  404.13  4981.9  396.88  4990.4  397.66
  4993.6  393.27  4996.3  392.77  4999.6  393.27  5025.9  395.77  5040.6   405.3
  5164.1  408.92  5232.8  409.34  5241.2  401.75  5276.7   401.6  5303.8  402.12
  5312.3  409.71  5355.8  410.81    5540  415.26  5598.6  422.66  5898.5  443.35
#Mann= 8 ,-1 , 0
  4216.7     .05       0  4439.8     .16       0  4764.2     .05       0
  4765.3     .12       0  4993.6     .07       0  4999.6     .12       0
  5164.1     .05       0  5355.8     .16       0
#XS Ineff= 2 ,-1
 4285.91    4798  412.75  5211.9 5507.05  412.38
Permanent Ineff=
       F       F
Bank Sta=4975.7,5040.6
XS Rating Curve= 0 ,0
Exp/Cntr=0.3,0.1

Type RM Length L Ch R = 1 ,38580   ,408,408,408
BEGIN DESCRIPTION:
MIMS CREEK 44.0
END DESCRIPTION:
XS GIS Cut Line= 3
       3597949.6     10608060.19      3597349.61     10607960.19
      3596549.65     10607510.21
#Sta/Elev= 30
  4435.3  422.28  4546.8  417.43  4589.9  417.01  4820.5  406.09  4840.8  404.64
  4850.9  399.03  4861.1  397.97  4871.2  405.02  4954.9   405.7  4972.6  398.05
  4979.7  392.16  4982.5  391.66  4985.7  392.16  5010.6   393.7  5023.3  401.75
  5033.4  402.13    5041  405.19  5057.3   404.3  5123.9  406.41  5175.8  405.84
  5505.4  408.03  5594.3  416.13  5687.2  422.58  5704.9  423.28  5785.8  431.84
  5800.8  431.84  5807.5  433.96  5850.9  436.55  5858.2   438.2  5961.4  444.09
#Mann= 4 ,-1 , 0
  4435.3     .05       0  4979.7     .03       0  4985.7     .05       0
  5687.2     .16       0
#XS Ineff= 1 ,-1
 4651.82  4881.4  409.45
Permanent Ineff=
       F
Bank Sta=4954.9,5041
XS Rating Curve= 0 ,0
Exp/Cntr=0.3,0.1