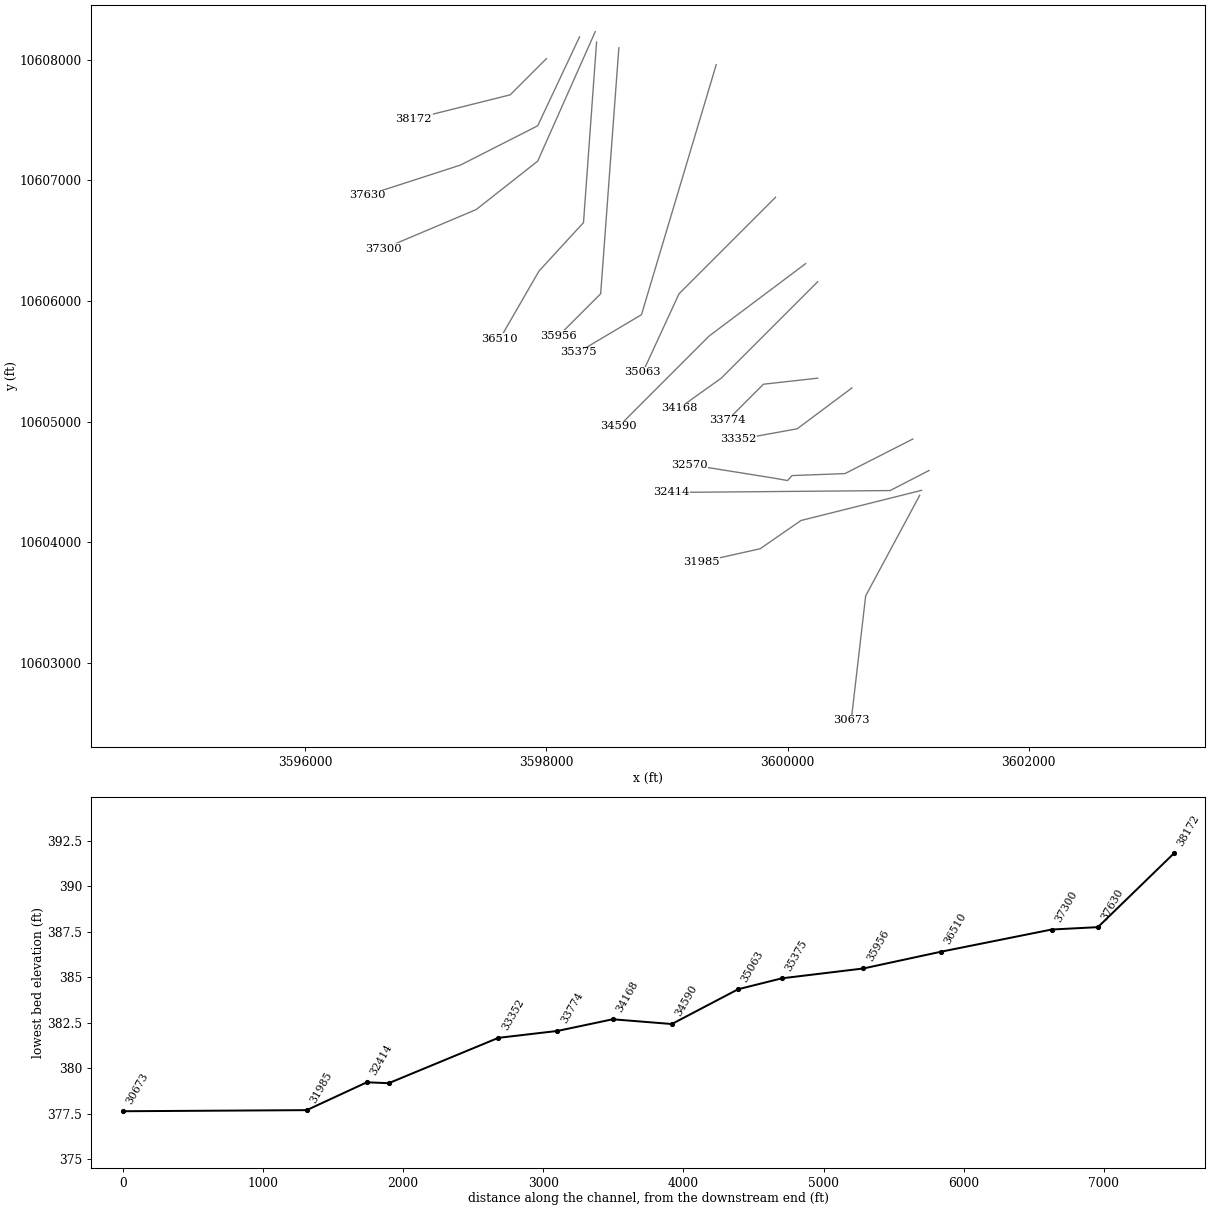
HEC-RAS study MIMS CREEK.prj: MIMS CREEK Base Level Engineering

--- MIMS CREEK.g01 (geometry) --- (continued)

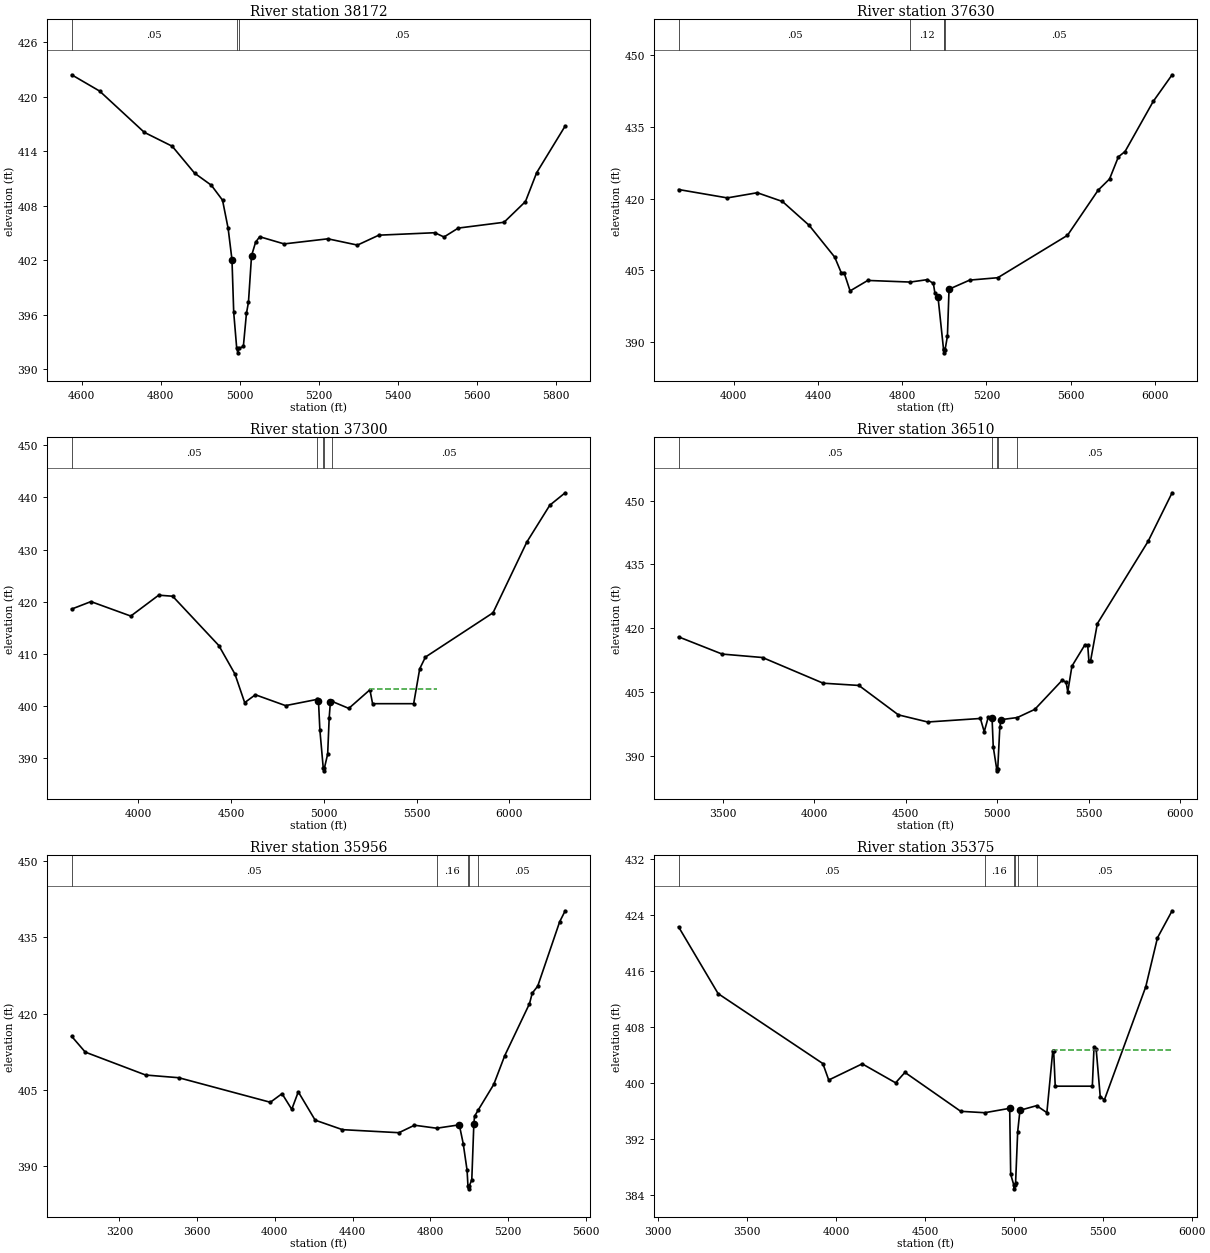
Type RM Length L Ch R = 1 ,38172   ,542,542,542
BEGIN DESCRIPTION:
MIMS CREEK 43.0
END DESCRIPTION:
XS GIS Cut Line= 3
      3597999.59     10608010.17      3597699.61     10607710.19
      3596899.57     10607510.18
#Sta/Elev= 30
  4574.3  422.39    4645   420.6  4758.1  416.06  4828.8  414.53  4885.4  411.57
  4927.8  410.24  4956.1   408.6  4970.3  405.49    4980  402.05  4984.4  396.25
    4992  392.31  4994.8  391.81    4998  392.31  5008.8  392.51  5016.6  396.15
  5021.7  397.37  5029.5  402.49  5039.8  403.98  5050.1  404.58  5111.9  403.79
  5222.7  404.35  5297.5  403.66  5351.6  404.75  5493.3  405.02  5516.5  404.55
  5552.6  405.53  5668.5  406.17  5722.7  408.45    5751  411.62  5823.2  416.76
#Mann= 3 ,-1 , 0
  4574.3     .05       0    4992     .03       0    4998     .05       0
Bank Sta=4980,5029.5
XS Rating Curve= 0 ,0
Exp/Cntr=0.3,0.1

Type RM Length L Ch R = 1 ,37630   ,330,330,330
BEGIN DESCRIPTION:
MIMS CREEK 42.0
END DESCRIPTION:
XS GIS Cut Line= 4
       3598274.7     10608191.06       3597927.5     10607453.25
      3597287.31     10607127.73      3596516.94     10606878.17
#Sta/Elev= 30
  3738.7  421.89    3970  420.14  4112.3  421.22  4231.8  419.39  4358.6  414.41
  4480.1  407.76  4510.9  404.52  4524.4  404.54  4553.1   400.7    4637  402.89
  4838.7  402.55  4920.6  403.06  4948.5  402.26  4955.6  400.31  4970.7  399.34
  4996.8  388.48  4997.5  388.26  5000.2  387.76  5003.5  388.26  5015.2  391.24
  5022.9  401.06  5120.9  402.96  5254.4  403.46  5585.3  412.32    5731  421.76
    5785  424.09    5827  428.72  5858.6  429.83  5992.2  440.29  6082.1  445.87
#Mann= 5 ,-1 , 0
  3738.7     .05       0  4838.7     .12       0  4996.8     .05       0
  4997.5     .03       0  5003.5     .05       0
Bank Sta=4970.7,5022.9
XS Rating Curve= 0 ,0
Exp/Cntr=0.3,0.1

Type RM Length L Ch R = 1 ,37300   ,790,790,790
BEGIN DESCRIPTION:
MIMS CREEK 41.0
END DESCRIPTION:
XS GIS Cut Line= 4
      3598404.94     10608234.51       3597927.5     10607160.28
      3597417.52      10606758.8      3596647.16      10606433.3
#Sta/Elev= 30
  3640.5  418.61  3744.5  420.04  3959.3  417.27  4109.7  421.27    4185  421.07
  4433.9  411.63  4520.7  406.18  4573.4  400.69  4630.9   402.2  4793.7  400.12
  4963.4  401.31  4971.1  401.09  4978.8  395.46    4997  388.13  4999.8  387.63
    5003  388.13  5020.8  390.85  5028.9  397.72  5035.3  400.75  5042.4  400.96
  5134.7  399.59  5248.5  403.15    5263  400.49  5484.5  400.49  5517.1  407.18
  5547.9  409.42  5912.3   417.9  6094.5  431.44  6218.4   438.5  6301.4  440.88
#Mann= 5 ,-1 , 0
  3640.5     .05       0  4963.4     .12       0    4997     .07       0
    5003     .12       0  5042.4     .05       0
#XS Ineff= 1 ,-1
 5248.86 5608.52   403.3
Permanent Ineff=
       T
Bank Sta=4971.1,5035.3
XS Rating Curve= 0 ,0
Exp/Cntr=0.3,0.1

Type RM Length L Ch R = 1 ,36510   ,554,554,554
BEGIN DESCRIPTION:
MIMS CREEK 40.0
END DESCRIPTION:
XS GIS Cut Line= 4
      3598415.78     10608147.68      3598307.27      10606650.3
      3597938.35     10606248.82       3597613.9     10605686.45
#Sta/Elev= 30
  3258.9  417.93    3497  413.88  3717.6  413.07  4048.5  407.03  4243.8   406.5
  4459.5  399.58  4619.9   397.9  4907.4  398.73  4928.4  395.61    4950  398.97
  4971.3  398.73  4977.7  392.06  4996.3  386.91  4999.1  386.41  5002.3  386.91
  5013.5  396.64  5020.3  398.45  5109.4  398.95  5204.6  400.87  5354.4  407.73
  5375.9  407.23  5384.7  404.99  5407.5  411.04  5477.9  416.03  5493.7  415.95
  5500.1  412.26  5509.5  412.33  5546.3  421.04  5823.4  440.39  5954.7  451.83
#Mann= 5 ,-1 , 0
  3258.9     .05       0  4971.3     .12       0  4996.3     .07       0
  5002.3     .12       0  5109.4     .05       0
Bank Sta=4971.3,5020.3
XS Rating Curve= 0 ,0
Exp/Cntr=0.3,0.1

Type RM Length L Ch R = 1 ,35956   ,581,581,581
BEGIN DESCRIPTION:
MIMS CREEK 39.0
END DESCRIPTION:
XS GIS Cut Line= 3
       3598600.6     10608100.14      3598449.61     10606060.19
      3598099.61     10605710.19
#Sta/Elev= 30
  2954.2  415.51  3024.3   412.4  3335.2  407.89  3505.7  407.36  3976.9  402.53
  4037.1  404.22  4087.2  401.14  4120.8  404.58  4207.6  399.01    4348  397.14
  4638.7  396.54    4719  398.01  4833.3  397.42  4949.6  398.09  4969.7  394.41
  4989.7  389.13  4994.2  385.99    4997  385.49  5000.2  385.99  5013.9  387.25
 5024.43  398.22    5028  399.76  5046.8  400.99    5127  406.04  5183.6  411.71
  5310.9  421.93    5325     424  5353.3  425.39  5466.4  438.07  5494.7  440.22
#Mann= 5 ,-1 , 0
  2954.2     .05       0  4833.3     .16       0  4994.2     .07       0
  5000.2     .16       0  5046.8     .05       0
Bank Sta=4949.6,5024.43
XS Rating Curve= 0 ,0
Exp/Cntr=0.3,0.1

Type RM Length L Ch R = 1 ,35375   ,312,312,312
BEGIN DESCRIPTION:
MIMS CREEK 38.0
END DESCRIPTION:
XS GIS Cut Line= 3
      3599407.89     10607959.51       3598788.1      10605886.6
       3598262.1     10605574.12
#Sta/Elev= 30
  3114.7  422.36    3337  412.83    3926  402.84  3959.1  400.49  4147.3   402.8
  4335.2  400.09  4387.7  401.58  4701.4  396.02  4836.9  395.82  4976.7  396.45
  4982.3  387.04  5000.2  385.45  5002.9  384.95  5006.2  385.45  5009.8  385.73
  5021.6  393.09  5034.5  396.17  5128.4  396.83  5185.8  395.83  5218.9  404.62
  5224.1  404.63  5232.8  399.61  5441.4  399.61    5451   405.2  5462.9  404.94
  5485.9  398.12  5509.2  397.65  5741.8   413.8  5807.7   420.8  5890.1  424.66
#Mann= 6 ,-1 , 0
  3114.7     .05       0  4836.9     .16       0  5000.2     .07       0
  5006.2     .16       0  5021.6     .16       0  5128.4     .05       0
#XS Ineff= 2 , 0
       0                 5219.32       0  404.84
Permanent Ineff=
       F       T
Bank Sta=4976.7,5034.5
XS Rating Curve= 0 ,0
Exp/Cntr=0.3,0.1

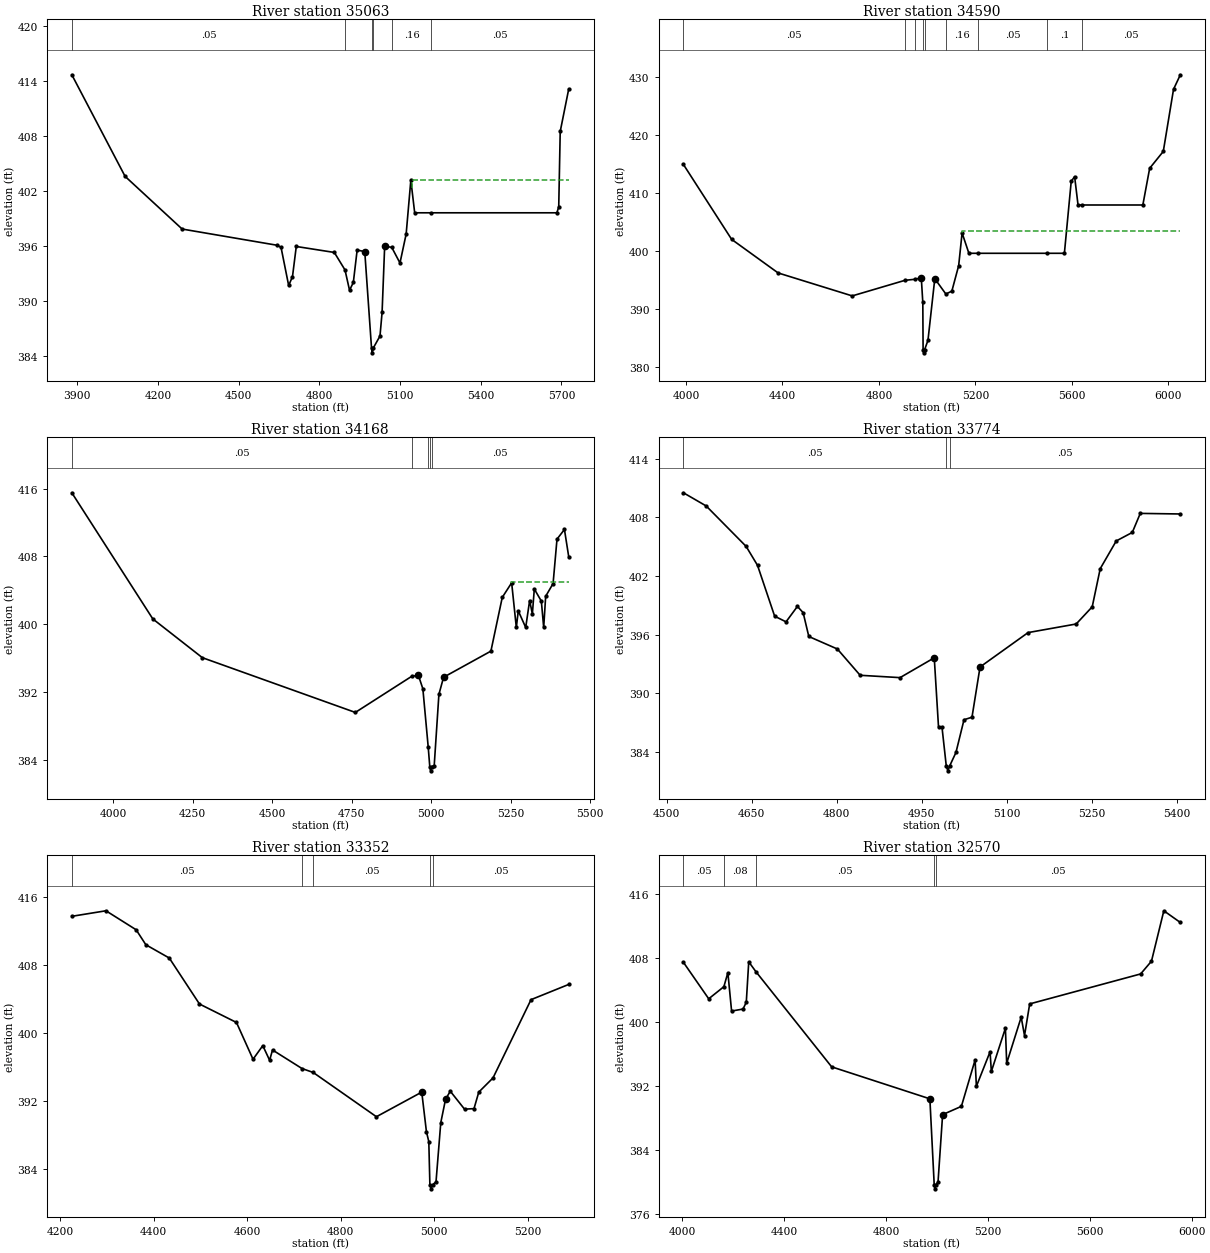
Type RM Length L Ch R = 1 ,35063   ,473,473,473
BEGIN DESCRIPTION:
MIMS CREEK 37.0
END DESCRIPTION:
XS GIS Cut Line= 3
      3599899.62      10606860.2      3599099.61     10606060.19
       3598799.6     10605410.16
#Sta/Elev= 30
  3879.8  414.65  4077.8  403.58  4289.9  397.84  4643.5  396.07  4657.6  395.84
  4685.9  391.69  4700.1  392.65  4714.2  395.94  4855.6  395.29  4895.4  393.38
  4912.2  391.17  4926.3  392.02  4940.5  395.55  4968.8  395.38    4994  384.85
  4996.8  384.35    5000  384.85  5025.4  386.18  5033.2  388.75  5042.8  395.98
  5069.2  395.84  5099.7  394.14  5122.7   397.3  5140.1  403.17  5154.4  399.61
  5215.9  399.61    5683  399.61  5689.9  400.26  5695.4  408.47  5727.1  413.11
#Mann= 6 ,-1 , 0
  3879.8     .05       0  4895.4     .12       0    4994     .07       0
    5000     .12       0  5069.2     .16       0  5215.9     .05       0
#XS Ineff= 2 , 0
       0                 5143.47       0  403.17
Permanent Ineff=
       F       T
Bank Sta=4968.8,5042.8
XS Rating Curve= 0 ,0
Exp/Cntr=0.3,0.1

Type RM Length L Ch R = 1 ,34590   ,422,422,422
BEGIN DESCRIPTION:
MIMS CREEK 36.0
END DESCRIPTION:
XS GIS Cut Line= 3
       3600149.6     10606310.18      3599349.61     10605710.19
      3598599.64     10604960.22
#Sta/Elev= 30
  3989.3  414.93  4189.3  402.01    4382  396.22  4689.3  392.26  4908.2  394.95
  4947.9  395.12  4975.7  395.38    4982  391.13  4983.2  382.94  4985.9  382.44
  4989.2  382.94  5003.4  384.61  5031.7  395.23  5077.5  392.59  5102.4  393.08
  5130.7  397.48  5144.9  403.12  5173.1  399.61  5212.1  399.61  5498.8  399.61
  5569.1  399.61  5597.4  412.01  5611.5  412.84  5625.7  407.94  5643.2  407.94
  5894.4  407.94  5922.7  414.27  5979.2  417.18  6021.7   427.9  6049.9   430.4
#Mann= 9 ,-1 , 0
  3989.3     .05       0  4908.2     .16       0  4947.9     .12       0
  4983.2     .07       0  4989.2     .12       0  5077.5     .16       0
  5212.1     .05       0  5498.8      .1       0  5643.2     .05       0
#XS Ineff= 2 , 0
       0                 5144.89       0   403.5
Permanent Ineff=
       F       T
Bank Sta=4975.7,5031.7
XS Rating Curve= 0 ,0
Exp/Cntr=0.3,0.1

Type RM Length L Ch R = 1 ,34168   ,394,394,394
BEGIN DESCRIPTION:
MIMS CREEK 35.0
END DESCRIPTION:
XS GIS Cut Line= 3
       3600249.6     10606160.18      3599449.61     10605360.19
      3599099.59     10605110.17
#Sta/Elev= 30
  3870.7   415.5  4125.2  400.62  4280.8  396.05  4761.6  389.59  4938.4  393.84
  4959.6  393.98  4973.8  392.38  4990.6  385.51  4995.5   383.2  4998.3   382.7
  5001.5   383.2  5009.4  383.28  5024.2  391.72  5038.9  393.74  5187.6  396.82
  5223.3  403.16  5252.8  404.88  5267.5  399.61  5273.6  401.57    5297  399.61
  5309.3  402.79  5317.9  401.21    5324  404.15  5346.1  402.72  5353.5  399.61
  5359.7  403.29    5383  404.79  5395.3  410.03  5418.7  411.17  5432.2  407.94
#Mann= 5 ,-1 , 0
  3870.7     .05       0  4938.4     .12       0  4990.6     .05       0
  4995.5    .035       0  5001.5     .05       0
#XS Ineff= 2 , 0
       0                 5252.27       0  404.93
Permanent Ineff=
       F       T
Bank Sta=4959.6,5038.9
XS Rating Curve= 0 ,0
Exp/Cntr=0.3,0.1

Type RM Length L Ch R = 1 ,33774   ,422,422,422
BEGIN DESCRIPTION:
MIMS CREEK 34.0
END DESCRIPTION:
XS GIS Cut Line= 3
       3600249.6     10605360.19      3599799.61     10605310.19
      3599499.63     10605010.21
#Sta/Elev= 30
  4529.3  410.52  4569.5  409.17    4640  405.03  4660.1  403.09  4690.3  397.89
  4710.4  397.31  4730.5  398.89  4740.6  398.25  4750.6  395.81    4801  394.53
  4841.2  391.84  4911.6   391.6    4972  393.63  4979.5  386.56  4985.6  386.56
  4993.2  382.56    4996  382.06  4999.2  382.56  5010.3  383.94  5024.5  387.29
  5038.6  387.55  5052.8  392.69  5137.6  396.21  5222.5  397.09  5250.8  398.85
  5264.9  402.75  5293.2  405.59  5321.5  406.46  5335.6  408.41  5406.3  408.35
#Mann= 3 ,-1 , 0
  4529.3     .05       0  4993.2     .03       0  4999.2     .05       0
Bank Sta=4972,5052.8
XS Rating Curve= 0 ,0
Exp/Cntr=0.3,0.1

Type RM Length L Ch R = 1 ,33352   ,782,782,782
BEGIN DESCRIPTION:
Mapping XS 1d832237
END DESCRIPTION:
XS GIS Cut Line= 3
      3600532.93     10605278.98      3600079.77     10604940.42
      3599590.18     10604851.87
#Sta/Elev= 30
  4224.9  413.69  4297.9  414.34  4362.5  412.11  4383.3  410.35  4433.4  408.79
    4498  403.39  4577.2  401.22  4612.6   396.9  4633.5   398.5  4648.1  396.78
  4654.3  397.99  4717.4  395.81  4741.3  395.35  4876.6  390.15  4973.6  393.04
  4983.6   388.4  4988.7  387.22    4991  382.18  4993.7  381.68    4997  382.18
  5004.1  382.49  5014.3  389.45  5024.5  392.19  5034.6  393.15  5065.1  391.04
  5085.4   391.1  5095.6  393.04  5126.1  394.71  5207.4   403.9  5288.1  405.69
#Mann= 5 ,-1 , 0
  4224.9     .05       0  4717.4      .1       0  4741.3     .05       0
    4991     .03       0    4997     .05       0
Bank Sta=4973.6,5024.5
XS Rating Curve= 0 ,0
Exp/Cntr=0.3,0.1

Type RM Length L Ch R = 1 ,32570   ,156,156,156
BEGIN DESCRIPTION:
MIMS CREEK 33.0
END DESCRIPTION:
XS GIS Cut Line= 6
      3601038.12     10604855.36       3600475.6     10604568.89
      3600036.37      10604552.4      3599999.48     10604511.16
      3599890.97      10604530.7      3599185.62     10604643.55
#Sta/Elev= 30
    4005  407.45  4104.3   402.9  4163.8  404.41  4179.5  406.16  4194.1  401.37
    4239  401.62  4251.8  402.47  4261.4  407.51  4289.4  406.29  4586.9  394.41
  4972.5  390.42  4989.5  379.69  4992.3  379.19  4995.5  379.69  5004.5  380.04
  5022.5  388.45  5096.2  389.48    5150  395.27  5155.1  391.98  5208.8  396.29
  5213.8  393.83    5269  399.23    5274  394.86    5331  400.61    5344  398.31
  5364.3  402.26  5799.8     406  5842.4  407.59  5890.9  413.88  5955.7  412.42
#Mann= 5 ,-1 , 0
    4005     .05       0  4163.8     .08       0  4289.4     .05       0
  4989.5     .03       0  4995.5     .05       0
Bank Sta=4972.5,5022.5
XS Rating Curve= 0 ,0
Exp/Cntr=0.3,0.1

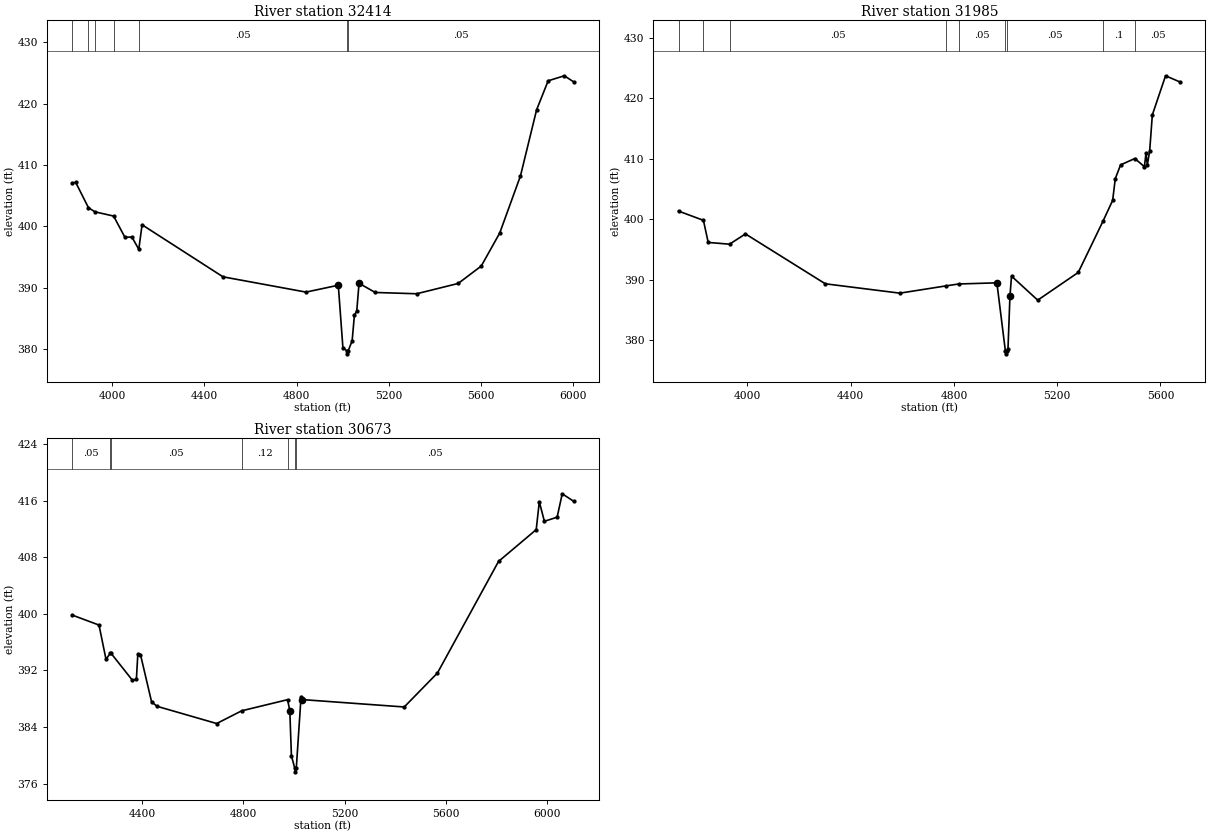
Type RM Length L Ch R = 1 ,32414   ,429,429,429
BEGIN DESCRIPTION:
MIMS CREEK 32.0
END DESCRIPTION:
XS GIS Cut Line= 3
      3601173.49     10604594.91       3600850.6     10604428.26
      3599038.12     10604412.64
#Sta/Elev= 30
  3826.4  407.05    3842  407.19  3897.5  403.05  3925.8  402.38  4006.6  401.69
  4055.8  398.21  4085.7  398.29  4115.7  396.27    4130  400.27  4480.8  391.79
  4840.8   389.3  4980.8  390.42  5000.8  380.25  5017.8  379.74  5020.5  379.24
  5023.8  379.74  5040.8  381.35  5050.8  385.57  5060.8  386.18  5070.8  390.74
  5140.8  389.24  5320.8  389.03  5500.8  390.71  5600.8  393.55  5680.8  398.92
  5770.8  408.24  5840.8  419.01  5890.8  423.73  5960.8  424.55  6002.3  423.54
#Mann= 7 ,-1 , 0
  3826.4     .05       0  3897.5     .16       0  3925.8     .05       0
  4006.6     .08       0  4115.7     .05       0  5017.8     .03       0
  5023.8     .05       0
Bank Sta=4980.8,5070.8
XS Rating Curve= 0 ,0
Exp/Cntr=0.3,0.1

Type RM Length L Ch R = 1 ,31985   ,1312,1312,1312
BEGIN DESCRIPTION:
MIMS CREEK 31.0
END DESCRIPTION:
XS GIS Cut Line= 4
      3601111.05     10604430.01      3600111.02       10604180.
      3599772.48     10603945.63      3599283.79     10603836.45
#Sta/Elev= 30
  3733.5  401.35  3829.9  399.82  3848.4  396.16  3930.9  395.87  3992.7  397.57
  4301.9  389.31  4590.5  387.76  4770.2  388.97  4818.7  389.28  4966.4  389.47
  4999.2  378.21  5001.9  377.71  5005.2  378.21  5009.3  378.46    5017  387.29
  5023.1  390.58  5124.5   386.6  5281.5  391.19  5377.2  399.67  5414.7  403.12
  5424.9  406.72  5445.4     409  5500.7  410.06  5537.6   408.7  5543.9  410.94
    5549  408.99  5558.1  411.32  5568.4  417.28  5619.6  423.76  5676.8  422.71
#Mann= 9 ,-1 , 0
  3733.5     .05       0  3829.9     .08       0  3930.9     .05       0
  4770.2     .12       0  4818.7     .05       0  4999.2     .03       0
  5005.2     .05       0  5377.2      .1       0  5500.7     .05       0
Bank Sta=4966.4,5017
XS Rating Curve= 0 ,0
Exp/Cntr=0.3,0.1

Type RM Length L Ch R = 1 ,30673   ,459,459,459
BEGIN DESCRIPTION:
Mapping XS d8b2d696
END DESCRIPTION:
XS GIS Cut Line= 3
      3601095.39     10604388.32      3600647.48       10603555.
      3600527.77      10602524.5
#Sta/Elev= 30
  4122.5  399.82    4229   398.4  4256.6  393.56  4274.4  394.46  4276.5  394.41
  4360.5  390.62  4376.7  390.71  4382.4  394.27  4392.9  394.23  4436.8  387.54
  4458.7  386.91  4694.1  384.48  4793.1  386.28  4974.2  387.85  4983.2  386.31
  4989.5  379.94  5002.8  378.15  5005.5  377.65  5008.8  378.15  5027.7   388.3
  5033.3  387.86  5435.5  386.82  5566.7  391.62  5808.3   407.4  5957.2  411.89
  5969.4  415.83  5989.5  413.07  6039.9  413.65    6060  416.96    6106  415.88
#Mann= 7 ,-1 , 0
  4122.5     .05       0  4274.4     .08       0  4276.5     .05       0
  4793.1     .12       0  4974.2     .05       0  5002.8     .03       0
  5008.8     .05       0
Bank Sta=4983.2,5033.3
XS Rating Curve= 0 ,0
Exp/Cntr=0.3,0.1