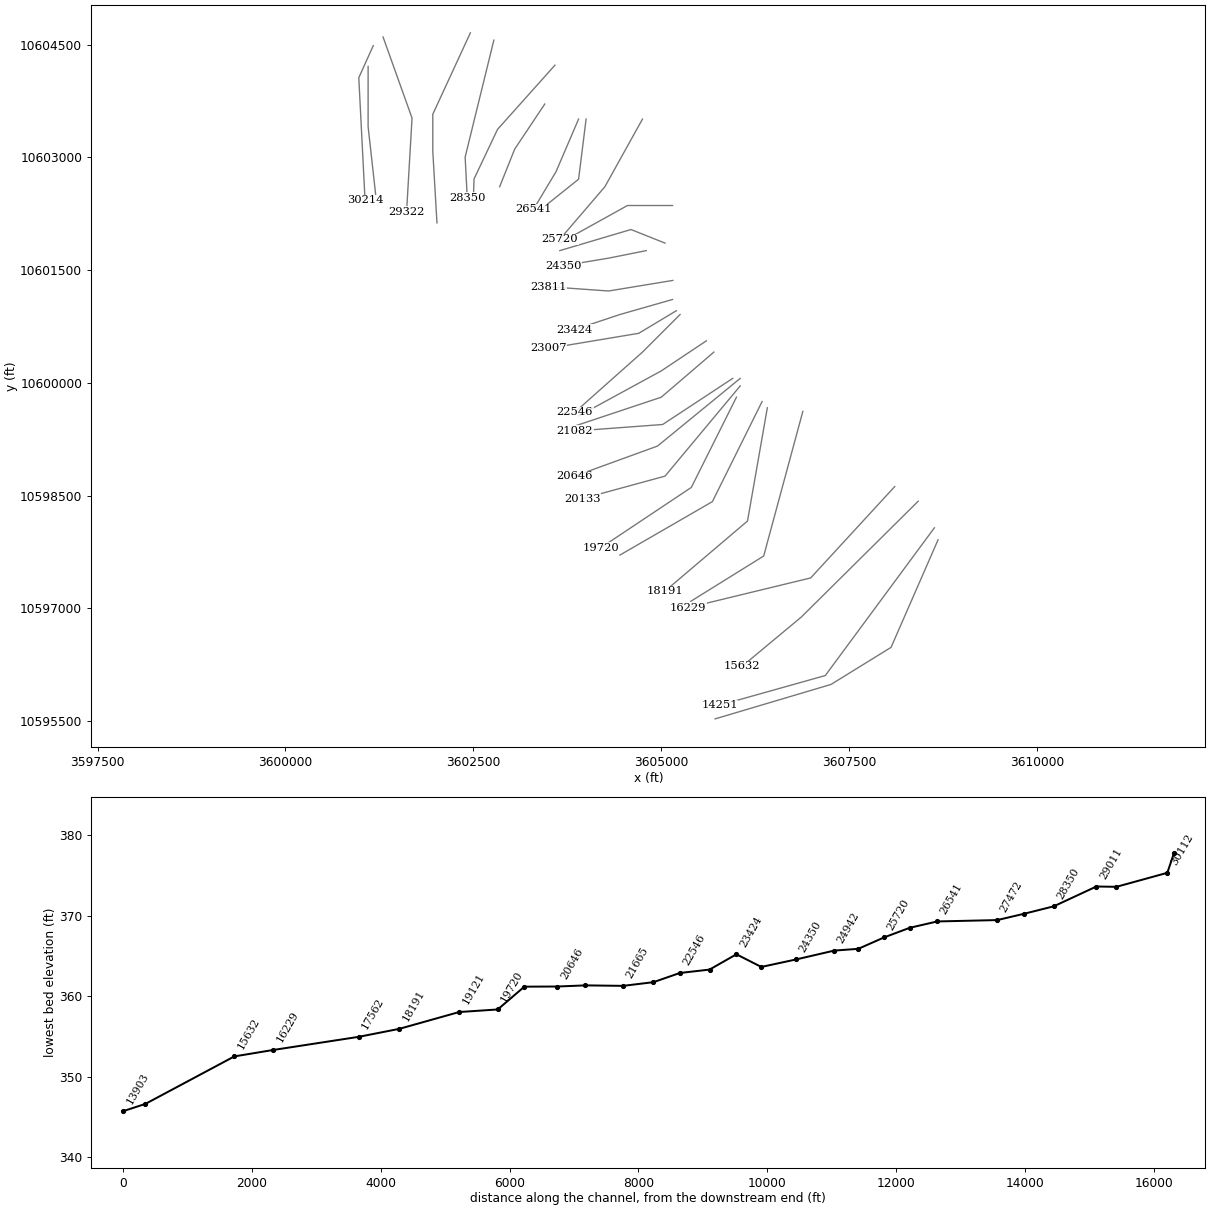
HEC-RAS study MIMS CREEK.prj: MIMS CREEK Base Level Engineering

--- MIMS CREEK.g01 (geometry) --- (continued)

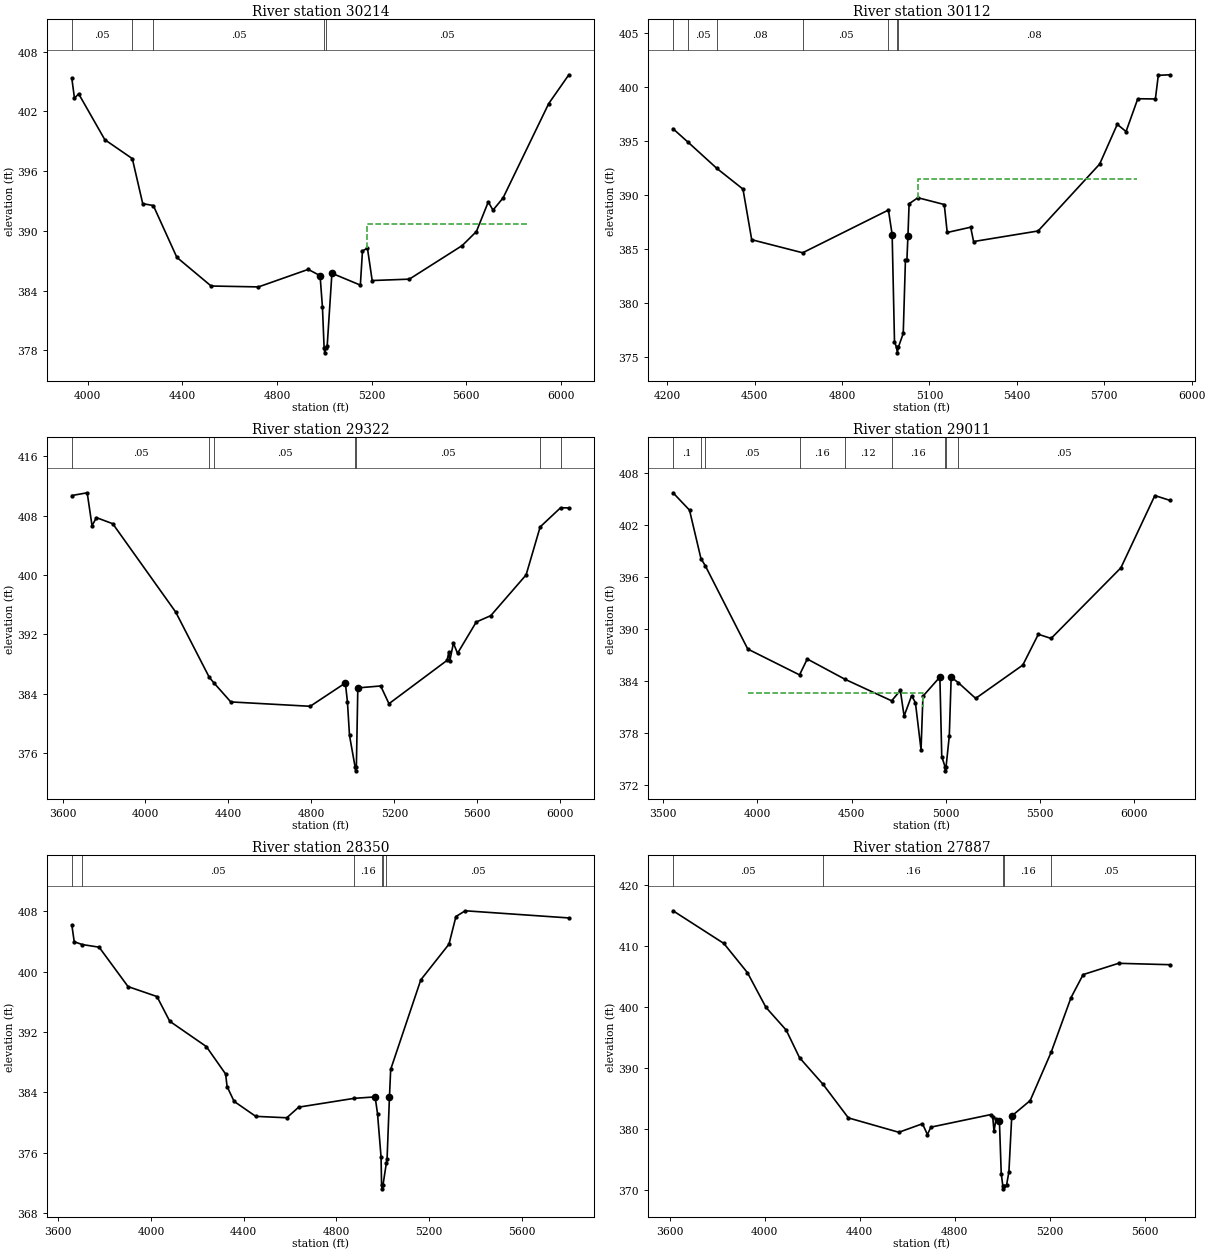
Type RM Length L Ch R = 1 ,30214   ,102,102,102
BEGIN DESCRIPTION:
Mapping XS da23aaf5
END DESCRIPTION:
XS GIS Cut Line= 3
      3601168.33     10604487.32       3600975.6     10604060.21
      3601058.94     10602430.02
#Sta/Elev= 30
  3932.7  405.32  3943.9  403.32  3961.5  403.77  4072.2  399.16  4188.4  397.26
  4232.4  392.74  4277.2  392.55  4376.6  387.35  4521.5  384.47  4721.7  384.38
    4932  386.14  4982.1  385.51  4992.1  382.34  4999.1  378.26  5001.8  377.76
  5005.1  378.26  5012.1  378.45  5032.1  385.75  5152.3  384.56  5161.3  387.99
  5182.3  388.27  5202.3  385.02  5359.4  385.16  5582.8  388.53  5642.9  389.94
    5693  392.91    5713  392.09  5755.5  393.31  5948.6  402.79  6033.6  405.68
#Mann= 5 ,-1 , 0
  3932.7     .05       0  4188.4     .08       0  4277.2     .05       0
  4999.1     .03       0  5005.1     .05       0
#XS Ineff= 1 ,-1
  5182.3  5862.5  390.73
Permanent Ineff=
       F
Bank Sta=4982.1,5032.1
XS Rating Curve= 0 ,0
Exp/Cntr=0.3,0.1

Type RM Length L Ch R = 1 ,30112   ,790,790,790
BEGIN DESCRIPTION:
MIMS CREEK 30.0
END DESCRIPTION:
XS GIS Cut Line= 3
      3601099.61     10604210.22      3601099.61     10603410.19
      3601199.61     10602510.16
#Sta/Elev= 30
  4220.2  396.11  4272.8  394.84  4370.9  392.43  4460.2  390.52  4490.2  385.83
  4665.1  384.62  4959.4  388.58 4972.16   386.3  4980.2  376.39  4987.2  375.85
    4990  375.35  4993.2  375.85  5010.2  377.15  5017.7  383.91  5022.7  383.91
 5026.36  386.19  5030.3  389.16  5060.5  389.72    5151  389.09  5161.1   386.5
  5241.6  386.99  5251.6  385.66    5473  386.64  5684.3  392.84  5744.7  396.52
  5774.8  395.85  5815.1  398.89  5875.5  398.87  5885.5  401.06  5925.8  401.11
#Mann= 7 ,-1 , 0
  4220.2     .08       0  4272.8     .05       0  4370.9     .08       0
  4665.1     .05       0  4959.4     .08       0  4987.2     .07       0
  4993.2     .08       0
#XS Ineff= 1 ,-1
  5060.5 5812.84  391.45
Permanent Ineff=
       F
Bank Sta=4972.16,5026.36
XS Rating Curve= 0 ,0
Exp/Cntr=0.3,0.1

Type RM Length L Ch R = 1 ,29322   ,311,311,311
BEGIN DESCRIPTION:
MIMS CREEK 29.0
END DESCRIPTION:
XS GIS Cut Line= 3
      3601298.53     10604601.86      3601683.94     10603523.75
      3601611.06      10602274.5
#Sta/Elev= 30
  3644.9  410.72    3719  411.09  3742.3  406.65  3763.5  407.74  3842.2  406.92
  4145.8  395.01  4307.5  386.22    4332   385.4  4411.3   382.9  4794.1  382.31
  4963.7  385.45  4973.7  382.91  4983.7  378.38  5010.8  374.11  5013.5  373.61
  5016.8  374.11  5023.8  384.79    5134  385.05    5174  382.66  5454.5  388.51
  5462.4  389.63  5467.4  388.45  5484.6  390.82  5504.6  389.45  5594.8  393.67
  5664.9  394.53  5835.2  400.02  5902.9  406.49  6001.4  409.07  6041.2  409.05
#Mann= 7 ,-1 , 0
  3644.9     .05       0  4307.5     .08       0    4332     .05       0
  5010.8     .03       0  5016.8     .05       0  5902.9      .1       0
  6001.4     .15       0
Bank Sta=4963.7,5023.8
XS Rating Curve= 0 ,0
Exp/Cntr=0.3,0.1

Type RM Length L Ch R = 1 ,29011   ,661,661,661
BEGIN DESCRIPTION:
MIMS CREEK 28.0
END DESCRIPTION:
XS GIS Cut Line= 4
      3602459.96      10604657.4      3601959.98      10603574.1
      3601959.98     10603081.04      3602015.54     10602129.64
#Sta/Elev= 30
  3552.2   405.7  3639.7   403.7  3700.5  398.11    3723  397.31    3949  387.69
  4223.9  384.71    4265  386.54  4464.8  384.21  4713.1  381.72  4759.2  382.92
  4779.2  379.97  4819.2  382.31  4839.2  381.52  4869.2  376.08  4879.2  382.25
  4969.2  384.46  4979.2  375.29  4996.2  374.15    4999  373.65  5002.2  374.15
  5019.2  377.67  5029.2  384.45  5067.2  383.81  5159.2     382  5409.5  385.84
    5492  389.39  5559.8  388.91  5930.4  397.05  6110.7  405.38  6191.4  404.82
#Mann= 9 ,-1 , 0
  3552.2      .1       0  3700.5     .08       0    3723     .05       0
  4223.9     .16       0  4464.8     .12       0  4713.1     .16       0
  4996.2     .07       0  5002.2     .16       0  5067.2     .05       0
#XS Ineff= 1 ,-1
    3950 4877.27  382.57
Permanent Ineff=
       T
Bank Sta=4969.2,5029.2
XS Rating Curve= 0 ,0
Exp/Cntr=0.3,0.1

Type RM Length L Ch R = 1 ,28350   ,463,463,463
BEGIN DESCRIPTION:
MIMS CREEK 27.0
END DESCRIPTION:
XS GIS Cut Line= 3
      3602772.49     10604560.23      3602390.53     10603004.65
      3602418.26     10602464.05
#Sta/Elev= 30
  3658.8  406.21  3669.1  403.98  3703.4  403.61  3776.5  403.26  3901.2  398.03
  4025.9  396.71    4081  393.43  4238.8  390.07  4321.9  386.43  4328.2  384.77
  4358.4   382.8  4451.8  380.81  4585.6  380.62  4637.1  382.03  4876.2   383.2
  4966.6  383.39  4976.9  381.18  4992.1  375.45  4994.5  371.69  4997.2  371.19
  5000.5  371.69  5015.3  374.66  5018.1  375.14  5028.4  383.37  5033.7  387.04
  5163.5  398.92  5285.1  403.66  5315.1  407.33  5355.2  408.09  5801.9  407.14
#Mann= 6 ,-1 , 0
  3658.8      .1       0  3703.4     .05       0  4876.2     .16       0
  4994.5     .07       0  5000.5     .16       0  5015.3     .05       0
Bank Sta=4966.6,5028.4
XS Rating Curve= 0 ,0
Exp/Cntr=0.3,0.1

Type RM Length L Ch R = 1 ,27887   ,415,415,415
BEGIN DESCRIPTION:
MIMS CREEK 26.0
END DESCRIPTION:
XS GIS Cut Line= 4
      3603584.96     10604226.85      3602821.09     10603372.71
      3602508.59     10602712.99      3602501.64     10602497.68
#Sta/Elev= 30
  3614.3  415.84    3828  410.49  3927.5  405.69  4005.2  400.01  4090.5  396.28
  4146.5  391.76    4246  387.37  4352.1  381.89  4564.5  379.53  4663.9  380.93
  4684.8  379.15    4699  380.37  4951.1  382.43  4959.4   382.1  4964.9  379.69
  4973.2  381.69  4987.7   381.3  4995.3  372.77  5001.9  370.76  5004.6  370.26
  5007.9  370.76  5017.5  370.82  5027.6  373.06  5039.6   382.2  5117.1  384.73
  5205.6  392.68  5288.9   401.6  5339.9  405.38    5489  407.23  5705.6     407
#Mann= 5 ,-1 , 0
  3614.3     .05       0    4246     .16       0  5001.9     .07       0
  5007.9     .16       0  5205.6     .05       0
Bank Sta=4987.7,5039.6
XS Rating Curve= 0 ,0
Exp/Cntr=0.3,0.1

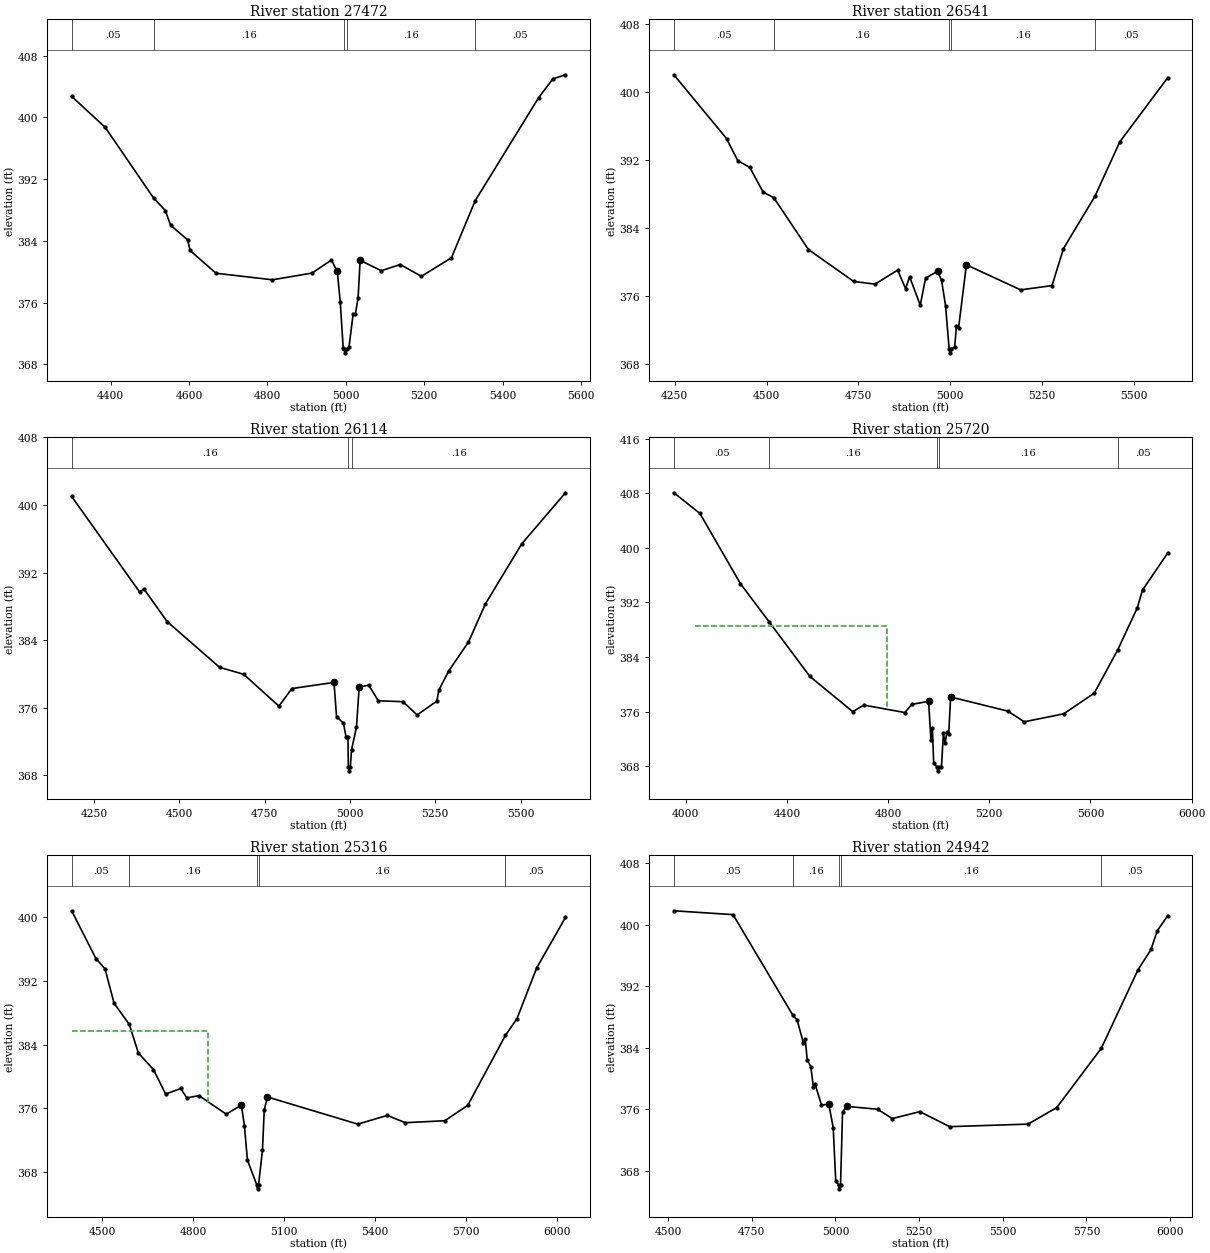
Type RM Length L Ch R = 1 ,27472   ,931,931,931
BEGIN DESCRIPTION:
MIMS CREEK 25.0
END DESCRIPTION:
XS GIS Cut Line= 3
      3603449.62      10603710.2      3603049.61     10603110.19
      3602849.62     10602610.23
#Sta/Elev= 30
  4300.9  402.73  4386.5  398.71  4509.7  389.56  4539.8  387.93  4553.3  386.02
  4596.9  384.12  4602.9  382.75    4669   379.8  4813.2  378.95  4913.9  379.82
  4963.4  381.51  4978.5  380.03    4986  376.09  4993.5  370.16  4996.5  369.98
  4999.2  369.48  5002.5  369.98  5008.5  370.28    5019  374.55  5024.7  374.55
  5031.5   376.6  5036.8  381.47  5090.7  380.13  5139.2  380.93    5193   379.4
  5269.7  381.81  5330.3  389.21  5491.9  402.55  5528.2  404.99  5560.5  405.53
#Mann= 5 ,-1 , 0
  4300.9     .05       0  4509.7     .16       0  4996.5     .07       0
  5002.5     .16       0  5330.3     .05       0
Bank Sta=4978.5,5036.8
XS Rating Curve= 0 ,0
Exp/Cntr=0.3,0.1

Type RM Length L Ch R = 1 ,26541   ,427,427,427
BEGIN DESCRIPTION:
MIMS CREEK 23.0
END DESCRIPTION:
XS GIS Cut Line= 3
      3603899.61     10603510.19      3603599.61     10602810.19
       3603299.6     10602310.17
#Sta/Elev= 30
  4247.5  401.98  4390.8  394.49  4421.6  391.88  4454.2   391.1  4490.5  388.19
  4519.5  387.54  4613.8  381.45  4737.1   377.7  4795.1  377.38  4856.8  379.02
  4878.5  376.85  4889.4  378.25  4918.4  374.91  4932.9  378.09  4965.6  378.89
  4976.4  377.83  4987.3  374.86    4997  369.81  4999.8  369.31    5003  369.81
    5012  369.94  5016.9  372.42  5022.7  372.23  5044.1  379.65  5191.8  376.71
  5277.3  377.21  5308.4  381.56  5393.9  387.69    5462  394.11  5592.2  401.63
#Mann= 5 ,-1 , 0
  4247.5     .05       0  4519.5     .16       0    4997     .07       0
    5003     .16       0  5393.9     .05       0
Bank Sta=4965.6,5044.1
XS Rating Curve= 0 ,0
Exp/Cntr=0.3,0.1

Type RM Length L Ch R = 1 ,26114   ,394,394,394
BEGIN DESCRIPTION:
MIMS CREEK 22.0
END DESCRIPTION:
XS GIS Cut Line= 3
      3603999.61     10603510.21      3603899.61     10602710.19
      3603399.58     10602310.17
#Sta/Elev= 30
  4184.9     401    4384  389.69  4396.6  390.05  4464.6  386.19  4618.3  380.77
  4688.8  379.95  4792.1  376.18  4829.9  378.26  4953.4  378.99  4960.9  374.93
  4981.1  374.17  4988.6  372.58  4994.4  372.58  4995.4  369.02  4998.1  368.52
  5001.4  369.02  5004.8  371.02  5019.2  373.66  5027.2  378.45  5055.2  378.66
  5083.2  376.81  5155.2  376.71  5196.9  375.14  5254.5  376.76  5260.9   378.1
  5289.7  380.36  5347.3  383.76  5396.9  388.28  5503.4  395.39  5631.5  401.44
#Mann= 3 ,-1 , 0
  4184.9     .16       0  4995.4     .07       0  5004.8     .16       0
Bank Sta=4953.4,5027.2
XS Rating Curve= 0 ,0
Exp/Cntr=0.3,0.1

Type RM Length L Ch R = 1 ,25720   ,404,404,404
BEGIN DESCRIPTION:
MIMS CREEK 21.0
END DESCRIPTION:
XS GIS Cut Line= 3
      3604749.59     10603510.16      3604249.61     10602610.19
       3603649.6     10601910.17
#Sta/Elev= 30
  3953.7  408.07  4056.6  405.04  4216.8  394.75    4330  389.17  4491.3  381.16
  4660.6  376.01  4704.1  376.97  4866.5  375.88    4894  377.07  4960.3  377.52
  4969.5  371.92  4975.2  373.66  4980.4  368.54  4993.9  367.84  4996.7  367.34
  4999.9  367.84  5011.2  367.96  5018.9  372.86  5025.5  371.43  5033.2  372.99
  5039.7  372.67  5047.4  378.16  5273.5  376.09  5338.3  374.52  5494.1  375.69
  5614.9  378.71  5707.1  385.01    5785   391.2  5805.8  393.82  5905.2  399.24
#Mann= 5 ,-1 , 0
  3953.7     .05       0    4330     .16       0  4993.9     .07       0
  4999.9     .16       0  5707.1     .05       0
#XS Ineff= 1 ,-1
 4038.35 4794.03  388.58
Permanent Ineff=
       F
Bank Sta=4960.3,5047.4
XS Rating Curve= 0 ,0
Exp/Cntr=0.3,0.1

Type RM Length L Ch R = 1 ,25316   ,374,374,374
BEGIN DESCRIPTION:
MIMS CREEK 20.0
END DESCRIPTION:
XS GIS Cut Line= 3
      3605149.59     10602360.19      3604549.61     10602360.19
      3603649.65     10601860.21
#Sta/Elev= 30
  4398.9  400.77  4478.9  394.78  4508.9   393.5  4538.9  389.17  4588.9  386.54
  4618.9  382.95  4668.9  380.86  4708.9  377.79  4758.9  378.49  4778.9  377.31
  4818.9   377.6  4908.9  375.27  4958.9  376.41  4968.9  373.84  4978.9  369.52
  5009.6  366.41  5012.4  365.91  5015.6  366.41  5028.6  370.79  5034.3  375.76
  5044.6  377.43  5343.2  374.02  5440.4  375.12  5499.9   374.2  5630.3  374.45
  5705.8  376.37  5830.5  385.16  5868.3  387.23  5933.5  393.61  6028.4  399.93
#Mann= 5 ,-1 , 0
  4398.9     .05       0  4588.9     .16       0  5009.6     .07       0
  5015.6     .16       0  5830.5     .05       0
#XS Ineff= 1 ,-1
 4377.27    4850  385.74
Permanent Ineff=
       F
Bank Sta=4958.9,5044.6
XS Rating Curve= 0 ,0
Exp/Cntr=0.3,0.1

Type RM Length L Ch R = 1 ,24942   ,592,592,592
BEGIN DESCRIPTION:
MIMS CREEK 19.0
END DESCRIPTION:
XS GIS Cut Line= 3
      3605049.62     10601860.19      3604596.18     10602040.74
      3603649.64      10601760.2
#Sta/Elev= 30
  4517.3  401.82    4694  401.32  4872.5  388.26  4885.4  387.64  4904.3  384.65
  4909.7  385.17  4915.6  382.45  4926.3  381.58    4934  378.96  4939.4  379.26
  4958.3  376.59  4980.1  376.68  4993.3  373.64  5000.8  366.75  5009.2  366.19
    5012  365.69  5015.2  366.19  5021.2  375.66  5033.1  376.41  5126.1  376.03
  5169.8  374.82  5252.1  375.72  5341.2  373.77  5575.4   374.1  5661.2  376.25
  5794.2  383.95  5904.3  394.18  5942.8  396.79  5961.3   399.2  5992.6  401.18
#Mann= 5 ,-1 , 0
  4517.3     .05       0  4872.5     .16       0  5009.2     .07       0
  5015.2     .16       0  5794.2     .05       0
Bank Sta=4980.1,5033.1
XS Rating Curve= 0 ,0
Exp/Cntr=0.3,0.1

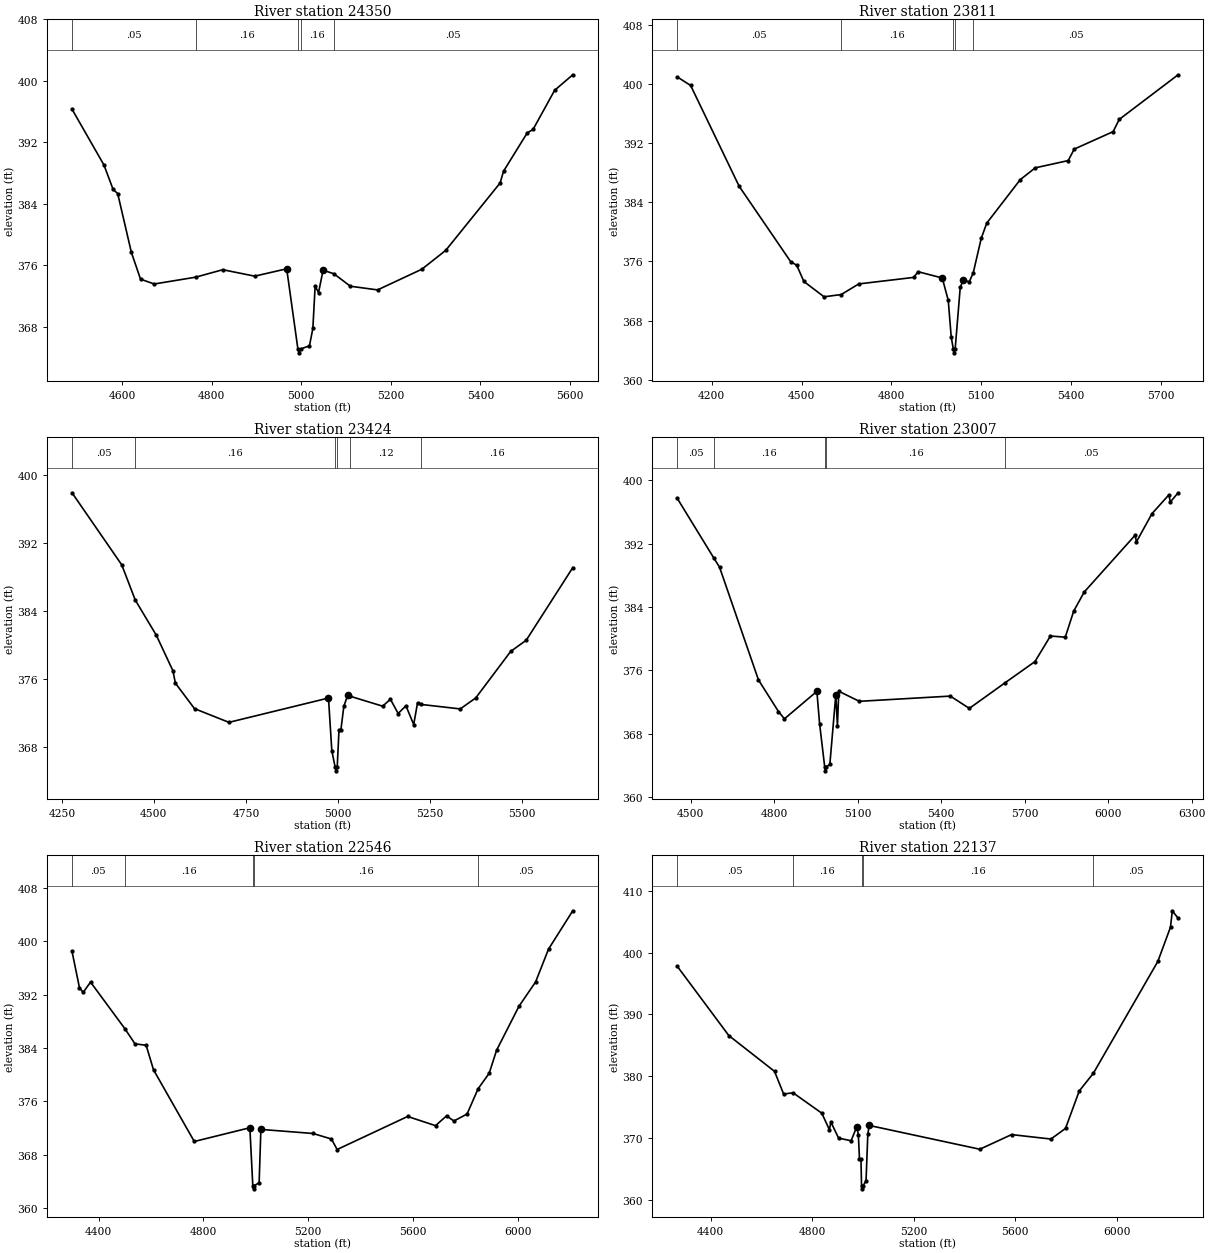
Type RM Length L Ch R = 1 ,24350   ,539,539,539
BEGIN DESCRIPTION:
MIMS CREEK 18.0
END DESCRIPTION:
XS GIS Cut Line= 3
      3604799.66      10601760.2      3604299.61     10601660.19
      3603699.63     10601560.19
#Sta/Elev= 30
  4488.1   396.3  4559.5  389.03  4579.9  385.85  4590.1  385.32  4620.7  377.65
  4641.1  374.18  4671.7  373.55  4764.4  374.44  4824.7  375.41  4896.1  374.57
  4967.5  375.53  4992.5  365.09  4995.3  364.59  4998.5  365.09  5018.3   365.5
  5025.9  367.76    5031  373.29  5038.6  372.42  5048.7  375.35  5072.9  374.88
  5109.6  373.26  5170.4  372.78  5269.2  375.47  5322.5  377.92  5444.1   386.7
  5451.7  388.23  5504.9  393.24  5517.6  393.66  5565.8  398.76  5606.3  400.78
#Mann= 5 ,-1 , 0
  4488.1     .05       0  4764.4     .16       0  4992.5     .07       0
  4998.5     .16       0  5072.9     .05       0
Bank Sta=4967.5,5048.7
XS Rating Curve= 0 ,0
Exp/Cntr=0.3,0.1

Type RM Length L Ch R = 1 ,23811   ,387,387,387
BEGIN DESCRIPTION:
MIMS CREEK 17.0
END DESCRIPTION:
XS GIS Cut Line= 3
      3605153.43     10601363.65       3604299.3     10601223.03
      3603493.36     10601280.22
#Sta/Elev= 30
  4084.8  400.92  4129.2  399.78  4291.4  386.16  4463.7  375.97  4483.9  375.49
  4507.7   373.3  4575.1  371.23  4632.2  371.53  4691.3  372.97  4874.8  373.85
  4889.3  374.62  4970.2  373.77  4990.2  370.76  5000.2  365.78  5007.3  364.16
    5010  363.66  5013.3  364.16  5030.3   372.5  5040.3   373.5  5060.4  373.25
  5073.8  374.47  5100.5  379.13  5118.9  381.18  5230.8  387.05    5281  388.65
  5391.2  389.63  5411.3  391.18  5541.3  393.54  5561.7  395.19  5758.4  401.22
#Mann= 5 ,-1 , 0
  4084.8     .05       0  4632.2     .16       0  5007.3     .07       0
  5013.3     .16       0  5073.8     .05       0
Bank Sta=4970.2,5040.3
XS Rating Curve= 0 ,0
Exp/Cntr=0.3,0.1

Type RM Length L Ch R = 1 ,23424   ,417,417,417
BEGIN DESCRIPTION:
MIMS CREEK 16.0
END DESCRIPTION:
XS GIS Cut Line= 3
       3605149.6     10601110.19      3604449.61     10600910.19
      3603849.57     10600710.18
#Sta/Elev= 30
  4277.6  397.92  4412.8  389.44  4449.4  385.31  4506.4  381.19  4551.9  376.98
  4558.4  375.54  4610.4  372.54    4704  370.93  4974.4  373.79  4983.5  367.59
  4992.2  365.73    4995  365.23  4998.2  365.73    5003  370.07  5008.2  370.07
  5016.1  372.81  5026.7  374.13  5032.5  374.01  5121.6  372.83  5142.6  373.65
  5163.7  371.97  5184.8  372.88  5205.9  370.67  5216.4  373.23  5227.1  373.03
  5332.4  372.51  5374.5   373.8  5469.4  379.27  5511.6  380.58  5638.1  389.12
#Mann= 6 ,-1 , 0
  4277.6     .05       0  4449.4     .16       0  4992.2     .07       0
  4998.2     .16       0  5032.5     .12       0  5227.1     .16       0
Bank Sta=4974.4,5026.7
XS Rating Curve= 0 ,0
Exp/Cntr=0.3,0.1

Type RM Length L Ch R = 1 ,23007   ,461,461,461
BEGIN DESCRIPTION:
MIMS CREEK 15.0
END DESCRIPTION:
XS GIS Cut Line= 3
      3605199.63      10600960.2      3604699.61     10600660.19
      3603499.59     10600460.18
#Sta/Elev= 30
  4451.6  397.69  4581.8  390.23  4603.2  389.03  4743.2   374.8  4815.1  370.81
  4836.5  369.89  4953.1  373.36  4962.8  369.29  4981.2  363.83  4983.9  363.33
  4987.2  363.83  4999.7  364.14  5021.1  372.91    5027     369  5031.8  373.37
  5105.7   372.1  5432.6  372.76  5501.1  371.21  5627.9   374.4  5736.8  377.11
  5792.5  380.34  5845.8  380.19  5876.2  383.49  5914.2   385.9  6096.7  393.05
  6101.7  392.23  6157.5  395.78  6218.3  398.15  6223.4  397.24  6251.3  398.41
#Mann= 5 ,-1 , 0
  4451.6     .05       0  4581.8     .16       0  4981.2     .07       0
  4987.2     .16       0  5627.9     .05       0
Bank Sta=4953.1,5021.1
XS Rating Curve= 0 ,0
Exp/Cntr=0.3,0.1

Type RM Length L Ch R = 1 ,22546   ,409,409,409
BEGIN DESCRIPTION:
MIMS CREEK 14.0
END DESCRIPTION:
XS GIS Cut Line= 3
      3605249.62      10600910.2      3604749.61     10600410.19
       3603849.6     10599610.18
#Sta/Elev= 30
  4298.6  398.47  4326.9  393.04    4341  392.32  4369.3  393.87  4499.8  386.92
    4539  384.62  4581.5  384.41  4609.7  380.73  4765.3     370  4977.4  372.06
  4988.6  363.41  4991.3  362.91  4994.6  363.41  5012.8  363.82  5019.5  371.81
  5218.5   371.2  5288.8  370.37  5310.5   368.8  5579.8  373.75    5686  372.37
  5728.2  373.84  5756.2  373.07  5806.4  374.11  5848.5  377.89  5890.9  380.22
  5919.3  383.68  6004.6  390.25  6068.1   393.9  6117.5  398.82  6209.9  404.55
#Mann= 5 ,-1 , 0
  4298.6     .05       0  4499.8     .16       0  4988.6     .07       0
  4994.6     .16       0  5848.5     .05       0
Bank Sta=4977.4,5019.5
XS Rating Curve= 0 ,0
Exp/Cntr=0.3,0.1

Type RM Length L Ch R = 1 ,22137   ,472,472,472
BEGIN DESCRIPTION:
MIMS CREEK 13.0
END DESCRIPTION:
XS GIS Cut Line= 3
       3605599.6     10600560.18      3604999.61     10600160.19
      3603899.61     10599560.19
#Sta/Elev= 30
  4268.4  397.78  4471.2  386.59  4651.5  380.79  4687.5  377.11  4724.5  377.32
  4837.8  374.02  4867.8  371.35  4873.8  372.58  4903.9  369.99  4953.4  369.55
    4976  371.85    4982  370.53  4986.5  366.58  4992.3  366.58  4994.6  362.27
  4997.3  361.77  5000.6  362.27  5012.3  363.05  5019.4  370.68  5025.1  372.03
  5460.8  368.18  5586.1  370.55  5741.3  369.83  5798.7  371.55  5852.8  377.61
  5908.6  380.49  6162.8  398.59  6212.6  404.14  6219.7  406.78  6242.5  405.58
#Mann= 5 ,-1 , 0
  4268.4     .05       0  4724.5     .16       0  4994.6     .07       0
  5000.6     .16       0  5908.6     .05       0
Bank Sta=4976,5025.1
XS Rating Curve= 0 ,0
Exp/Cntr=0.3,0.1

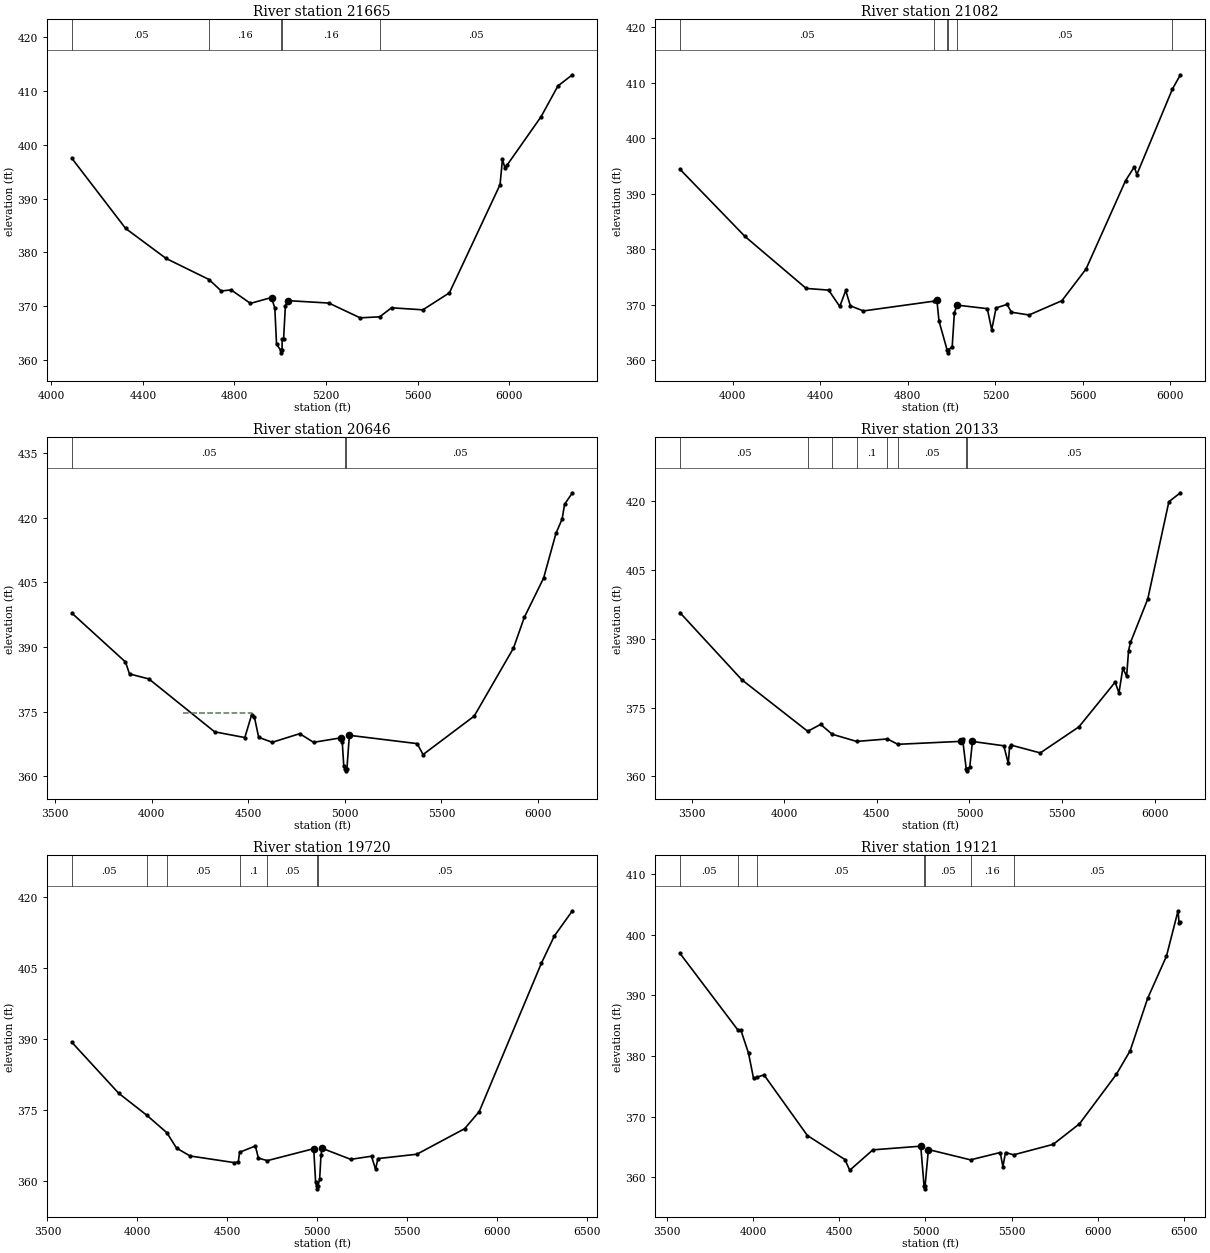
Type RM Length L Ch R = 1 ,21665   ,583,583,583
BEGIN DESCRIPTION:
MIMS CREEK 12.0
END DESCRIPTION:
XS GIS Cut Line= 3
      3605699.59     10600410.17      3604999.61     10599810.19
      3603799.64      10599410.2
#Sta/Elev= 30
  4089.9  397.46  4324.2  384.45  4500.9  378.87  4688.6  374.95  4742.4  372.81
  4785.2  373.02  4869.7  370.51  4961.9   371.6  4976.2  369.62  4983.8  362.91
  5001.7  361.81  5004.4  361.31  5007.7  361.81  5008.5  363.86  5014.5  363.86
  5022.4  370.05  5032.9  371.02  5212.1  370.57  5349.1  367.82  5434.8  368.01
  5486.2  369.69  5623.2  369.31  5739.1  372.47  5960.5  392.59    5971  397.31
  5981.6  395.75  5992.1  396.28  6139.7  405.23  6213.5  410.96  6276.7  413.03
#Mann= 5 ,-1 , 0
  4089.9     .05       0  4688.6     .16       0  5001.7     .07       0
  5007.7     .16       0  5434.8     .05       0
Bank Sta=4961.9,5032.9
XS Rating Curve= 0 ,0
Exp/Cntr=0.3,0.1

Type RM Length L Ch R = 1 ,21082   ,436,436,436
BEGIN DESCRIPTION:
MIMS CREEK 11.0
END DESCRIPTION:
XS GIS Cut Line= 3
      3605949.64     10600060.21      3605018.05     10599446.99
      3603849.58     10599360.19
#Sta/Elev= 30
  3758.7   394.4  4055.4  382.33  4335.5  372.96    4438  372.66    4489  369.71
  4516.2  372.59  4537.3  369.83  4596.8  368.91  4921.3  370.68  4932.6   370.9
  4942.6  367.06  4979.7  361.87  4982.5  361.37  4985.7  361.87  5002.8  362.51
  5012.8  368.58  5024.6  369.96  5163.2  369.32  5183.3  365.52  5203.4  369.46
  5253.5  370.08  5273.5  368.68  5353.8  368.18  5504.2  370.75  5614.5  376.46
    5795  392.35  5835.1  394.84  5846.7  393.46  6009.1  408.83  6045.7  411.41
#Mann= 6 ,-1 , 0
  3758.7     .05       0  4921.3     .16       0  4979.7     .07       0
  4985.7     .16       0  5024.6     .05       0  6009.1     .08       0
Bank Sta=4932.6,5024.6
XS Rating Curve= 0 ,0
Exp/Cntr=0.3,0.1

Type RM Length L Ch R = 1 ,20646   ,513,513,513
BEGIN DESCRIPTION:
MIMS CREEK 10.0
END DESCRIPTION:
XS GIS Cut Line= 3
      3606049.58     10600060.17      3604949.61     10599160.19
      3603849.61     10598760.19
#Sta/Elev= 30
  3586.6  397.82  3863.6  386.51  3884.5  383.73    3985  382.57  4325.2  370.29
  4481.7  368.96  4516.9  374.24  4531.2  373.73  4553.5     369  4623.8  367.86
  4765.9  369.86  4837.7  367.85  4979.8   368.9  4986.3  367.92  4994.2  362.33
  5001.6  361.73  5004.4  361.23  5007.6  361.73  5010.5  361.73  5023.1  369.48
  5374.3  367.55  5404.9  365.01  5669.6  373.94  5873.1  389.73  5928.9  396.84
  6029.3  406.01  6093.2  416.39  6125.1  419.71  6137.7  423.12  6178.3   425.8
#Mann= 3 ,-1 , 0
  3586.6     .05       0  5001.6     .03       0  5007.6     .05       0
#XS Ineff= 1 ,-1
 4161.36  4516.9  374.72
Permanent Ineff=
       F
Bank Sta=4979.8,5023.1
XS Rating Curve= 0 ,0
Exp/Cntr=0.3,0.1

Type RM Length L Ch R = 1 ,20133   ,413,413,413
BEGIN DESCRIPTION:
MIMS CREEK 9.0
END DESCRIPTION:
XS GIS Cut Line= 3
       3606049.6     10599960.18      3605049.61     10598760.19
      3603949.62     10598460.19
#Sta/Elev= 30
  3437.1  395.73    3771  381.09  4126.8  369.84  4196.6  371.35  4258.8   369.2
  4390.8  367.63  4557.1  368.17  4613.5     367  4956.8  367.65  4963.3   368.1
  4982.5  361.71  4985.2  361.21  4988.5  361.71  5001.7  361.96  5016.4  367.62
  5185.7  366.68  5209.9  362.84  5216.8  366.35  5227.2   366.8  5382.6  365.12
  5591.7  370.82  5786.9  380.56  5807.6  378.22  5828.4  383.58  5849.1  381.88
  5859.4  387.45  5869.8  389.23  5963.1  398.72  6077.1  419.95  6139.3   421.9
#Mann= 8 ,-1 , 0
  3437.1     .05       0  4126.8     .08       0  4258.8     .05       0
  4390.8      .1       0  4557.1     .15       0  4613.5     .05       0
  4982.5     .03       0  4988.5     .05       0
Bank Sta=4956.8,5016.4
XS Rating Curve= 0 ,0
Exp/Cntr=0.3,0.1

Type RM Length L Ch R = 1 ,19720   ,599,599,599
BEGIN DESCRIPTION:
MIMS CREEK 8.0
END DESCRIPTION:
XS GIS Cut Line= 3
      3605999.63     10599810.22      3605399.61     10598610.19
      3604199.61     10597810.19
#Sta/Elev= 30
  3636.6  389.25  3896.6  378.53  4052.3  373.91  4164.2  370.22    4218  366.98
  4293.5  365.31  4539.5  363.91  4561.8  364.05    4569   366.1  4656.8  367.41
  4673.6  364.86  4723.4  364.33  4981.3  366.85  4991.8  359.91  4997.8  358.88
  5000.6  358.38  5003.8  358.88  5014.3  360.35  5021.8  365.54  5027.9  366.93
  5187.1   364.6  5302.8  365.26  5325.3  362.53  5338.8  364.76  5555.2  365.68
  5821.1  371.07  5902.2  374.68  6247.7  405.94  6319.8  411.69  6420.5  417.02
#Mann= 7 ,-1 , 0
  3636.6     .05       0  4052.3     .08       0  4164.2     .05       0
    4569      .1       0  4723.4     .05       0  4997.8     .03       0
  5003.8     .05       0
Bank Sta=4981.3,5027.9
XS Rating Curve= 0 ,0
Exp/Cntr=0.3,0.1

Type RM Length L Ch R = 1 ,19121   ,930,930,930
BEGIN DESCRIPTION:
MIMS CREEK 7.0
END DESCRIPTION:
XS GIS Cut Line= 3
      3606341.24     10599753.08      3605679.51     10598420.94
      3604449.64     10597710.21
#Sta/Elev= 30
  3573.4  396.95  3908.2  384.36  3926.9  384.29  3971.7  380.46  4000.9  376.29
  4019.9  376.48  4061.3  376.89  4313.6  366.87  4531.8   362.9  4559.8  361.13
  4694.3   364.5  4972.4  365.11  4991.7  358.56  4994.4  358.06  4997.7  358.56
    5017  364.55  5261.6  362.85  5434.1  364.06  5449.9  361.74    5465  364.06
  5512.3  363.68  5742.2  365.41  5894.9   368.8  6108.8  376.96  6189.2  380.86
  6291.1  389.53  6400.5  396.51  6467.7  403.99  6473.5  401.98  6481.3  402.08
#Mann= 7 ,-1 , 0
  3573.4     .05       0  3908.2     .08       0  4019.9     .05       0
  4991.7     .03       0  4997.7     .05       0  5261.6     .16       0
  5512.3     .05       0
Bank Sta=4972.4,5017
XS Rating Curve= 0 ,0
Exp/Cntr=0.3,0.1

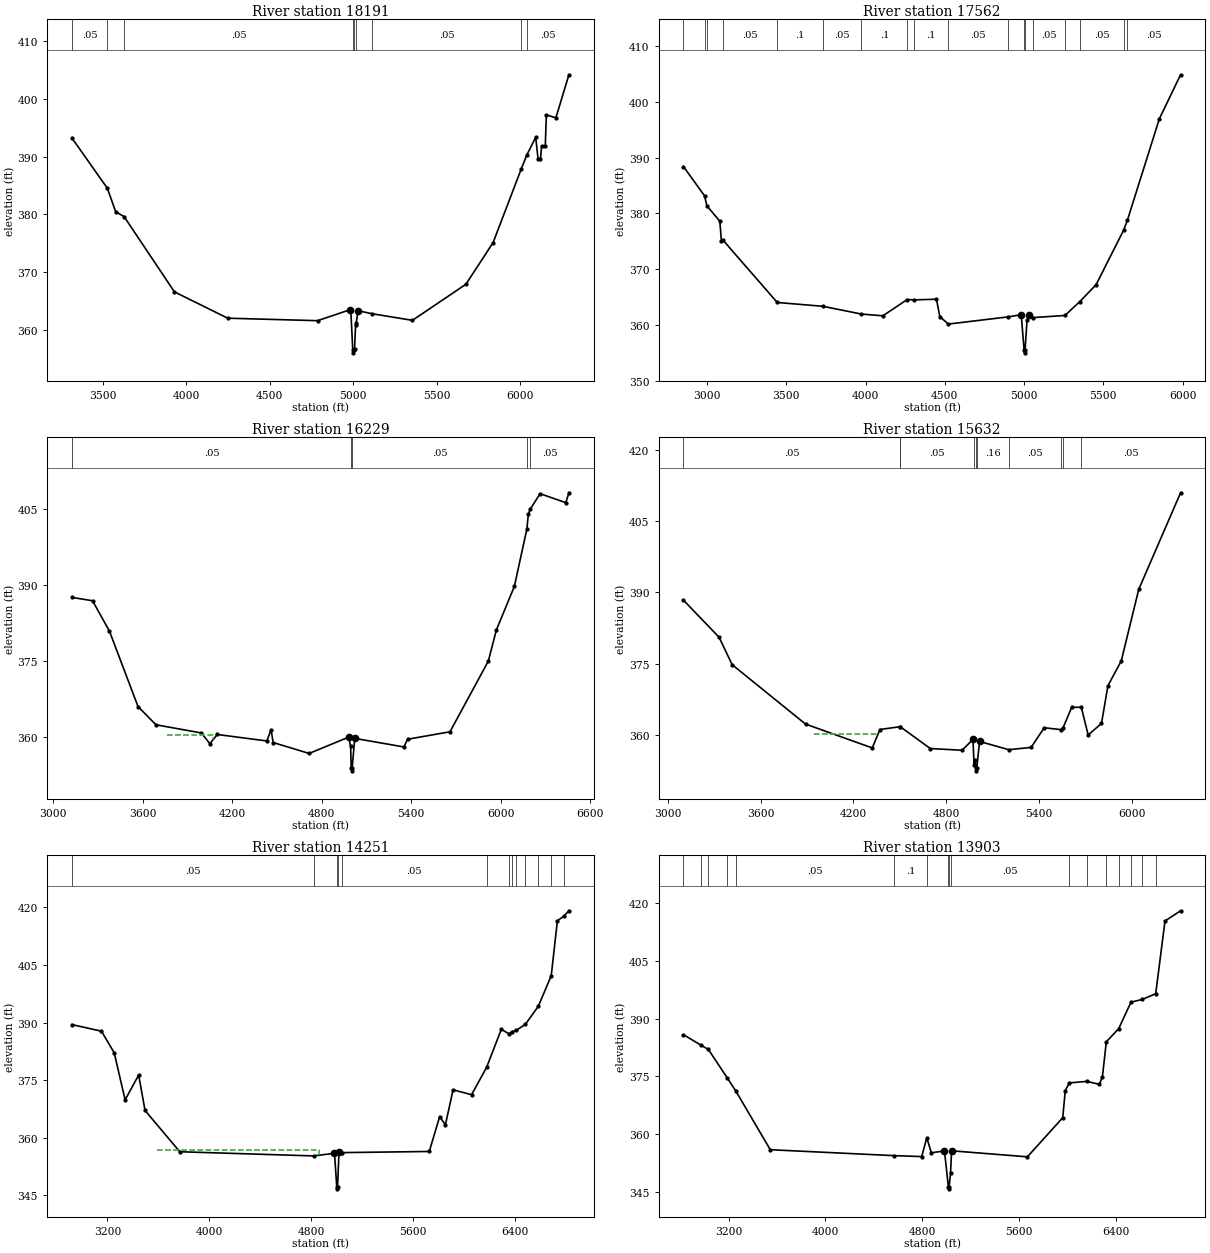
Type RM Length L Ch R = 1 ,18191   ,629,629,629
BEGIN DESCRIPTION:
MIMS CREEK 6.0
END DESCRIPTION:
XS GIS Cut Line= 3
       3606410.7     10599669.77      3606146.81     10598162.84
      3605043.59     10597226.14
#Sta/Elev= 30
    3315  393.26  3527.6  384.53  3577.8  380.44  3627.9  379.61  3929.4  366.55
  4248.6  361.98  4786.6  361.55  4979.6  363.43  4986.2  363.16  4997.5  356.47
  5000.2  355.97  5003.5  356.47  5008.2  356.59  5014.7  360.87  5018.3  361.12
    5029  363.28  5115.7  362.74  5355.2  361.61  5674.9  367.86  5838.2   375.1
  6005.5  387.78  6040.3  390.31  6093.4  393.38  6107.6  389.54  6121.9  389.57
  6128.5  391.79  6150.5  391.78  6157.1  397.25  6214.2  396.75  6292.1  404.21
#Mann= 9 ,-1 , 0
    3315     .05       0  3527.6     .08       0  3627.9     .05       0
  4997.5     .03       0  5003.5     .05       0  5018.3     .16       0
  5115.7     .05       0  6005.5     .08       0  6040.3     .05       0
Bank Sta=4979.6,5029
XS Rating Curve= 0 ,0
Exp/Cntr=0.3,0.1

Type RM Length L Ch R = 1 ,17562   ,1333,1333,1333
BEGIN DESCRIPTION:
Mapping XS 04792f3b
END DESCRIPTION:
XS GIS Cut Line= 3
      3606882.93     10599621.21      3606362.09     10597697.56
      3605391.28     10597094.28
#Sta/Elev= 30
  2851.5  388.38  2984.1  383.14  2999.1  381.34  3080.5  378.59  3090.8  375.04
  3101.8  375.15    3443  364.01  3729.8  363.33  3974.4  361.93  4109.5  361.62
  4262.9  364.54  4305.5  364.47  4447.5   364.6  4468.7  361.47  4522.6  360.14
  4900.2  361.43  4982.1  361.81  5000.4  355.48  5003.1  354.98  5006.4  355.48
  5018.7  360.82  5034.1   361.7  5056.5   361.3  5258.1  361.68  5351.5  364.16
  5454.4  367.19    5628  376.97  5652.1  378.76  5853.5  396.94  5987.4  404.84
#Mann= 18 ,-1 , 0
  2851.5     .12       0  2984.1     .05       0  2999.1     .08       0
  3101.8     .05       0    3443      .1       0  3729.8     .05       0
  3974.4      .1       0  4262.9     .15       0  4305.5      .1       0
  4522.6     .05       0  4900.2     .16       0  5000.4     .07       0
  5006.4     .16       0  5056.5     .05       0  5258.1     .08       0
  5351.5     .05       0    5628     .08       0  5652.1     .05       0
Bank Sta=4982.1,5034.1
XS Rating Curve= 0 ,0
Exp/Cntr=0.3,0.1

Type RM Length L Ch R = 1 ,16229   ,597,597,597
BEGIN DESCRIPTION:
Mapping XS a7d6cf71
END DESCRIPTION:
XS GIS Cut Line= 3
      3608105.12     10598621.15      3606987.09      10597405.9
      3605355.12     10597010.06
#Sta/Elev= 30
  3125.4  387.54  3264.2  386.88  3377.7  380.87  3568.8  366.02    3689  362.42
  3993.6  360.81  4050.3  358.69  4099.6  360.51  4431.9  359.23  4460.3  361.43
  4474.5  358.92  4715.5  356.77  4979.9  359.98  4993.6  358.15  4997.5  353.84
  5000.2  353.34  5003.5  353.84  5021.1  359.74  5350.4  358.05  5374.9  359.57
  5659.1  361.04  5916.3  374.99  5970.2  381.14  6090.5   389.7  6174.1  400.98
  6184.3  403.94  6196.8  404.93  6262.8  407.99  6435.1  406.22    6456  408.17
#Mann= 5 ,-1 , 0
  3125.4     .05       0  4997.5     .03       0  5003.5     .05       0
  6174.1     .08       0  6196.8     .05       0
#XS Ineff= 1 ,-1
 3761.52 4073.61   360.4
Permanent Ineff=
       T
Bank Sta=4979.9,5021.1
XS Rating Curve= 0 ,0
Exp/Cntr=0.3,0.1

Type RM Length L Ch R = 1 ,15632   ,1381,1381,1381
BEGIN DESCRIPTION:
Mapping XS 9935af0c
END DESCRIPTION:
XS GIS Cut Line= 3
      3608417.68     10598426.76      3606862.09     10596885.06
      3606077.35     10596232.27
#Sta/Elev= 30
  3102.4  388.38    3332  380.61  3416.8  374.84  3890.6  362.37  4321.9  357.36
  4371.4  361.23  4501.7  361.82  4502.5  361.82  4696.7  357.23  4901.8  356.87
  4972.4  359.15  4979.3   353.7  4986.6  354.89  4990.7  353.05  4993.4  352.55
  4996.7  353.05  5014.9  358.72  5203.4  356.99  5347.8  357.47  5432.7   361.6
  5541.7   361.2    5555  361.64  5609.8  365.87  5672.1  365.92  5716.5  360.08
  5802.5   362.5  5844.1  370.43    5930  375.61  6043.3  390.67  6313.3  410.94
#Mann= 10 ,-1 , 0
  3102.4     .05       0  4501.7     .08       0  4502.5     .05       0
  4979.3     .16       0  4990.7     .07       0  4996.7     .16       0
  5203.4     .05       0  5541.7     .08       0    5555      .1       0
  5672.1     .05       0
#XS Ineff= 1 ,-1
 3946.58 4358.03  360.21
Permanent Ineff=
       T
Bank Sta=4972.4,5014.9
XS Rating Curve= 0 ,0
Exp/Cntr=0.3,0.1

Type RM Length L Ch R = 1 ,14251   ,348,348,348
BEGIN DESCRIPTION:
Mapping XS cdec3671
END DESCRIPTION:
XS GIS Cut Line= 3
      3608632.94     10598072.59      3607181.54     10596107.29
      3605773.25     10595711.86
#Sta/Elev= 30
    2921  389.46  3153.9  387.74  3254.1   382.1  3339.7  369.84  3446.2  376.31
  3496.3  367.07  3769.3  356.32  4821.5  355.23    4985  355.92  5002.9  347.15
  5005.6  346.65  5008.9  347.15  5020.5  356.38    5045  356.09  5729.7  356.39
  5811.7   365.5  5856.2  363.29  5916.6  372.46  6062.1  371.19    6180  378.29
  6296.2  388.26  6354.5  387.05  6383.2  387.63  6414.1  387.96  6484.8  389.53
  6586.5  394.22  6688.1   402.2  6736.3  416.51  6789.7  417.79  6826.9  419.12
#Mann= 13 ,-1 , 0
    2921     .05       0  4821.5      .1       0  5002.9     .07       0
  5008.9      .1       0    5045     .05       0    6180     .08       0
  6354.5     .05       0  6383.2     .08       0  6414.1      .1       0
  6484.8     .08       0  6586.5      .1       0  6688.1     .05       0
  6789.7      .1       0
#XS Ineff= 1 ,-1
 3590.79 4863.22  356.74
Permanent Ineff=
       T
Bank Sta=4985,5020.5
XS Rating Curve= 0 ,0
Exp/Cntr=0.3,0.1

Type RM Length L Ch R = 1 ,13903   ,341,341,341
BEGIN DESCRIPTION:
Mapping XS d9906dd6
END DESCRIPTION:
XS GIS Cut Line= 4
      3608681.54     10597912.86      3608056.54     10596482.29
      3607257.92     10595989.23      3605716.22     10595530.89
#Sta/Elev= 30
  2826.9  385.84  2968.6  383.17  3032.8  382.01  3186.4   374.7  3259.5  371.18
  3544.1  355.92  4565.8  354.38  4795.6  354.13  4837.9  359.04  4874.8  355.12
  4983.8  355.61  5016.1  346.24  5018.8  345.74  5022.1  346.24  5033.9  349.86
  5042.6  355.64  5669.1  354.07  5961.2  364.25  5982.1  371.29  6015.5  373.31
  6161.4   373.7  6263.8  372.93  6289.1   374.9  6321.5     384  6423.5  387.41
  6525.5  394.32  6617.3  395.01  6729.5   396.5  6806.3  415.43    6935  418.09
#Mann= 17 ,-1 , 0
  2826.9     .05       0  2968.6     .16       0  3032.8     .05       0
  3186.4     .16       0  3259.5     .05       0  4565.8      .1       0
  4837.9     .05       0  5016.1     .03       0  5022.1     .05       0
  5033.9     .05       0  6015.5      .1       0  6161.4     .08       0
  6321.5      .1       0  6423.5     .08       0  6525.5     .05       0
  6617.3      .1       0  6729.5     .05       0
#XS Ineff= 1 ,-1
 3235.99 4816.71  355.72
Permanent Ineff=
       T
Bank Sta=4983.8,5042.6
XS Rating Curve= 0 ,0
Exp/Cntr=0.3,0.1