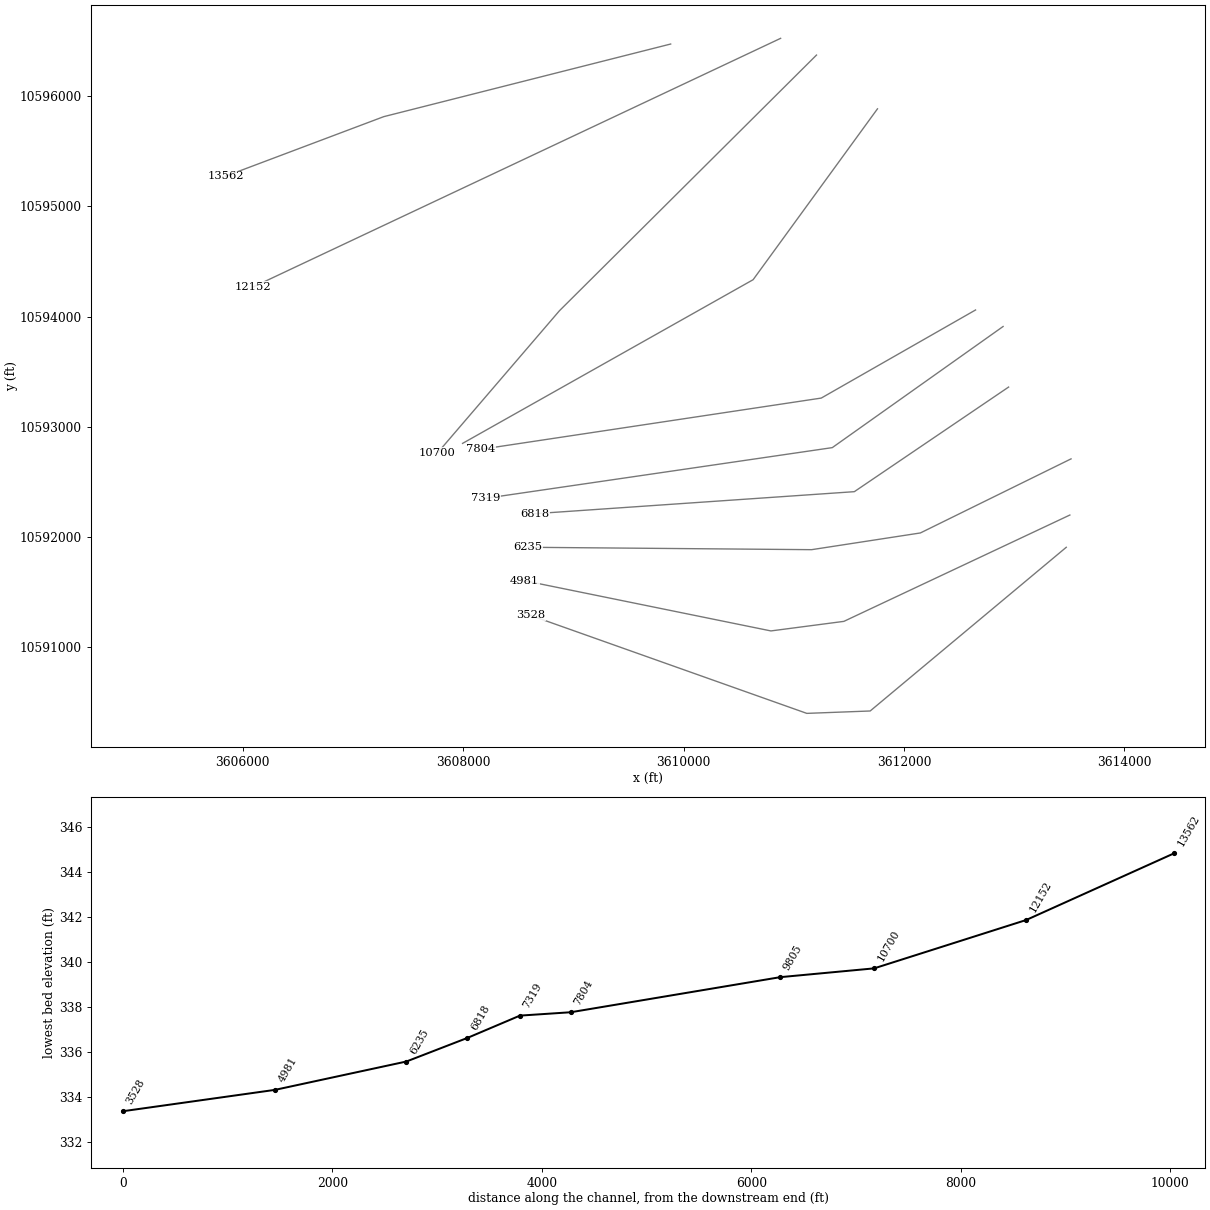
HEC-RAS study MIMS CREEK.prj: MIMS CREEK Base Level Engineering

--- MIMS CREEK.g01 (geometry) --- (continued)

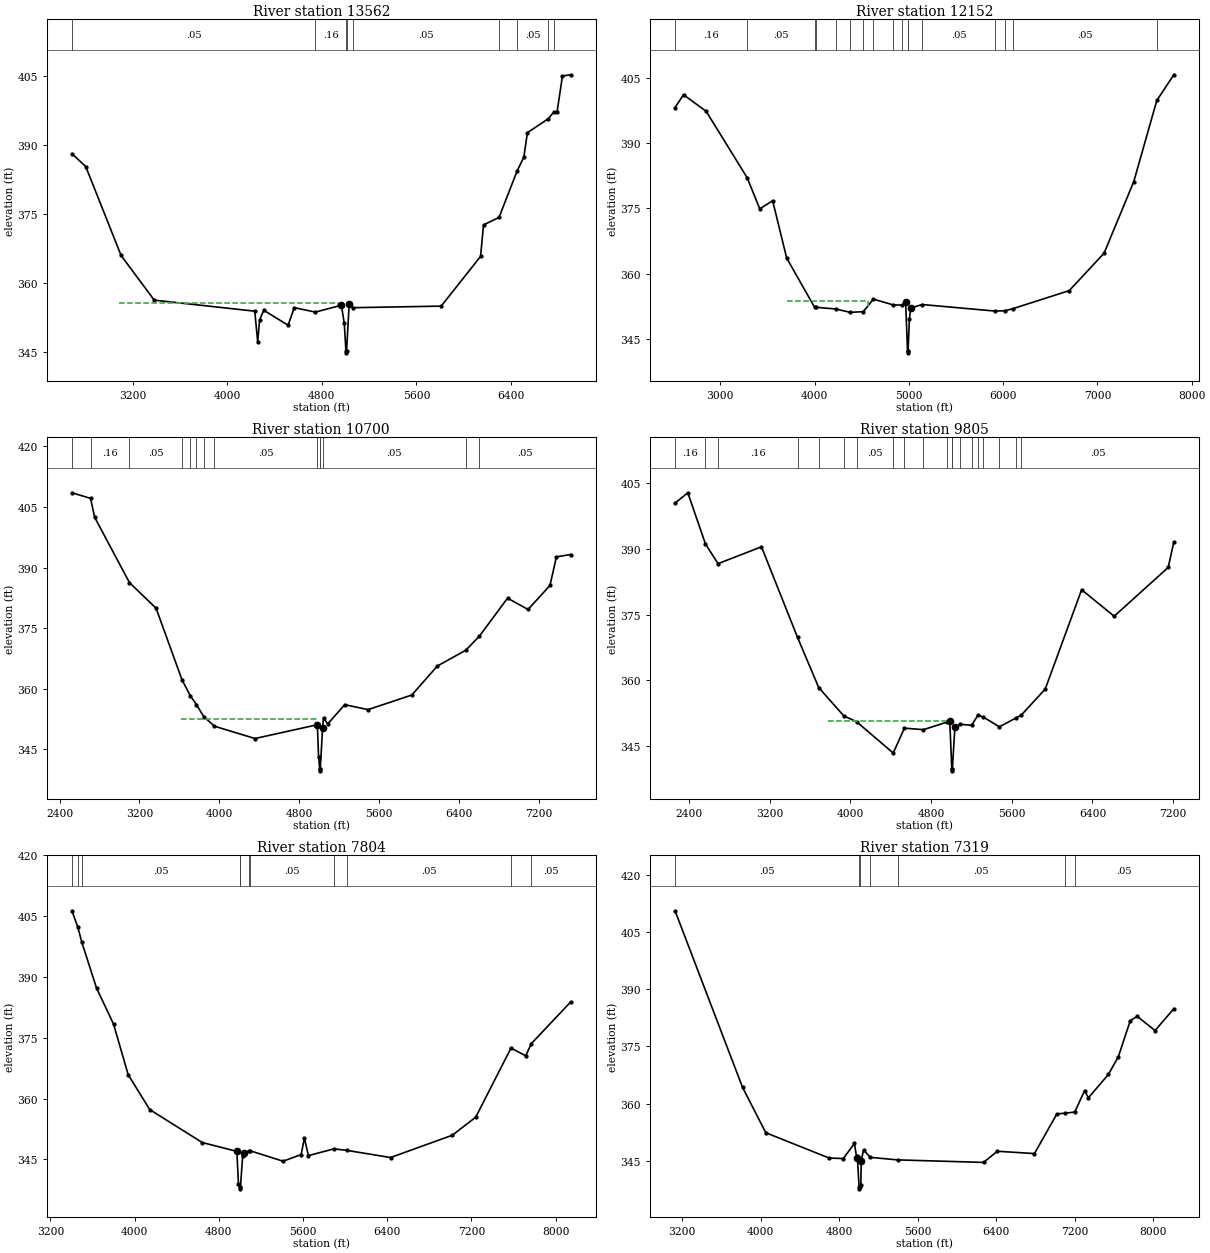
Type RM Length L Ch R = 1 ,13562   ,1410,1410,1410
BEGIN DESCRIPTION:
MIMS CREEK 5.0
END DESCRIPTION:
XS GIS Cut Line= 3
      3609882.91     10596475.34      3607278.76     10595815.62
      3605844.61     10595275.22
#Sta/Elev= 30
  2685.6  388.11  2802.5  385.33  3101.6  365.98  3381.9  356.27  4232.4  353.87
    4257  347.18  4273.4  351.99  4308.6  354.06  4514.2  350.82  4566.5  354.64
  4744.1  353.67  4965.1  355.16  4989.5  351.21  5003.1  345.31  5005.9  344.81
  5009.1  345.31  5030.7  355.35  5067.4  354.63  5809.3  354.97  6142.4  365.78
  6167.3  372.64  6298.6  374.25  6451.6  384.38  6508.4  387.34  6538.6  392.68
  6715.3  395.72    6762  397.19  6789.1  397.13  6835.1  405.02  6904.6  405.28
#Mann= 9 ,-1 , 0
  2685.6     .05       0  4744.1     .16       0  5003.1     .07       0
  5009.1     .16       0  5067.4     .05       0  6298.6     .08       0
  6451.6     .05       0  6715.3      .1       0    6762     .05       0
#XS Ineff= 1 ,-1
 3080.24 4940.19  355.68
Permanent Ineff=
       T
Bank Sta=4965.1,5030.7
XS Rating Curve= 0 ,0
Exp/Cntr=0.3,0.1

Type RM Length L Ch R = 1 ,12152   ,1452,1452,1452
BEGIN DESCRIPTION:
Mapping XS 1cd7b3ed
END DESCRIPTION:
XS GIS Cut Line= 2
      3610880.71     10596526.97      3606095.56     10594270.03
#Sta/Elev= 30
  2519.9  398.15  2609.6  401.09  2849.8  397.29  3284.7  382.05  3418.5   374.9
  3555.2  376.76  3704.2  363.59  4000.5   352.3    4011  352.31  4223.6  351.92
  4378.2  351.14  4516.4   351.3  4623.7  354.17  4835.3  352.85  4930.9   352.8
  4966.1  353.42  4985.9  342.35  4988.6  341.85  4991.9  342.35  5006.1  349.66
  5019.9  352.13  5140.2  352.94  5912.3  351.44  6019.7  351.51  6103.5  351.99
  6701.4  356.13  7071.3  364.73    7386  381.16  7630.4  399.77  7810.6  405.67
#Mann= 17 ,-1 , 0
  2519.9     .16       0  3284.7     .05       0  4000.5     .16       0
    4011     .05       0  4223.6     .16       0  4378.2     .05       0
  4516.4     .08       0  4623.7      .1       0  4835.3     .05       0
  4930.9     .16       0  4985.9     .07       0  4991.9     .16       0
  5140.2     .05       0  5912.3     .08       0  6019.7      .1       0
  6103.5     .05       0  7630.4     .08       0
#XS Ineff= 1 ,-1
 3707.95 4563.64  353.75
Permanent Ineff=
       T
Bank Sta=4966.1,5019.9
XS Rating Curve= 0 ,0
Exp/Cntr=0.3,0.1

Type RM Length L Ch R = 1 ,10700   ,895,895,895
BEGIN DESCRIPTION:
Mapping XS 65ec0d34
END DESCRIPTION:
XS GIS Cut Line= 3
      3611206.26     10596375.07      3608873.38     10594053.03
       3607766.6     10592761.79
#Sta/Elev= 30
  2524.2  408.53  2710.6  407.15  2751.6  402.48  3100.1  386.29  3366.7  379.95
  3626.2  362.22  3709.4  358.28  3770.9  356.09  3843.7  353.12  3951.2  350.74
  4356.7   347.7  4980.5  351.11  4993.1  343.22  5004.2   340.2    5007   339.7
  5010.2   340.2  5033.1  350.27  5042.6  352.79    5085  351.32  5254.7  356.08
  5488.1  354.85  5926.4  358.47  6182.1  365.65  6466.7  369.56  6600.4  372.96
  6884.6  382.45  7089.8  379.64  7309.3  385.59  7373.6  392.66  7516.4  393.25
#Mann= 14 ,-1 , 0
  2524.2     .05       0  2710.6     .16       0  3100.1     .05       0
  3626.2     .16       0  3709.4     .08       0  3770.9     .07       0
  3843.7     .16       0  3951.2     .05       0  4980.5     .16       0
  5004.2     .07       0  5010.2     .16       0  5033.1     .05       0
  6466.7     .08       0  6600.4     .05       0
#XS Ineff= 1 ,-1
 3614.03 4971.52  352.55
Permanent Ineff=
       T
Bank Sta=4980.5,5033.1
XS Rating Curve= 0 ,0
Exp/Cntr=0.3,0.1

Type RM Length L Ch R = 1 ,9805    ,2001,2001,2001
BEGIN DESCRIPTION:
Mapping XS 01bc231b
END DESCRIPTION:
XS GIS Cut Line= 3
      3611759.65     10595886.78      3610631.19     10594335.15
      3607994.54     10592848.65
#Sta/Elev= 30
  2260.8  400.47  2387.4  402.82  2562.3  391.14  2687.1  386.63  3117.7  390.48
    3475  369.81  3685.7  358.31  3935.4  351.83  4060.2  350.54    4424  343.38
  4535.1  349.06  4723.9  348.72  4960.3  350.46  4984.8  350.78  5004.7  339.81
  5007.5  339.31  5010.7  339.81  5035.5  349.23  5090.6  349.94  5201.7  349.71
  5262.2  351.95  5312.8  351.65  5476.8  349.37  5646.1  351.44  5691.4  351.98
  5931.2  357.98  6292.3  380.68  6614.9  374.62  7150.4  385.76  7206.2  391.52
#Mann= 20 ,-1 , 0
  2260.8     .16       0  2562.3     .05       0  2687.1     .16       0
    3475     .05       0  3685.7     .12       0  3935.4     .07       0
  4060.2     .05       0    4424     .05       0  4535.1     .16       0
  4723.9     .05       0  4960.3     .16       0  5004.7     .07       0
  5010.7     .16       0  5090.6     .05       0  5201.7     .15       0
  5262.2      .1       0  5312.8     .15       0  5476.8     .05       0
  5646.1      .1       0  5691.4     .05       0
#XS Ineff= 1 ,-1
 3774.71    4948  350.61
Permanent Ineff=
       T
Bank Sta=4984.8,5035.5
XS Rating Curve= 0 ,0
Exp/Cntr=0.3,0.1

Type RM Length L Ch R = 1 ,7804    ,485,485,485
BEGIN DESCRIPTION:
MIMS CREEK 4.0
END DESCRIPTION:
XS GIS Cut Line= 3
      3612649.65     10594060.21      3611249.61     10593260.19
       3608157.2     10592794.35
#Sta/Elev= 30
  3404.2  406.33  3459.9  402.36  3496.9  398.67  3638.2  387.26  3799.4  378.41
  3939.1  365.88  4143.5   357.3  4643.1  349.17  4971.4  346.99  4987.2  338.84
    5000  338.25  5002.8  337.75    5006  338.25  5026.8  345.78  5036.9  346.57
  5091.1  347.13  5094.8  347.16  5411.1  344.57  5582.6  346.19  5613.4  350.28
  5651.6  345.94  5893.7  347.61    6014  347.25  6432.5  345.47    7019  350.97
  7241.5  355.42  7576.8  372.46  7716.8  370.57  7770.8  373.59    8144  383.84
#Mann= 11 ,-1 , 0
  3404.2     .12       0  3459.9     .16       0  3496.9     .05       0
    5000     .03       0    5006     .05       0  5091.1     .16       0
  5094.8     .05       0  5893.7     .08       0    6014     .05       0
  7576.8     .16       0  7770.8     .05       0
Bank Sta=4971.4,5036.9
XS Rating Curve= 0 ,0
Exp/Cntr=0.3,0.1

Type RM Length L Ch R = 1 ,7319    ,501,501,501
BEGIN DESCRIPTION:
MIMS CREEK 3.0
END DESCRIPTION:
XS GIS Cut Line= 3
      3612899.61     10593910.19      3611349.61     10592810.19
      3608200.59     10592349.47
#Sta/Elev= 30
  3127.1  410.61  3814.8  364.26  4052.2  352.33  4696.8  345.69    4842  345.55
  4955.2  349.52  4978.6  345.78  4984.7  346.26  5002.6   338.1  5005.4   337.6
  5008.6   338.1  5020.4  338.53  5024.7  344.95    5048  347.81  5117.3  345.87
  5394.4   345.2  6270.9  344.54  6412.3  347.47  6790.3  346.86  7018.7  357.28
  7101.3  357.45  7200.7  357.77  7301.7  363.42  7339.5  361.49  7544.2  367.65
  7645.3  372.31  7766.6  381.76  7837.4  382.89  8019.3  379.17  8210.3  384.89
#Mann= 7 ,-1 , 0
  3127.1     .05       0  5002.6     .03       0  5008.6     .05       0
  5117.3     .12       0  5394.4     .05       0  7101.3     .08       0
  7200.7     .05       0
Bank Sta=4978.6,5024.7
XS Rating Curve= 0 ,0
Exp/Cntr=0.3,0.1

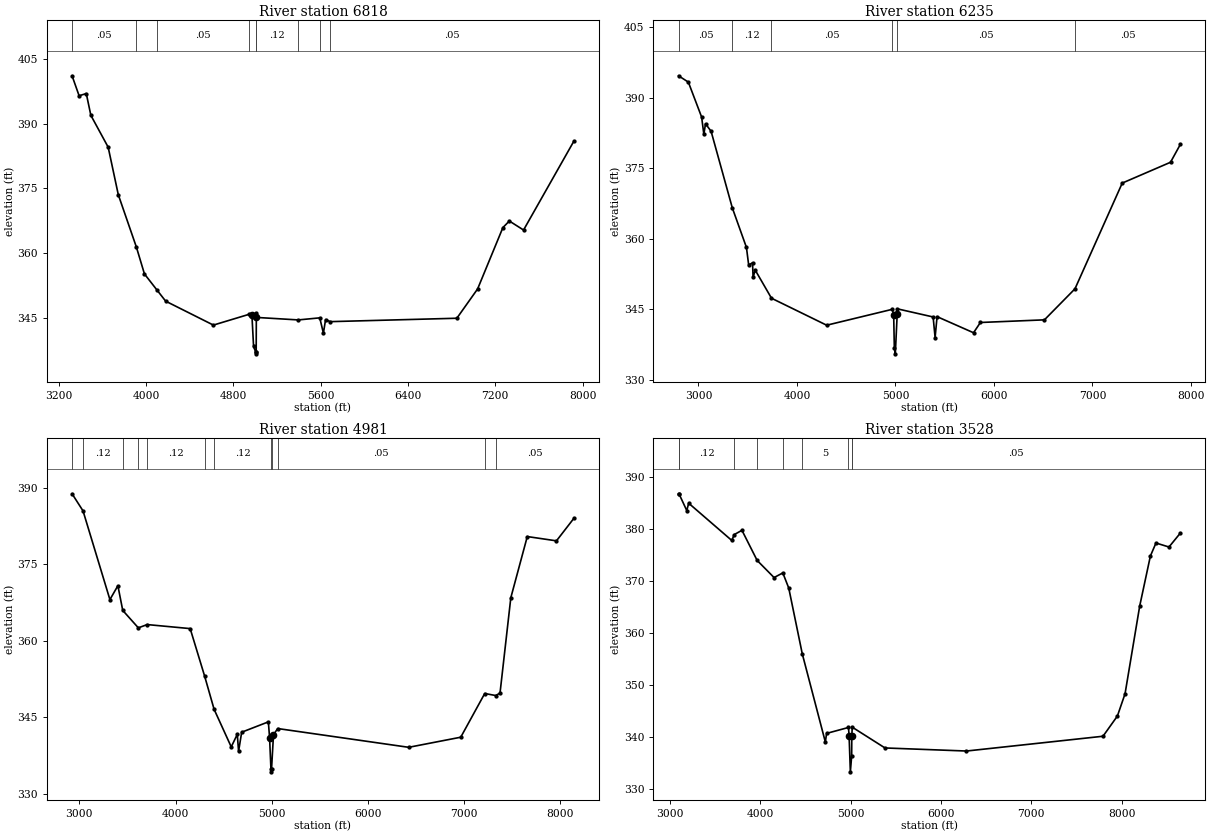
Type RM Length L Ch R = 1 ,6818    ,583,583,583
BEGIN DESCRIPTION:
MIMS CREEK 2.0
END DESCRIPTION:
XS GIS Cut Line= 3
      3612949.62      10593360.2      3611549.61     10592410.19
      3608649.61     10592210.19
#Sta/Elev= 30
  3321.3  401.13  3385.7   396.5  3451.6     397  3493.5  391.95  3652.2  384.56
  3745.1  373.52  3910.8  361.38  3984.6  355.15  4096.2  351.52  4179.2  348.83
  4616.5  343.28  4947.3  345.81  4969.8  345.52  4984.7  338.32  5002.7  337.11
  5005.5  336.61  5008.7  337.11  5010.2  346.02 5010.65  345.06  5394.6  344.48
  5591.3  344.96  5624.7  341.41  5644.7  344.56  5687.2  344.08  6847.6  344.87
    7038  351.67  7269.8  365.91  7328.7  367.43    7459  365.34  7920.1  385.95
#Mann= 9 ,-1 , 0
  3321.3     .05       0  3910.8     .08       0  4096.2     .05       0
  4947.3     .12       0  5002.7     .07       0  5008.7     .12       0
  5394.6     .05       0  5591.3     .12       0  5687.2     .05       0
Bank Sta=4969.8,5010.65
XS Rating Curve= 0 ,0
Exp/Cntr=0.3,0.1

Type RM Length L Ch R = 1 ,6235    ,1254,1254,1254
BEGIN DESCRIPTION:
Mapping XS 25646e53
END DESCRIPTION:
XS GIS Cut Line= 4
      3613516.28     10592708.11      3612149.11     10592035.38
       3611161.7     10591883.47      3608590.04     10591905.17
#Sta/Elev= 30
  2797.5  394.62  2897.2  393.27    3032  385.85  3054.5  382.19  3071.4  384.43
  3128.1  382.83  3343.2  366.58    3487  358.16  3509.5  354.43  3548.8  354.89
  3554.4  351.86  3576.9  353.32  3741.3  347.37  4301.5  341.64  4968.3  345.02
  4981.8   343.8  4988.5  336.79  4998.4  335.56 5017.43  343.98  5018.8  345.12
  5382.3  343.39  5402.3  339.03  5422.3  343.46  5792.4  340.04  5862.4  342.22
  6512.4  342.78  6822.4  349.37  7302.4  371.83  7792.4  376.25    7892  380.04
#Mann= 6 ,-1 , 0
  2797.5     .05       0  3343.2     .12       0  3741.3     .05       0
  4968.3     .07       0  5018.8     .05       0  6822.4     .05       0
Bank Sta=4981.8,5017.43
XS Rating Curve= 0 ,0
Exp/Cntr=0.3,0.1

Type RM Length L Ch R = 1 ,4981    ,1453,1453,1453
BEGIN DESCRIPTION:
Mapping XS d2847511
END DESCRIPTION:
XS GIS Cut Line= 4
      3613505.42     10592198.12      3611454.67     10591232.42
      3610792.78     10591145.62      3608557.57     10591601.34
#Sta/Elev= 30
  2924.9  388.83  3038.9  385.47  3318.2  368.08  3401.2   370.8  3451.5  365.96
  3613.6  362.54  3705.8  363.18  4152.5  362.39  4302.1  353.11  4401.2  346.56
  4579.3  339.19  4642.2  341.66  4655.6  338.32  4687.8  342.07  4965.1   344.1
  4977.8  340.99  4992.1   334.8  4994.8   334.3  4998.1   334.8 5018.46  341.59
  5062.4  342.79  6423.8  339.11  6964.7  341.09    7214  349.66  7327.7  349.27
  7372.9  349.74  7485.2  368.45  7656.3  380.44  7959.6   379.6  8140.4  384.01
#Mann= 12 ,-1 , 0
  2924.9     .05       0  3038.9     .12       0  3451.5     .05       0
  3613.6     .16       0  3705.8     .12       0  4302.1     .16       0
  4401.2     .12       0  4992.1     .07       0  4998.1     .12       0
  5062.4     .05       0    7214      .1       0  7327.7     .05       0
Bank Sta=4977.8,5018.46
XS Rating Curve= 0 ,0
Exp/Cntr=0.3,0.1

Type RM Length L Ch R = 1 ,3528    ,0,0,0
BEGIN DESCRIPTION:
MIMS CREEK 1.0
END DESCRIPTION:
XS GIS Cut Line= 4
      3613472.93     10591905.19      3611693.38     10590418.62
       3611118.3     10590396.92      3608613.21     10591286.17
#Sta/Elev= 30
  3096.3  386.79  3101.9  386.77  3187.6  383.56  3208.4  384.98  3684.7  377.83
  3714.1  378.96    3798  379.77  3966.2  373.98  4153.3  370.69  4250.3  371.58
  4315.9  368.67  4465.4  356.04  4720.7  339.09    4735  340.74    4977  341.88
  4983.6   340.3  4997.6  333.35  5012.2  336.43 5013.42  340.27  5018.7  341.93
  5380.9  337.94  6282.6  337.35  7793.1  340.19  7952.3  344.07  8037.2  348.36
  8199.6  365.25  8317.7  374.84  8379.4  377.33  8523.1  376.56  8648.8  379.23
#Mann= 9 ,-1 , 0
  3096.3     .05       0  3101.9     .12       0  3714.1     .05       0
  3966.2     .16       0  4250.3     .12       0  4465.4       5       0
    4977     .03       0 5013.42     .12       0 5013.42     .05       0
Bank Sta=4983.6,5013.42
XS Rating Curve= 0 ,0
Exp/Cntr=0.3,0.1

Chan Stop Cuts=-1
Use User Specified Reach Order=0
Composite Channel Slope=5