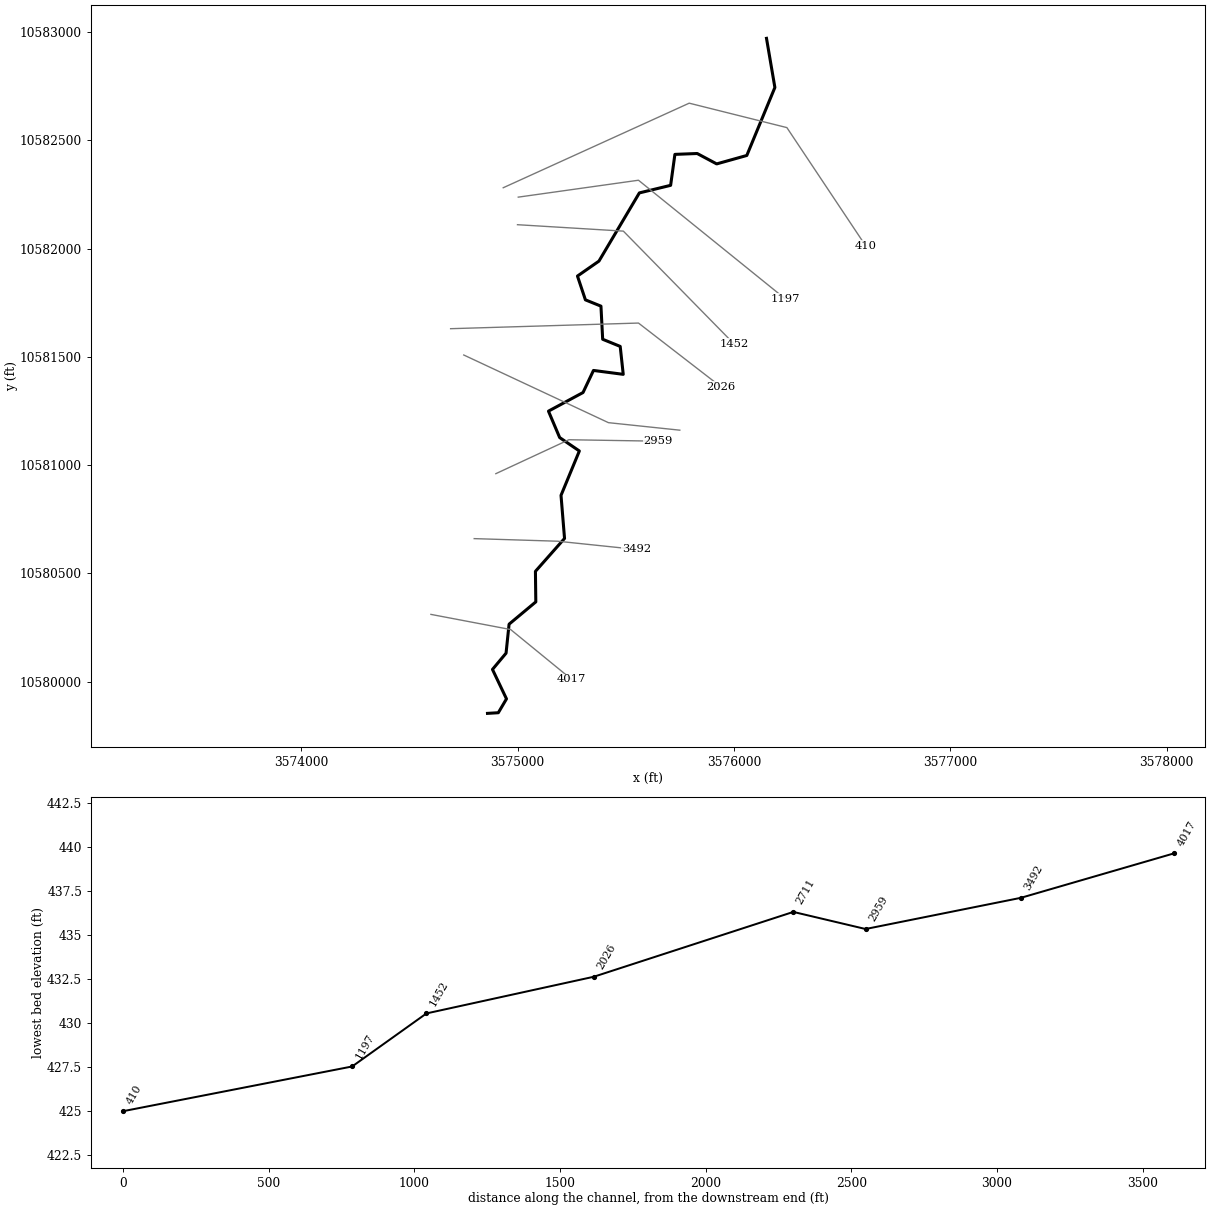
--- UNT 003 IN UKCR.prj (project) ---

Proj Title=UNT 003 IN UKCR Base Level Engineering
Current Plan=p01
Default Exp/Contr=0.3,0.1
English Units
Geom File=g01
Flow File=f01
Plan File=p01
BEGIN DESCRIPTION:
UNT 003 IN UKCR
END DESCRIPTION:

--- UNT 003 IN UKCR.p01 (plan) ---

Plan Title=Multiple Run
Short Identifier=Multiple
Geom File=g01
Flow File=f01
Subcritical Flow
K Sum by GR= 0
Std Step Tol= 0.01
Critical Tol= 0.01
Num of Std Step Trials= 20
Max Error Tol= 0.3
Flow Tol Ratio= 0.001
Split Flow NTrial= 30
Split Flow Tol= 0.02
Split Flow Ratio= 0.02
Log Output Level= 0
Friction Slope Method= 1
Unsteady Friction Slope Method= 2
Unsteady Bridges Friction Slope Method= 1
Parabolic Critical Depth
Global Vel Dist=  1 , 1 , 1
Global Log Level= 0
CheckData=True
Encroach Param= -1, 0, 0, 0
BEGIN DESCRIPTION:
Multiple Run
END DESCRIPTION:

--- UNT 003 IN UKCR.f01 (steady flow) ---

Flow Title=Multiple
Number of Profiles=7
Profile Names=10-year,25-year,50-year,1pct_min,100-year,1pct_plu,500-year
River Rch & RM= UNT 003 IN UKCR,Reach-1,4017
    1031    1419    1739    1557    2106    2847    3074
Boundary for River Rch & Prof#=UNT 003 IN UKCR,Reach-1,1
Up Type=0
Dn Type=3
Dn Slope=0.005
Boundary for River Rch & Prof#=UNT 003 IN UKCR,Reach-1,2
Up Type=0
Dn Type=3
Dn Slope=0.005
Boundary for River Rch & Prof#=UNT 003 IN UKCR,Reach-1,3
Up Type=0
Dn Type=3
Dn Slope=0.005
Boundary for River Rch & Prof#=UNT 003 IN UKCR,Reach-1,4
Up Type=0
Dn Type=3
Dn Slope=0.005
Boundary for River Rch & Prof#=UNT 003 IN UKCR,Reach-1,5
Up Type=0
Dn Type=3
Dn Slope=0.005
Boundary for River Rch & Prof#=UNT 003 IN UKCR,Reach-1,6
Up Type=0
Dn Type=3
Dn Slope=0.005
Boundary for River Rch & Prof#=UNT 003 IN UKCR,Reach-1,7
Up Type=0
Dn Type=3
Dn Slope=0.005

--- UNT 003 IN UKCR.g01 (geometry) ---

Geom Title=Existing Conditions

River Reach=UNT 003 IN UKCR,Reach-1
Reach XY= 30
      3574861.00     10579853.00      3574911.00     10579856.00
      3574948.75     10579920.00      3574884.00     10580056.00
      3574946.75     10580131.00      3574960.75     10580265.00
      3575084.25     10580368.00      3575082.50     10580509.00
      3575217.00     10580661.00      3575200.75     10580860.00
      3575285.50     10581065.00      3575194.50     10581127.00
      3575142.75     10581249.00      3575302.50     10581335.00
      3575350.75     10581437.00      3575488.25     10581419.00
      3575474.25     10581548.00      3575393.25     10581581.00
      3575385.25     10581734.00      3575313.50     10581763.00
      3575276.75     10581873.00      3575376.00     10581942.00
      3575562.75     10582257.00      3575707.25     10582292.00
      3575727.00     10582435.00      3575830.00     10582439.00
      3575920.00     10582391.00      3576059.25     10582430.00
      3576189.00     10582744.00      3576150.25     10582971.00

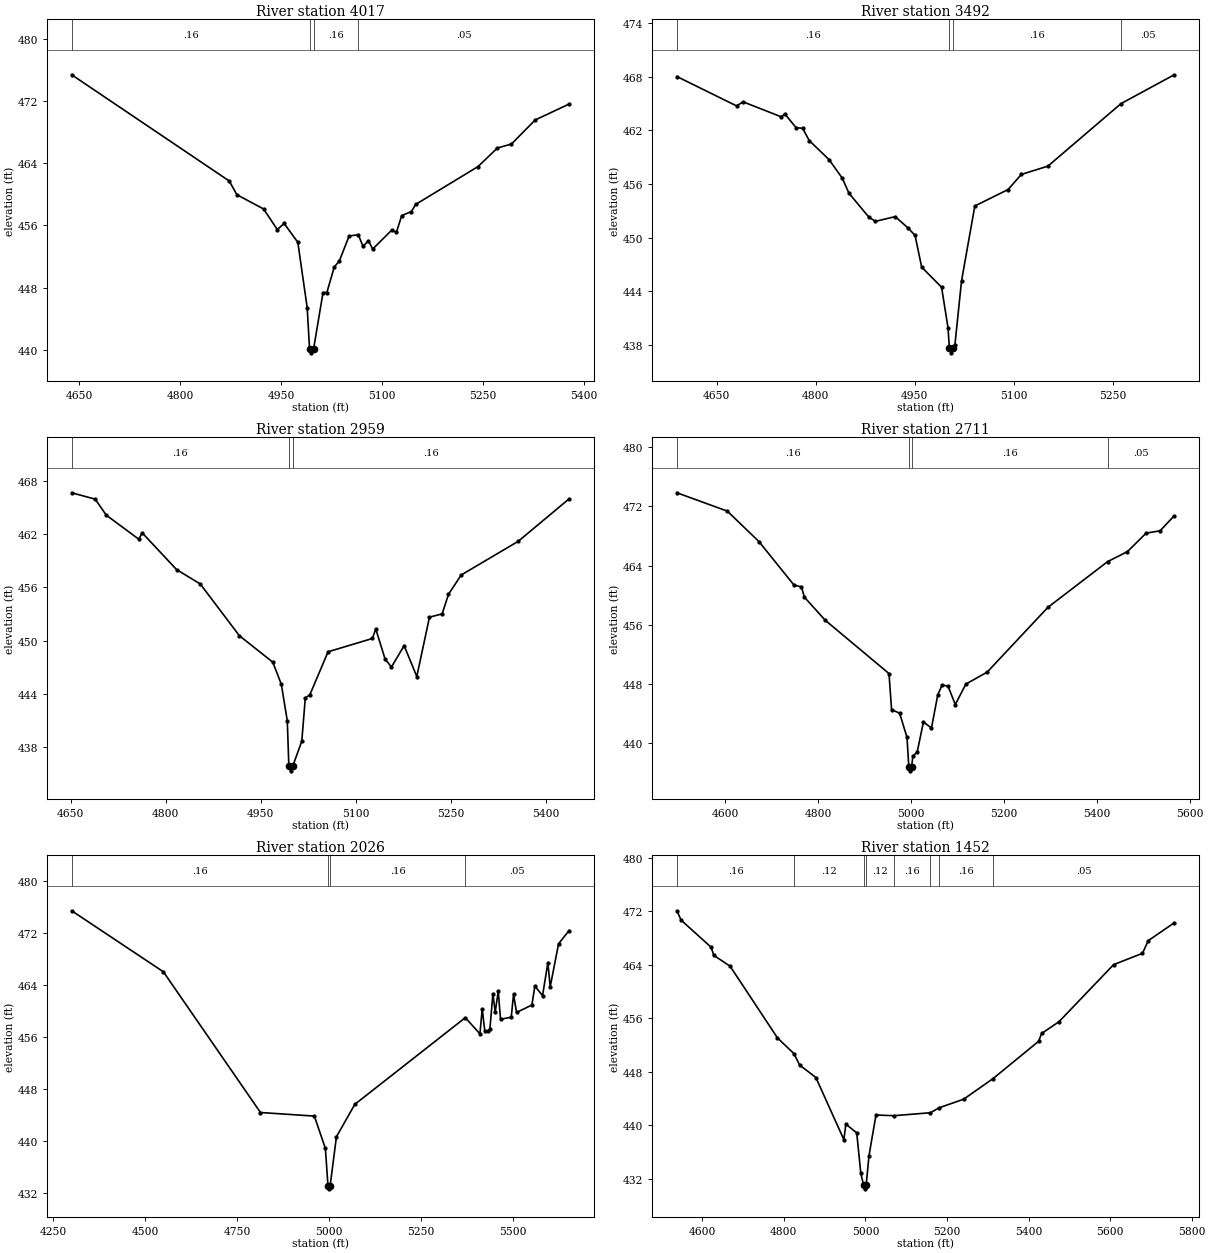
Type RM Length L Ch R = 1,4017,525,525,525
BEGIN DESCRIPTION:
UNT 003 IN UKCR 7.0
END DESCRIPTION:
XS GIS Cut Line= 3
      3574599.60     10580310.19      3574968.02     10580240.22
      3575249.60     10580010.20
#Sta/Elev= 30
  4639.0  475.34  4873.1  461.69  4884.3  459.94  4924.0  458.10  4944.4  455.46
  4954.6  456.24  4974.9  453.81  4988.8  445.41  4992.3  440.12  4995.0  439.62
  4998.3  440.12  5012.3  447.36  5018.0  447.36  5029.0  450.65  5036.6  451.43
  5051.0  454.62  5064.6  454.80  5071.8  453.29  5079.7  454.04  5086.1  452.95
  5114.9  455.43  5121.3  455.09  5129.2  457.25  5143.6  457.77  5150.0  458.69
  5242.6  463.55  5271.4  465.94  5292.2  466.44  5327.4  469.53  5377.6  471.57
#Mann=4,-1,0
  4639.0    0.16       0  4992.3    0.07       0  4998.3    0.16       0
  5064.6    0.05       0
Bank Sta=4992.3,4998.3
Exp/Cntr=0.3,0.1

Type RM Length L Ch R = 1,3492,533,533,533
BEGIN DESCRIPTION:
UNT 003 IN UKCR 6.0
END DESCRIPTION:
XS GIS Cut Line= 3
      3574799.56     10580660.19      3575185.03     10580648.21
      3575549.60     10580610.19
#Sta/Elev= 30
  4590.1  468.01  4680.2  464.73  4690.2  465.18  4748.1  463.50  4753.2  463.84
  4770.2  462.30  4780.2  462.22  4790.2  460.85  4820.3  458.71  4840.3  456.63
  4850.3  454.96  4880.3  452.29  4890.3  451.81  4920.3  452.34  4940.3  451.03
  4950.3  450.23  4960.3  446.69  4990.4  444.44  5000.2  439.88  5002.2  437.60
  5004.9  437.10  5008.2  437.60  5010.5  437.94  5020.6  445.15  5040.7  453.53
  5091.0  455.37  5111.1  457.06  5151.3  457.99  5261.8  464.98  5342.3  468.21
#Mann=4,-1,0
  4590.1    0.16       0  5002.2    0.07       0  5008.2    0.16       0
  5261.8    0.05       0
Bank Sta=5002.2,5008.2
Exp/Cntr=0.3,0.1

Type RM Length L Ch R = 1,2959,248,248,248
BEGIN DESCRIPTION:
UNT 003 IN UKCR 5.0
END DESCRIPTION:
XS GIS Cut Line= 3
      3574899.63     10580960.20      3575237.12     10581116.96
      3575649.64     10581110.19
#Sta/Elev= 30
  4651.8  466.67  4688.9  465.95  4706.3  464.15  4757.6  461.44  4763.1  462.15
  4817.2  458.02  4854.7  456.39  4916.4  450.56  4969.1  447.58  4982.6  445.09
  4992.0  440.98  4994.5  435.83  4997.3  435.33  5000.5  435.83  5014.9  438.67
  5020.4  443.52  5027.7  443.92  5056.4  448.75  5126.4  450.25  5131.6  451.33
  5146.4  447.92  5156.4  447.03  5176.4  449.44  5196.4  445.96  5216.4  452.65
  5236.4  453.02  5246.4  455.22  5266.4  457.40  5356.5  461.20  5436.5  465.97
#Mann=3,-1,0
  4651.8    0.16       0  4994.5    0.07       0  5000.5    0.16       0
Bank Sta=4994.5,5000.5
Exp/Cntr=0.3,0.1

Type RM Length L Ch R = 1,2711,685,685,685
BEGIN DESCRIPTION:
UNT 003 IN UKCR 4.0
END DESCRIPTION:
XS GIS Cut Line= 3
      3574751.37     10581508.33      3575419.80     10581195.82
      3575749.70     10581161.09
#Sta/Elev= 30
  4496.7  473.83  4605.1  471.35  4673.1  467.24  4748.6  461.36  4764.5  461.13
  4770.7  459.75  4815.7  456.62  4952.8  449.43  4958.4  444.55  4975.6  444.09
  4991.5  440.83  4995.5  436.80  4998.2  436.30  5001.5  436.80  5004.0  438.24
  5013.6  438.88  5026.9  442.89  5044.2  442.08  5057.7  446.55  5067.0  447.88
  5079.8  447.73  5095.4  445.25  5118.2  448.01  5163.9  449.62  5294.7  458.37
  5422.9  464.53  5465.7  465.89  5505.9  468.38  5536.0  468.70  5566.3  470.72
#Mann=4,-1,0
  4496.7    0.16       0  4995.5    0.07       0  5001.5    0.16       0
  5422.9    0.05       0
Bank Sta=4995.5,5001.5
Exp/Cntr=0.3,0.1

Type RM Length L Ch R = 1,2026,574,574,574
BEGIN DESCRIPTION:
UNT 003 IN UKCR 3.0
END DESCRIPTION:
XS GIS Cut Line= 3
      3574690.62     10581629.85      3575558.69     10581655.89
      3575940.60     10581360.78
#Sta/Elev= 30
  4301.0  475.46  4550.1  466.06  4813.9  444.38  4960.3  443.83  4990.3  438.85
  4997.3  433.12  5000.1  432.62  5003.3  433.12  5020.3  440.64  5070.3  445.64
  5370.5  458.99  5410.2  456.50  5416.5  460.35  5423.4  456.95  5431.0  456.89
  5437.3  457.21  5445.5  462.66  5451.8  459.86  5460.0  463.04  5466.3  458.74
  5495.3  459.07  5501.6  462.58  5509.8  459.80  5551.4  460.94  5559.6  463.87
  5580.4  462.38  5594.9  467.46  5601.2  463.74  5623.9  470.37  5652.1  472.39
#Mann=4,-1,0
  4301.0    0.16       0  4997.3    0.07       0  5003.3    0.16       0
  5370.5    0.05       0
Bank Sta=4997.3,5003.3
Exp/Cntr=0.3,0.1

Type RM Length L Ch R = 1,1452,255,255,255
BEGIN DESCRIPTION:
UNT 003 IN UKCR 2.0
END DESCRIPTION:
XS GIS Cut Line= 3
      3574999.61     10582110.19      3575488.85     10582080.50
      3575999.58     10581560.22
#Sta/Elev= 30
  4538.0  472.05  4548.0  470.66  4621.9  466.60  4628.2  465.40  4668.2  463.78
  4784.5  453.07  4825.1  450.71  4838.6  449.03  4878.6  447.16  4947.2  437.89
  4952.2  440.20  4978.8  438.89  4988.8  432.86  4995.8  431.04  4998.6  430.54
  5001.8  431.04  5008.9  435.51  5026.0  441.56  5069.8  441.46  5159.5  441.90
  5180.8  442.64  5241.0  443.92  5313.1  447.00  5424.9  452.57  5432.0  453.73
  5474.4  455.47  5608.7  464.01  5679.5  465.70  5693.6  467.59  5757.2  470.25
#Mann=8,-1,0
  4538.0    0.16       0  4825.1    0.12       0  4995.8    0.07       0
  5001.8    0.12       0  5069.8    0.16       0  5159.5    0.12       0
  5180.8    0.16       0  5313.1    0.05       0
Bank Sta=4995.8,5001.8
Exp/Cntr=0.3,0.1

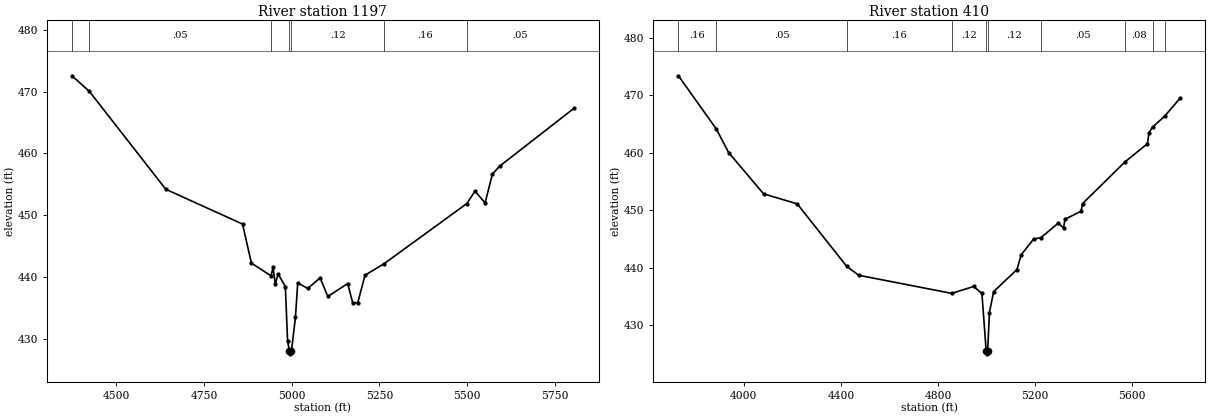
Type RM Length L Ch R = 1,1197,787,787,787
BEGIN DESCRIPTION:
Mapping XS 64d0d683
END DESCRIPTION:
XS GIS Cut Line= 3
      3575003.13     10582237.49      3575558.69     10582315.61
      3576235.17     10581769.23
#Sta/Elev= 30
  4373.4  472.59  4423.1  470.06  4640.8  454.20  4859.6  448.56  4884.9  442.24
  4941.1  440.16  4946.5  441.55  4953.0  438.78  4960.9  440.50  4981.7  438.40
  4988.1  429.55  4993.1  428.03  4995.9  427.53  4999.1  428.03  5010.5  433.46
  5016.9  439.03  5045.7  438.13  5080.9  439.84  5102.7  436.83  5159.2  438.91
  5173.6  435.83  5188.0  435.81  5208.8  440.28  5262.5  442.11  5499.1  451.89
  5522.2  453.90  5551.0  451.99  5571.8  456.66  5592.6  457.95  5804.0  467.30
#Mann=7,-1,0
  4373.4    0.16       0  4423.1    0.05       0  4941.1    0.12       0
  4993.1    0.07       0  4999.1    0.12       0  5262.5    0.16       0
  5499.1    0.05       0
Bank Sta=4993.1,4999.1
Exp/Cntr=0.3,0.1

Type RM Length L Ch R = 1,410,0,0,0
BEGIN DESCRIPTION:
UNT 003 IN UKCR 1.0
END DESCRIPTION:
XS GIS Cut Line= 4
      3574933.73     10582280.91      3575793.07     10582671.52
      3576244.46     10582558.67      3576609.04     10582011.79
#Sta/Elev= 30
  3731.2  473.37  3887.6  464.09  3937.9  460.01  4081.8  452.83  4220.2  451.09
  4423.8  440.23  4473.6  438.66  4856.6  435.51  4946.7  436.71  4980.8  435.49
  4998.4  425.49  5001.2  424.99  5004.4  425.49  5011.7  432.18  5029.1  435.81
  5125.1  439.66  5142.7  442.23  5193.7  444.97  5223.8  445.21  5294.8  447.71
  5316.9  446.91  5322.9  448.41  5389.0  449.80  5395.0  451.12  5568.4  458.33
  5662.5  461.56  5668.5  463.44  5683.3  464.44  5732.8  466.32  5797.7  469.51
#Mann=10,-1,0
  3731.2    0.16       0  3887.6    0.05       0  4423.8    0.16       0
  4856.6    0.12       0  4998.4    0.07       0  5004.4    0.12       0
  5223.8    0.05       0  5568.4    0.08       0  5683.3    0.05       0
  5732.8     0.1       0
Bank Sta=4998.4,5004.4
Exp/Cntr=0.3,0.1

Chan Stop Cuts=-1