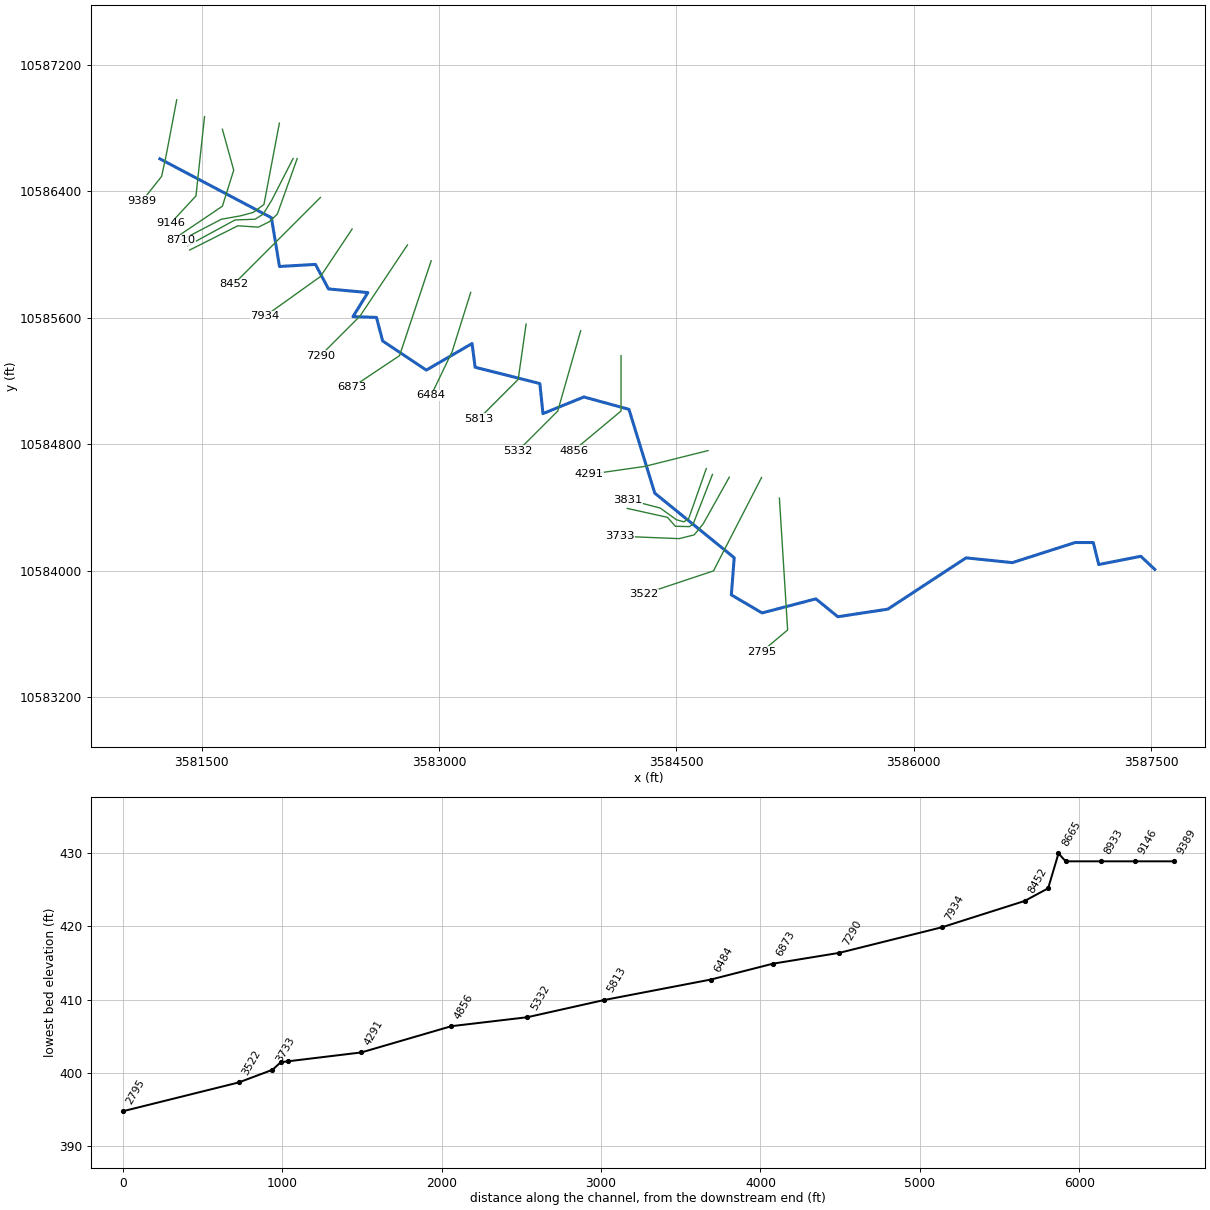
--- UNT 006 IN UKCR.prj (project) ---

Proj Title=UNT 006 IN UKCR Base Level Engineering
Current Plan=p01
Default Exp/Contr=0.3,0.1
English Units
Geom File=g01
Flow File=f01
Plan File=p01
BEGIN DESCRIPTION:
UNT 006 IN UKCR
END DESCRIPTION:

--- UNT 006 IN UKCR.p01 (plan) ---

Plan Title=Multiple Run
Short Identifier=Multiple
Geom File=g01
Flow File=f01
Subcritical Flow
K Sum by GR= 0
Std Step Tol= 0.01
Critical Tol= 0.01
Num of Std Step Trials= 20
Max Error Tol= 0.3
Flow Tol Ratio= 0.001
Split Flow NTrial= 30
Split Flow Tol= 0.02
Split Flow Ratio= 0.02
Log Output Level= 0
Friction Slope Method= 1
Unsteady Friction Slope Method= 2
Unsteady Bridges Friction Slope Method= 1
Parabolic Critical Depth
Global Vel Dist=  1 , 1 , 1
Global Log Level= 0
CheckData=True
Encroach Param= -1, 0, 0, 0
BEGIN DESCRIPTION:
Multiple Run
END DESCRIPTION:

--- UNT 006 IN UKCR.f01 (steady flow) ---

Flow Title=Multiple
Number of Profiles=7
Profile Names=10-year,25-year,50-year,1pct_min,100-year,1pct_plu,500-year
River Rch & RM= UNT 006 IN UKCR,Reach-1,9389
     872    1180    1430    1266    1712    2315    2443
Boundary for River Rch & Prof#=UNT 006 IN UKCR,Reach-1,1
Up Type=0
Dn Type=3
Dn Slope=0.005
Boundary for River Rch & Prof#=UNT 006 IN UKCR,Reach-1,2
Up Type=0
Dn Type=3
Dn Slope=0.005
Boundary for River Rch & Prof#=UNT 006 IN UKCR,Reach-1,3
Up Type=0
Dn Type=3
Dn Slope=0.005
Boundary for River Rch & Prof#=UNT 006 IN UKCR,Reach-1,4
Up Type=0
Dn Type=3
Dn Slope=0.005
Boundary for River Rch & Prof#=UNT 006 IN UKCR,Reach-1,5
Up Type=0
Dn Type=3
Dn Slope=0.005
Boundary for River Rch & Prof#=UNT 006 IN UKCR,Reach-1,6
Up Type=0
Dn Type=3
Dn Slope=0.005
Boundary for River Rch & Prof#=UNT 006 IN UKCR,Reach-1,7
Up Type=0
Dn Type=3
Dn Slope=0.005

--- UNT 006 IN UKCR.g01 (geometry) ---

Geom Title=Existing Conditions

River Reach=UNT 006 IN UKCR,Reach-1
Reach XY= 30
      3581234.89     10586604.37      3581939.75     10586232.00
      3581990.75     10585924.00      3582218.25     10585937.00
      3582300.50     10585782.00      3582549.50     10585759.00
      3582455.50     10585607.00      3582603.75     10585602.00
      3582643.00     10585453.00      3582918.75     10585269.00
      3583208.25     10585437.00      3583227.25     10585287.00
      3583636.50     10585184.00      3583656.25     10584994.00
      3583915.00     10585099.00      3584199.75     10585021.00
      3584363.00     10584491.00      3584865.00     10584083.00
      3584847.00     10583848.00      3585041.25     10583734.00
      3585381.25     10583823.00      3585520.00     10583710.00
      3585836.25     10583758.00      3586330.50     10584082.00
      3586623.50     10584052.00      3587020.00     10584179.00
      3587135.00     10584179.00      3587169.25     10584040.00
      3587435.25     10584092.00      3587523.50     10584009.00

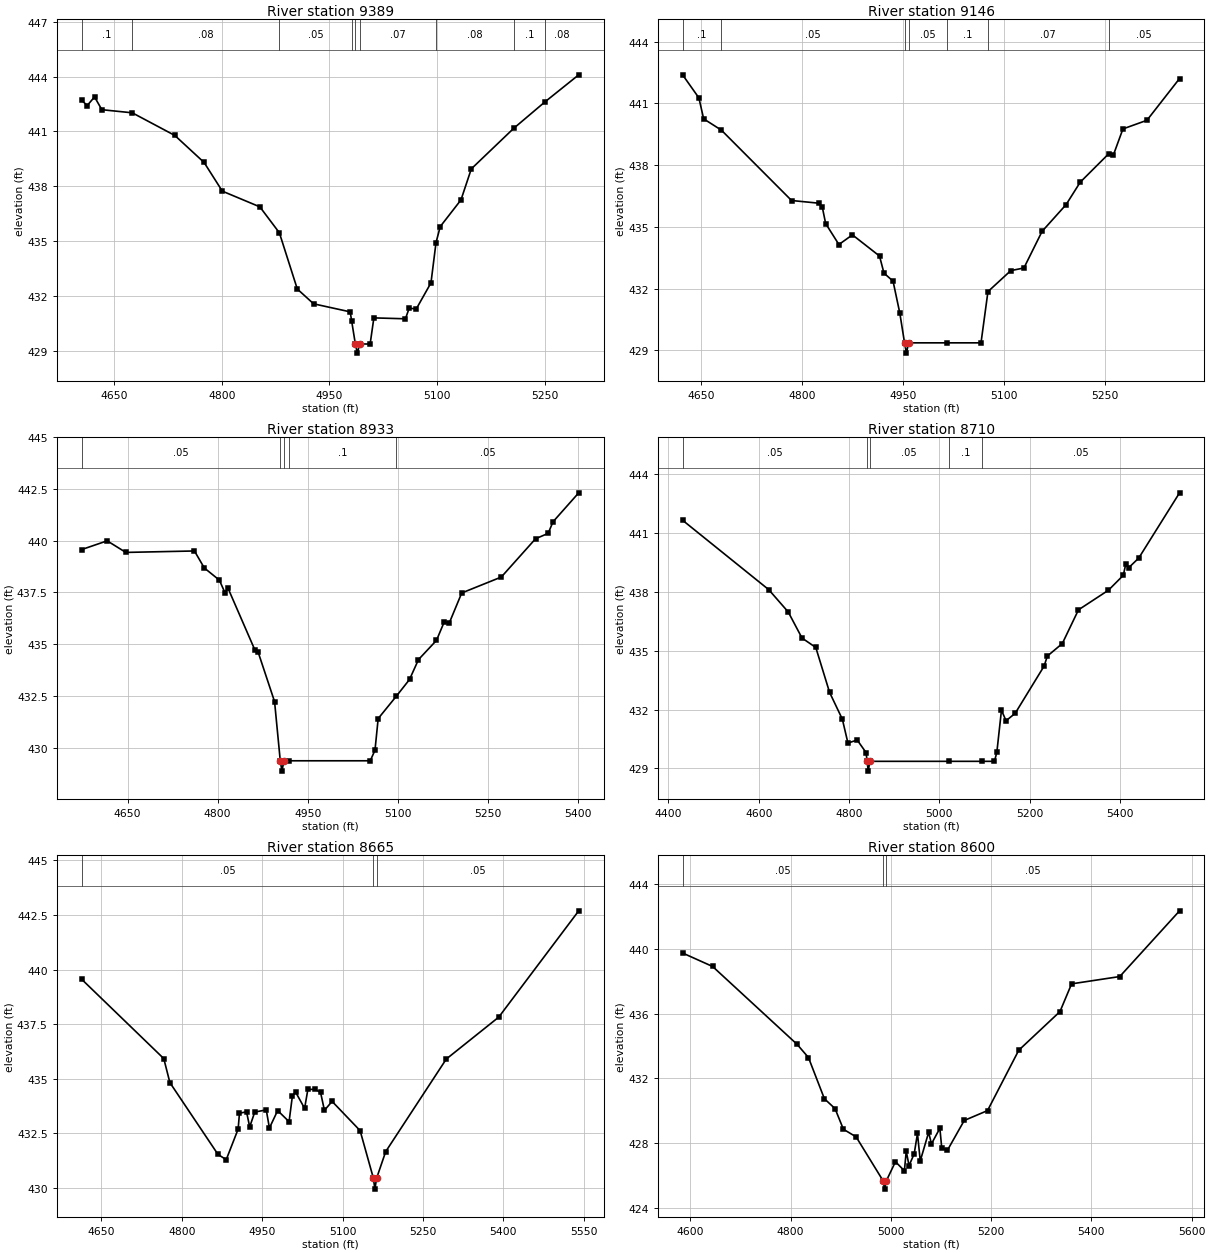
Type RM Length L Ch R = 1,9389,243,243,243
BEGIN DESCRIPTION:
UNT 006 IN UKCR 11.0
END DESCRIPTION:
XS GIS Cut Line= 4
      3581341.23     10586977.65      3581273.95     10586623.90
      3581245.74     10586493.69      3581122.04     10586337.44
#Sta/Elev= 30
  4604.9  442.70  4612.5  442.42  4622.7  442.89  4632.9  442.19  4675.3  442.02
  4734.6  440.78  4775.4  439.30  4800.8  437.73  4853.1  436.87  4880.3  435.45
  4905.3  432.37  4928.0  431.56  4979.0  431.12  4981.0  430.63  4986.2  429.36
  4989.0  428.86  4992.2  429.36  5006.8  429.36  5012.0  430.79  5056.0  430.74
  5061.2  431.32  5071.1  431.28  5091.6  432.71  5098.6  434.91  5104.5  435.79
  5133.4  437.25  5147.8  438.95  5206.9  441.17  5250.5  442.62  5297.5  444.10
#Mann=9,-1,0
  4604.9     0.1       0  4675.3    0.08       0  4880.3    0.05       0
  4981.0    0.07       0  4986.2    0.07       0  4992.2    0.07       0
  5098.6    0.08       0  5206.9     0.1       0  5250.5    0.08       0
Bank Sta=4986.2,4992.2
Exp/Cntr=0.3,0.1

Type RM Length L Ch R = 1,9146,213,213,213
BEGIN DESCRIPTION:
Mapping XS 087b823f
END DESCRIPTION:
XS GIS Cut Line= 3
      3581517.00     10586871.27      3581462.75     10586369.99
      3581303.38     10586197.70
#Sta/Elev= 30
  4621.9  442.39  4646.1  441.27  4653.2  440.25  4679.6  439.70  4783.9  436.28
  4824.2  436.15  4829.6  435.96  4834.6  435.16  4854.3  434.14  4874.4  434.61
  4914.7  433.58  4921.3  432.75  4934.8  432.36  4944.9  430.80  4951.9  429.36
  4954.7  428.86  4957.9  429.36  5014.6  429.36  5065.6  429.36  5075.9  431.85
  5109.8  432.87  5129.4  433.00  5156.4  434.78  5192.1  436.08  5213.1  437.17
  5255.4  438.55  5262.4  438.49  5276.6  439.76  5312.3  440.18  5360.8  442.21
#Mann=7,-1,0
  4621.9     0.1       0  4679.6    0.05       0  4951.9   0.035       0
  4957.9    0.05       0  5014.6     0.1       0  5075.9    0.07       0
  5255.4    0.05       0
Bank Sta=4951.9,4957.9
Exp/Cntr=0.3,0.1

Type RM Length L Ch R = 1,8933,223,223,223
BEGIN DESCRIPTION:
Mapping XS 07706409
END DESCRIPTION:
XS GIS Cut Line= 4
      3581629.86     10586790.97      3581701.47     10586532.76
      3581629.85     10586304.89      3581364.11     10586125.57
#Sta/Elev= 30
  4573.8  439.57  4616.1  439.99  4647.2  439.43  4761.4  439.50  4777.8  438.68
  4802.9  438.09  4812.1  437.49  4817.3  437.70  4862.4  434.69  4867.6  434.60
  4894.8  432.22  4904.3  429.36  4907.1  428.86  4910.3  429.36  4918.4  429.36
  5054.1  429.36  5062.0  429.87  5067.3  431.40  5097.8  432.49  5119.5  433.29
  5134.4  434.25  5164.4  435.18  5177.4  436.08  5185.4  436.00  5206.4  437.47
  5272.3  438.24  5329.3  440.09  5350.3  440.35  5358.4  440.91  5401.2  442.31
#Mann=5,-1,0
  4573.8    0.05       0  4904.3    0.07       0  4910.3    0.05       0
  4918.4     0.1       0  5097.8    0.05       0
Bank Sta=4904.3,4910.3
Exp/Cntr=0.3,0.1

Type RM Length L Ch R = 1,8710,45,45,45
BEGIN DESCRIPTION:
Mapping XS 1d93535c
END DESCRIPTION:
XS GIS Cut Line= 6
      3581990.10     10586830.08      3581892.44     10586315.74
      3581825.17     10586265.83      3581744.87     10586244.13
      3581623.34     10586222.43      3581369.42     10586090.04
#Sta/Elev= 30
  4431.4  441.66  4622.1  438.12  4665.3  436.98  4695.8  435.65  4726.3  435.17
  4756.8  432.88  4785.1  431.51  4797.5  430.29  4817.9  430.45  4837.8  429.80
  4839.8  429.36  4842.6  428.86  4845.8  429.36  5020.7  429.36  5095.0  429.36
  5121.9  429.36  5127.2  429.83  5137.4  431.97  5147.5  431.43  5167.8  431.81
  5231.8  434.22  5239.0  434.73  5272.1  435.37  5307.9  437.09  5374.2  438.09
  5407.1  438.85  5412.7  439.43  5418.7  439.23  5441.3  439.73  5531.7  443.06
#Mann=5,-1,0
  4431.4    0.05       0  4839.8   0.035       0  4845.8    0.05       0
  5020.7     0.1       0  5095.0    0.05       0
Bank Sta=4839.8,4845.8
Exp/Cntr=0.3,0.1

Type RM Length L Ch R = 1,8665,65,65,65
BEGIN DESCRIPTION:
Mapping XS ad0796e1
END DESCRIPTION:
XS GIS Cut Line= 6
      3582076.90     10586606.55      3581942.35     10586343.95
      3581888.10     10586254.98      3581836.02     10586222.43
      3581710.15     10586218.09      3581410.71     10586055.35
#Sta/Elev= 30
  4613.2  439.55  4766.3  435.92  4777.7  434.82  4867.5  431.53  4882.9  431.29
  4905.1  432.69  4907.6  433.42  4920.8  433.48  4926.7  432.79  4936.1  433.47
  4957.6  433.57  4963.5  432.74  4978.9  433.54  5000.2  433.03  5006.4  434.21
  5012.3  434.39  5029.2  433.64  5035.3  434.51  5048.2  434.51  5058.9  434.38
  5066.2  433.55  5080.5  433.96  5132.8  432.62  5157.6  430.44  5160.4  429.94
  5163.6  430.44  5180.6  431.66  5293.7  435.90  5391.6  437.82  5540.9  442.69
#Mann=3,-1,0
  4613.2    0.05       0  5157.6    0.03       0  5163.6    0.05       0
Bank Sta=5157.6,5163.6
Exp/Cntr=0.3,0.1

Type RM Length L Ch R = 1,8600,148,148,148
BEGIN DESCRIPTION:
Mapping XS fe0943c6
END DESCRIPTION:
XS GIS Cut Line= 6
      3582102.95     10586606.55      3581977.08     10586254.98
      3581927.16     10586207.23      3581857.72     10586172.51
      3581727.51     10586181.19      3581423.07     10586027.89
#Sta/Elev= 30
  4584.4  439.73  4644.3  438.90  4812.9  434.10  4835.5  433.29  4867.3  430.75
  4888.6  430.14  4905.2  428.87  4930.6  428.40  4984.7  425.68  4987.4  425.18
  4990.7  425.68  5009.1  426.87  5026.9  426.31  5030.6  427.51  5036.2  426.63
  5046.5  427.36  5053.0  428.61  5058.6  426.92  5075.3  428.68  5080.9  427.97
  5097.7  428.93  5101.5  427.70  5112.7  427.57  5146.3  429.41  5192.8  430.02
  5255.1  433.74  5337.3  436.12  5360.5  437.83  5456.6  438.28  5575.9  442.33
#Mann=3,-1,0
  4584.4    0.05       0  4984.7    0.03       0  4990.7    0.05       0
Bank Sta=4984.7,4990.7
Exp/Cntr=0.3,0.1

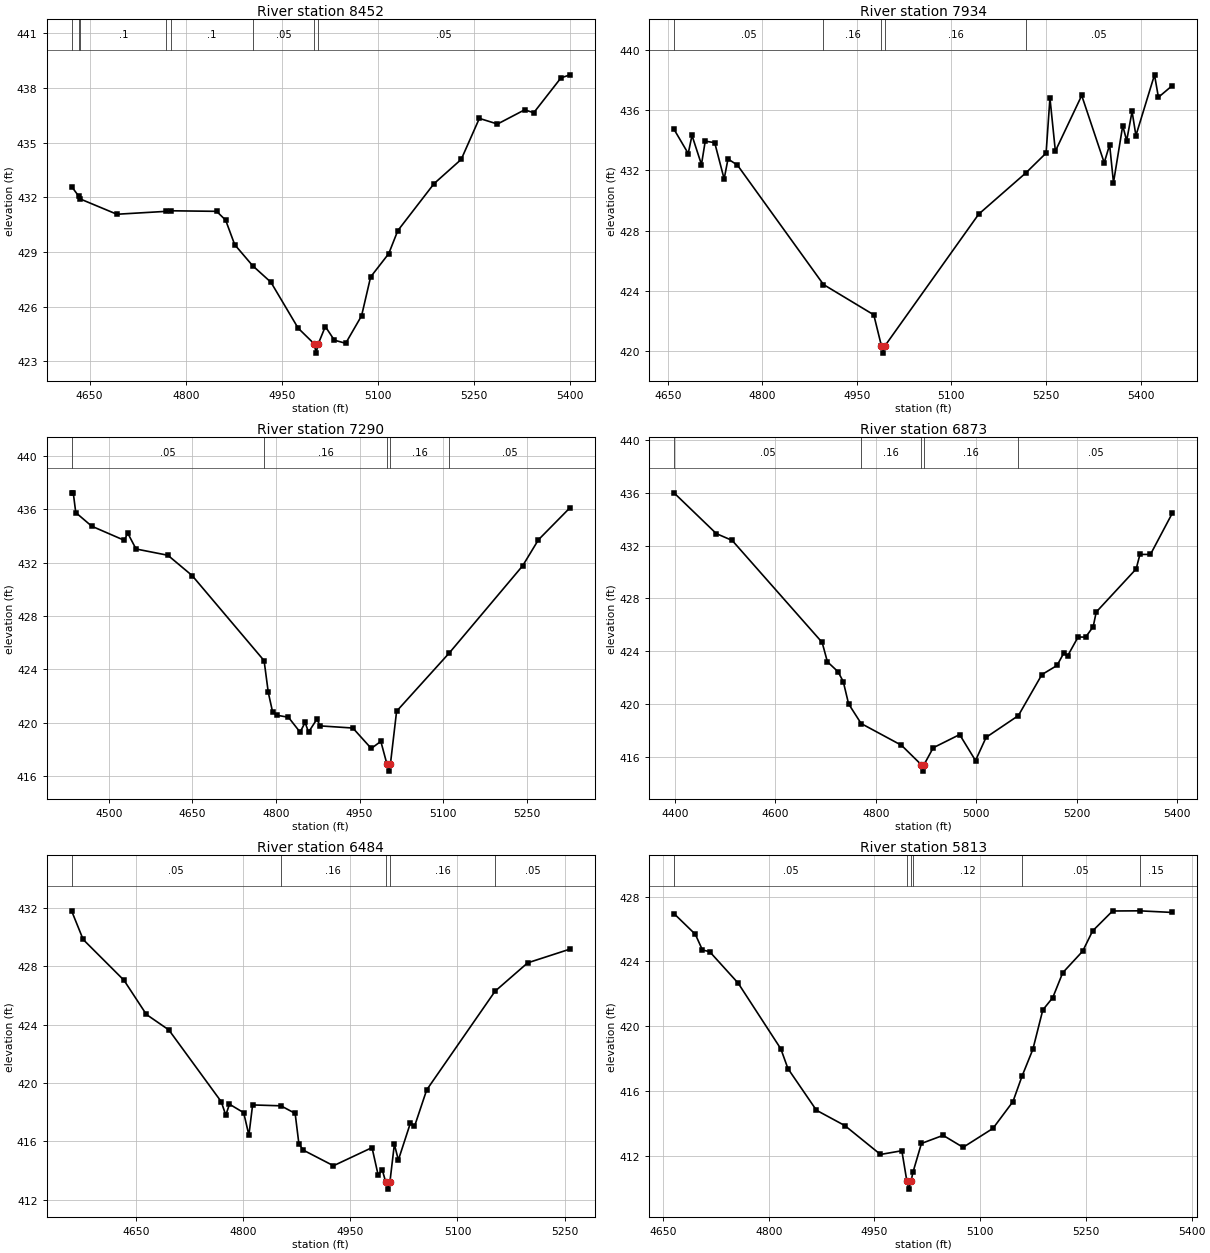
Type RM Length L Ch R = 1,8452,518,518,518
BEGIN DESCRIPTION:
UNT 006 IN UKCR 10.0
END DESCRIPTION:
XS GIS Cut Line= 3
      3582249.62     10586360.20      3581949.61     10586060.19
      3581699.63     10585810.21
#Sta/Elev= 30
  4621.8  432.59  4633.2  432.05  4635.2  431.91  4692.5  431.07  4769.8  431.23
  4777.5  431.26  4848.1  431.23  4862.2  430.75  4876.4  429.40  4904.3  428.25
  4932.9  427.34  4975.4  424.82  5000.7  423.95  5003.4  423.45  5006.7  423.95
  5017.8  424.91  5031.9  424.16  5049.6  423.99  5074.4  425.50  5088.5  427.63
  5116.8  428.91  5130.9  430.17  5187.5  432.75  5229.9  434.08  5258.2  436.33
  5286.5  436.02  5328.9  436.80  5343.1  436.64  5385.5  438.55  5399.6  438.72
#Mann=8,-1,0
  4621.8    0.05       0  4633.2    0.08       0  4635.2     0.1       0
  4769.8    0.08       0  4777.5     0.1       0  4904.3    0.05       0
  5000.7    0.03       0  5006.7    0.05       0
Bank Sta=5000.7,5006.7
Exp/Cntr=0.3,0.1

Type RM Length L Ch R = 1,7934,644,644,644
BEGIN DESCRIPTION:
UNT 006 IN UKCR 9.0
END DESCRIPTION:
XS GIS Cut Line= 3
      3582449.62     10586160.21      3582249.61     10585860.19
      3581899.60     10585610.19
#Sta/Elev= 30
  4659.8  434.72  4682.4  433.11  4688.4  434.31  4703.4  432.38  4709.4  433.93
  4724.4  433.83  4739.4  431.42  4745.5  432.75  4760.5  432.34  4897.0  424.42
  4976.8  422.41  4988.8  420.37  4991.6  419.87  4994.8  420.37  5143.3  429.09
  5218.5  431.84  5250.2  433.14  5256.3  436.79  5264.9  433.27  5306.7  436.96
  5342.4  432.50  5351.0  433.69  5357.1  431.18  5371.8  434.96  5378.0  433.96
  5386.6  435.90  5392.7  434.30  5422.2  438.33  5428.4  436.84  5450.5  437.62
#Mann=5,-1,0
  4659.8    0.05       0  4897.0    0.16       0  4988.8    0.07       0
  4994.8    0.16       0  5218.5    0.05       0
Bank Sta=4988.8,4994.8
Exp/Cntr=0.3,0.1

Type RM Length L Ch R = 1,7290,417,417,417
BEGIN DESCRIPTION:
UNT 006 IN UKCR 8.0
END DESCRIPTION:
XS GIS Cut Line= 3
      3582799.61     10586060.19      3582499.61     10585610.19
      3582249.60     10585360.18
#Sta/Elev= 30
  4433.1  437.24  4436.1  437.24  4440.6  435.76  4469.2  434.74  4527.7  433.68
  4533.8  434.22  4548.8  433.03  4605.9  432.56  4649.4  431.04  4778.6  424.66
  4786.1  422.28  4793.7  420.84  4801.2  420.57  4822.2  420.42  4843.2  419.30
  4852.2  420.03  4858.3  419.30  4873.3  420.27  4879.3  419.77  4937.9  419.61
  4970.9  418.08  4988.1  418.61  4999.2  416.88  5002.0  416.38  5005.2  416.88
  5016.4  420.87  5111.2  425.25  5242.6  431.77  5270.9  433.72  5327.5  436.12
#Mann=5,-1,0
  4433.1    0.05       0  4778.6    0.16       0  4999.2    0.07       0
  5005.2    0.16       0  5111.2    0.05       0
Bank Sta=4999.2,5005.2
Exp/Cntr=0.3,0.1

Type RM Length L Ch R = 1,6873,389,389,389
BEGIN DESCRIPTION:
UNT 006 IN UKCR 7.0
END DESCRIPTION:
XS GIS Cut Line= 3
      3582949.61     10585960.19      3582749.61     10585360.19
      3582449.62     10585160.20
#Sta/Elev= 30
  4397.9  436.00  4482.2  432.91  4513.9  432.39  4693.1  424.66  4703.6  423.19
  4724.7  422.44  4735.2  421.69  4745.8  420.00  4770.8  418.51  4851.2  416.86
  4890.3  415.40  4893.1  414.90  4896.3  415.40  4914.4  416.67  4967.1  417.67
  4998.7  415.70  5019.8  417.46  5084.1  419.11  5131.0  422.22  5161.1  422.91
  5174.6  423.85  5182.1  423.63  5203.1  425.07  5218.1  425.06  5233.2  425.85
  5239.2  426.96  5318.8  430.23  5326.3  431.33  5347.3  431.33  5390.9  434.46
#Mann=5,-1,0
  4397.9    0.05       0  4770.8    0.16       0  4890.3    0.07       0
  4896.3    0.16       0  5084.1    0.05       0
Bank Sta=4890.3,4896.3
Exp/Cntr=0.3,0.1

Type RM Length L Ch R = 1,6484,671,671,671
BEGIN DESCRIPTION:
UNT 006 IN UKCR 6.0
END DESCRIPTION:
XS GIS Cut Line= 3
      3583199.62     10585760.22      3583082.13     10585385.93
      3582949.62     10585110.21
#Sta/Elev= 30
  4559.4  431.78  4575.6  429.82  4632.8  427.03  4664.2  424.69  4695.7  423.63
  4769.1  418.72  4775.4  417.80  4780.6  418.55  4800.5  417.97  4807.8  416.43
  4813.0  418.50  4852.7  418.44  4872.6  417.92  4877.9  415.82  4884.3  415.40
  4926.3  414.34  4980.3  415.58  4989.0  413.68  4994.5  414.08  4999.4  413.24
  5002.2  412.74  5005.4  413.24  5011.6  415.81  5017.2  414.73  5034.2  417.28
  5039.8  417.03  5056.9  419.53  5152.7  426.28  5198.3  428.22  5257.6  429.16
#Mann=5,-1,0
  4559.4    0.05       0  4852.7    0.16       0  4999.4    0.07       0
  5005.4    0.16       0  5152.7    0.05       0
Bank Sta=4999.4,5005.4
Exp/Cntr=0.3,0.1

Type RM Length L Ch R = 1,5813,481,481,481
BEGIN DESCRIPTION:
UNT 006 IN UKCR 5.0
END DESCRIPTION:
XS GIS Cut Line= 3
      3583549.62     10585560.23      3583499.61     10585210.19
      3583249.64     10584960.22
#Sta/Elev= 30
  4665.5  426.95  4695.8  425.67  4705.9  424.70  4716.1  424.60  4756.5  422.66
  4817.1  418.60  4827.2  417.38  4867.6  414.81  4908.0  413.86  4958.5  412.08
  4988.8  412.31  4995.9  410.44  4998.6  409.94  5001.9  410.44  5004.5  410.97
  5016.6  412.76  5047.4  413.26  5075.7  412.52  5118.1  413.69  5146.4  415.34
  5159.4  416.92  5174.7  418.57  5188.8  421.00  5202.9  421.76  5217.1  423.30
  5245.4  424.63  5259.5  425.88  5287.8  427.11  5326.0  427.12  5372.6  427.02
#Mann=6,-1,0
  4665.5    0.05       0  4995.9    0.03       0  5001.9    0.05       0
  5004.5    0.12       0  5159.4    0.05       0  5326.0    0.15       0
Bank Sta=4995.9,5001.9
Exp/Cntr=0.3,0.1

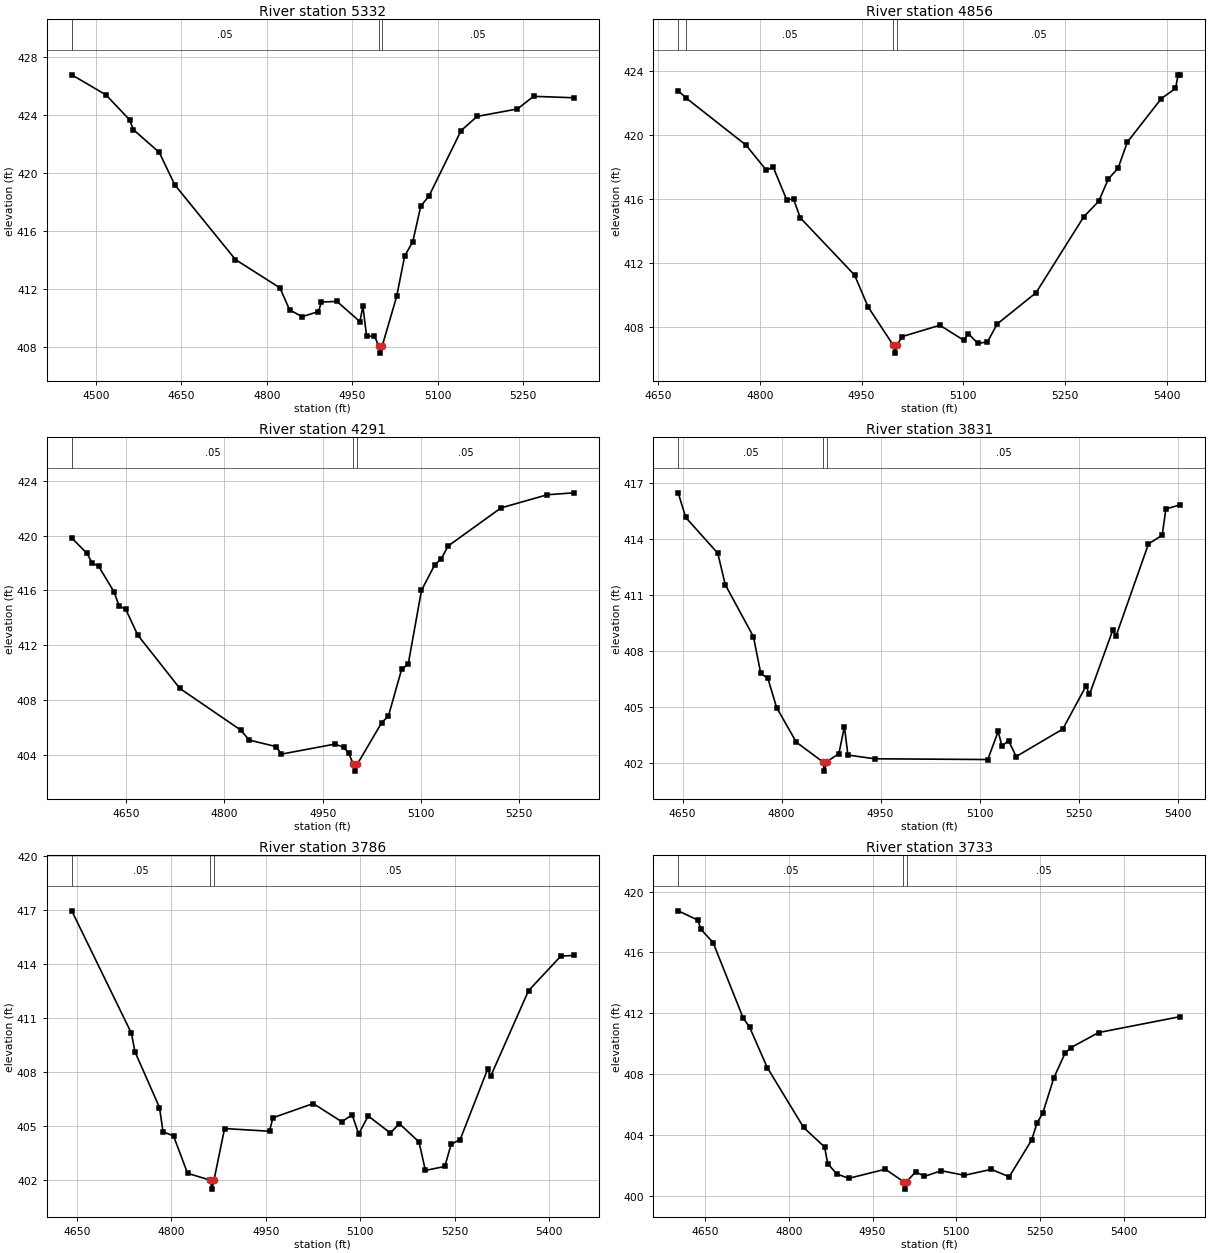
Type RM Length L Ch R = 1,5332,476,476,476
BEGIN DESCRIPTION:
UNT 006 IN UKCR 4.0
END DESCRIPTION:
XS GIS Cut Line= 3
      3583894.63     10585517.86      3583749.61     10585010.19
      3583499.63     10584760.21
#Sta/Elev= 30
  4457.7  426.76  4517.7  425.38  4559.3  423.66  4565.7  422.99  4611.3  421.42
  4638.5  419.19  4745.1  414.04  4823.2  412.09  4840.1  410.58  4862.2  410.11
  4890.8  410.46  4896.0  411.12  4923.3  411.16  4963.6  409.77  4968.8  410.83
  4975.3  408.78  4989.2  408.75  4996.8  408.10  4999.6  407.60  5002.8  408.10
  5028.1  411.50  5042.2  414.29  5056.4  415.27  5070.5  417.73  5084.7  418.40
  5141.2  422.92  5169.5  423.90  5240.2  424.41  5268.5  425.28  5339.2  425.18
#Mann=3,-1,0
  4457.7    0.05       0  4996.8    0.03       0  5002.8    0.05       0
Bank Sta=4996.8,5002.8
Exp/Cntr=0.3,0.1

Type RM Length L Ch R = 1,4856,565,565,565
BEGIN DESCRIPTION:
UNT 006 IN UKCR 3.0
END DESCRIPTION:
XS GIS Cut Line= 3
      3584149.61     10585360.19      3584149.61     10585010.19
      3583849.62     10584760.20
#Sta/Elev= 30
  4679.6  422.77  4691.6  422.30  4779.6  419.37  4809.6  417.80  4819.6  418.00
  4839.6  415.95  4849.6  416.01  4859.6  414.83  4939.6  411.26  4959.6  409.27
  4996.6  406.88  4999.4  406.38  5002.6  406.88  5009.6  407.41  5065.4  408.12
  5100.5  407.19  5107.7  407.59  5121.4  406.99  5135.7  407.08  5150.0  408.20
  5207.3  410.15  5277.6  414.89  5299.7  415.86  5314.0  417.26  5328.3  417.93
  5342.0  419.56  5392.1  422.28  5413.0  422.91  5416.9  423.76  5420.1  423.76
#Mann=4,-1,0
  4679.6     0.1       0  4691.6    0.05       0  4996.6    0.03       0
  5002.6    0.05       0
Bank Sta=4996.6,5002.6
Exp/Cntr=0.3,0.1

Type RM Length L Ch R = 1,4291,460,460,460
BEGIN DESCRIPTION:
UNT 006 IN UKCR 2.0
END DESCRIPTION:
XS GIS Cut Line= 3
      3584699.62     10584760.19      3584299.61     10584660.19
      3583949.59     10584610.19
#Sta/Elev= 30
  4567.2  419.83  4590.4  418.71  4598.1  418.02  4608.4  417.75  4631.6  415.90
  4639.4  414.87  4649.7  414.61  4667.7  412.75  4732.1  408.84  4824.9  405.80
  4837.8  405.07  4879.0  404.59  4886.8  404.04  4969.2  404.78  4982.1  404.53
  4989.6  404.12  4996.7  403.30  4999.5  402.80  5002.7  403.30  5040.1  406.35
  5050.2  406.82  5070.4  410.24  5080.5  410.63  5100.7  416.01  5120.9  417.87
  5131.0  418.32  5141.2  419.24  5222.0  422.03  5292.7  422.99  5333.1  423.13
#Mann=3,-1,0
  4567.2    0.05       0  4996.7    0.03       0  5002.7    0.05       0
Bank Sta=4996.7,5002.7
Exp/Cntr=0.3,0.1

Type RM Length L Ch R = 1,3831,45,45,45
BEGIN DESCRIPTION:
Mapping XS 3211ea77
END DESCRIPTION:
XS GIS Cut Line= 6
      3584688.47     10584646.35      3584577.79     10584331.67
      3584547.41     10584309.97      3584499.66     10584322.99
      3584397.67     10584396.78      3584193.04     10584450.62
#Sta/Elev= 30
  4643.5  416.47  4654.7  415.16  4703.4  413.24  4714.7  411.56  4757.4  408.78
  4768.5  406.81  4779.2  406.56  4792.5  404.99  4822.3  403.14  4862.3  402.09
  4865.0  401.59  4868.3  402.09  4886.8  402.52  4895.2  403.97  4900.5  402.45
  4941.1  402.25  5112.4  402.21  5128.1  403.71  5133.9  402.93  5143.8  403.22
  5155.4  402.37  5226.0  403.84  5261.2  406.14  5266.4  405.69  5301.5  409.11
  5306.7  408.82  5355.8  413.74  5376.5  414.20  5382.2  415.61  5404.0  415.83
#Mann=3,-1,0
  4643.5    0.05       0  4862.3    0.03       0  4868.3    0.05       0
Bank Sta=4862.3,4868.3
Exp/Cntr=0.3,0.1

Type RM Length L Ch R = 1,3786,53,53,53
BEGIN DESCRIPTION:
Mapping XS 0edddfe5
END DESCRIPTION:
XS GIS Cut Line= 6
      3584727.52     10584609.43      3584606.00     10584296.95
      3584582.13     10584279.59      3584493.15     10584281.76
      3584443.24     10584338.18      3584189.35     10584394.60
#Sta/Elev= 30
  4641.6  416.95  4736.4  410.14  4742.0  409.11  4781.0  406.01  4786.6  404.66
  4803.3  404.43  4825.6  402.35  4861.6  401.97  4864.3  401.47  4867.6  401.97
  4884.4  404.84  4955.8  404.69  4961.2  405.44  5025.3  406.23  5070.6  405.22
  5087.2  405.60  5097.4  404.54  5112.7  405.54  5147.8  404.59  5162.1  405.11
  5193.3  404.10  5203.5  402.51  5234.3  402.73  5244.5  403.97  5258.8  404.23
  5302.3  408.13  5307.5  407.77  5367.4  412.51  5418.7  414.43  5439.4  414.47
#Mann=3,-1,0
  4641.6    0.05       0  4861.6    0.03       0  4867.6    0.05       0
Bank Sta=4861.6,4867.6
Exp/Cntr=0.3,0.1

Type RM Length L Ch R = 1,3733,211,211,211
BEGIN DESCRIPTION:
Mapping XS 0e4d8a44
END DESCRIPTION:
XS GIS Cut Line= 5
      3584833.85     10584592.05      3584668.93     10584296.95
      3584612.51     10584227.50      3584517.02     10584203.63
      3584143.09     10584218.76
#Sta/Elev= 30
  4601.6  418.74  4636.7  418.13  4642.4  417.52  4664.1  416.65  4717.8  411.71
  4729.7  411.07  4761.2  408.43  4826.3  404.49  4864.0  403.20  4869.7  402.11
  4885.7  401.43  4907.4  401.14  4973.0  401.74  5005.1  400.93  5007.9  400.43
  5011.1  400.93  5027.5  401.57  5043.1  401.27  5073.4  401.64  5114.6  401.34
  5163.0  401.73  5195.0  401.24  5235.1  403.65  5245.1  404.80  5255.1  405.42
  5275.1  407.75  5295.1  409.37  5305.1  409.73  5355.2  410.73  5501.8  411.78
#Mann=3,-1,0
  4601.6    0.05       0  5005.1    0.03       0  5011.1    0.05       0
Bank Sta=5005.1,5011.1
Exp/Cntr=0.3,0.1

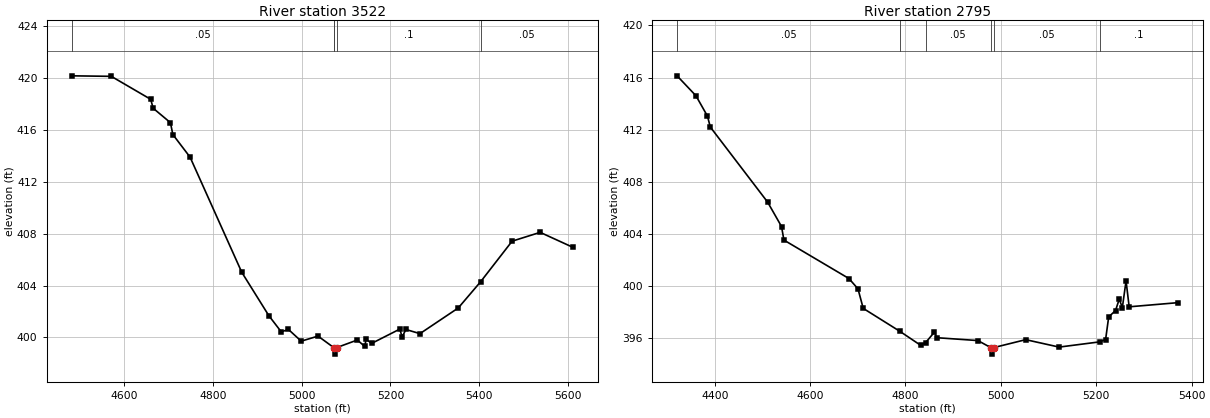
Type RM Length L Ch R = 1,3522,727,727,727
BEGIN DESCRIPTION:
Mapping XS 543c4776
END DESCRIPTION:
XS GIS Cut Line= 3
      3585037.84     10584589.88      3584734.04     10583999.64
      3584292.93     10583852.61
#Sta/Elev= 30
  4482.1  420.17  4571.3  420.13  4660.0  418.36  4665.6  417.67  4704.4  416.56
  4710.0  415.64  4748.7  413.90  4865.2  405.02  4926.1  401.68  4954.1  400.43
  4970.4  400.61  4999.1  399.71  5037.0  400.10  5072.2  399.22  5072.7  399.21
  5075.4  398.71  5078.7  399.21  5125.6  399.80  5142.2  399.30  5145.3  399.85
  5157.9  399.54  5221.2  400.64  5226.5  400.03  5234.9  400.61  5266.6  400.29
  5352.9  402.27  5403.0  404.28  5474.2  407.42  5537.4  408.10  5610.9  406.95
#Mann=5,-1,0
  4482.1    0.05       0  5072.2     0.1       0  5072.7    0.03       0
  5078.7     0.1       0  5403.0    0.05       0
Bank Sta=5072.7,5078.7
Exp/Cntr=0.3,0.1

Type RM Length L Ch R = 1,2795,0,0,0
BEGIN DESCRIPTION:
UNT 006 IN UKCR 1.0
END DESCRIPTION:
XS GIS Cut Line= 3
      3585150.70     10584459.75      3585202.79     10583626.38
      3585037.87     10583487.50
#Sta/Elev= 30
  4321.1  416.13  4360.7  414.60  4384.8  413.04  4390.8  412.20  4511.0  406.44
  4540.1  404.57  4545.1  403.53  4681.4  400.58  4700.4  399.79  4711.4  398.29
  4788.2  396.53  4831.7  395.46  4842.4  395.67  4860.7  396.47  4865.7  396.04
  4951.9  395.82  4978.9  395.28  4981.7  394.78  4984.9  395.28  5052.1  395.89
  5122.2  395.32  5207.1  395.72  5219.6  395.90  5226.1  397.64  5240.4  398.12
  5248.2  399.00  5254.7  398.35  5262.5  400.40  5269.0  398.41  5371.7  398.73
#Mann=6,-1,0
  4321.1    0.05       0  4788.2     0.1       0  4842.4    0.05       0
  4978.9    0.03       0  4984.9    0.05       0  5207.1     0.1       0
Bank Sta=4978.9,4984.9
Exp/Cntr=0.3,0.1

Chan Stop Cuts=-1