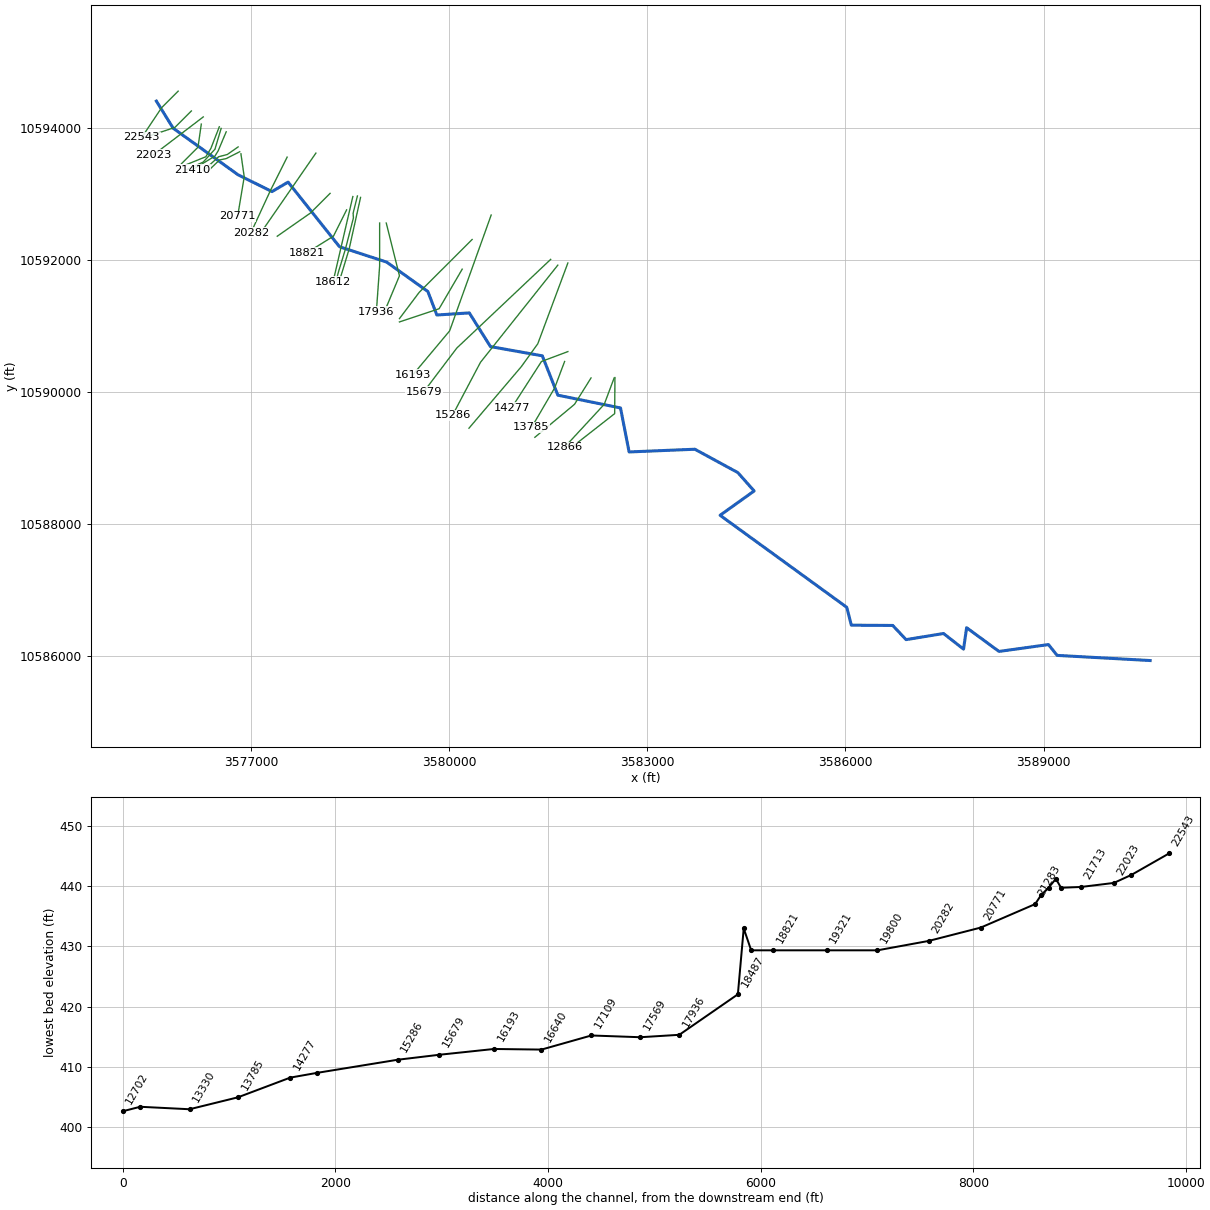
--- UNT 013 IN UKCR.prj (project) ---

Proj Title=UNT 013 IN UKCR Base Level Engineering
Current Plan=p01
Default Exp/Contr=0.3,0.1
English Units
Geom File=g01
Flow File=f01
Plan File=p01
Y Axis Title=Elevation
X Axis Title(PF)=Main Channel Distance
X Axis Title(XS)=Station
BEGIN DESCRIPTION:
UNT 013 IN UKCR
END DESCRIPTION:
DSS Export Rating Curves= 0
DSS Export Rating Curve Sorted= 0
DSS Export Volume Flow Curves= 0
DXF OffsetX= 0
DXF OffsetY= 0
DXF ScaleX= 1
DXF ScaleY= 10

--- UNT 013 IN UKCR.p01 (plan) ---

Plan Title=Multiple Run
Short Identifier=Multiple
Geom File=g01
Flow File=f01
Subcritical Flow
K Sum by GR= 0
Std Step Tol= 0.01
Critical Tol= 0.01
Num of Std Step Trials= 20
Max Error Tol= 0.3
Flow Tol Ratio= 0.001
Split Flow NTrial= 30
Split Flow Tol= 0.02
Split Flow Ratio= 0.02
Log Output Level= 0
Friction Slope Method= 1
Unsteady Friction Slope Method= 2
Unsteady Bridges Friction Slope Method= 1
Parabolic Critical Depth
Global Vel Dist=  1 , 1 , 1
Global Log Level= 0
CheckData=True
Encroach Param= -1, 0, 0, 0
BEGIN DESCRIPTION:
Multiple Run
END DESCRIPTION:

--- UNT 013 IN UKCR.f01 (steady flow) ---

Flow Title=Multiple
Program Version=4.10
Number of Profiles= 7
Profile Names=10-year,25-year,50-year,1pct_min,100-year,1pct_plu,500-year
River Rch & RM=UNT 013 IN UKCR,Reach-1         ,22543
    1229    1698    2087    1870    2530    3421    3704
River Rch & RM=UNT 013 IN UKCR,Reach-1         ,20282
    1414    1964    2422    2178    2945    3983    4339
River Rch & RM=UNT 013 IN UKCR,Reach-1         ,17109
    2061    2912    3633    3298    4460    6032    6705
River Rch & RM=UNT 013 IN UKCR,Reach-1         ,16640
    2061    2912    3633    3298    4460    6032    6705
River Rch & RM=UNT 013 IN UKCR,Reach-1         ,12131
    2582    3675    4607    4198    5678    7679    8604
River Rch & RM=UNT 013 IN UKCR,Reach-1         ,3067
    2719    3875    4862    4433    5995    8108    9094
Boundary for River Rch & Prof#=UNT 013 IN UKCR,Reach-1         , 1
Up Type= 0
Dn Type= 3
Dn Slope=0.005
Boundary for River Rch & Prof#=UNT 013 IN UKCR,Reach-1         , 2
Up Type= 0
Dn Type= 3
Dn Slope=0.005
Boundary for River Rch & Prof#=UNT 013 IN UKCR,Reach-1         , 3
Up Type= 0
Dn Type= 3
Dn Slope=0.005
Boundary for River Rch & Prof#=UNT 013 IN UKCR,Reach-1         , 4
Up Type= 0
Dn Type= 3
Dn Slope=0.005
Boundary for River Rch & Prof#=UNT 013 IN UKCR,Reach-1         , 5
Up Type= 0
Dn Type= 3
Dn Slope=0.005
Boundary for River Rch & Prof#=UNT 013 IN UKCR,Reach-1         , 6
Up Type= 0
Dn Type= 3
Dn Slope=0.005
Boundary for River Rch & Prof#=UNT 013 IN UKCR,Reach-1         , 7
Up Type= 0
Dn Type= 3
Dn Slope=0.005
DSS Import GetInterval= 0
DSS Import GetPeak= 0
DSS Import FillOption= 0

--- UNT 013 IN UKCR.g01 (geometry) ---

Geom Title=Existing Conditions

River Reach=UNT 013 IN UKCR,Reach-1
Reach XY= 30
      3575569.75     10594410.00      3575824.00     10593998.00
      3576808.00     10593291.00      3577320.50     10593037.00
      3577563.50     10593181.00      3578341.75     10592201.00
      3579057.25     10591967.00      3579679.75     10591521.00
      3579815.75     10591165.00      3580307.00     10591197.00
      3580627.25     10590686.00      3581412.25     10590546.00
      3581647.50     10589949.00      3582596.00     10589755.00
      3582726.00     10589088.00      3583721.50     10589129.00
      3584372.00     10588775.00      3584618.75     10588496.00
      3584103.50     10588127.00      3586020.50     10586732.00
      3586090.50     10586460.00      3586717.25     10586456.00
      3586919.00     10586241.00      3587485.75     10586334.00
      3587788.75     10586097.00      3587835.25     10586422.00
      3588325.25     10586062.00      3589075.00     10586166.00
      3589205.25     10586002.00      3590612.75     10585924.00

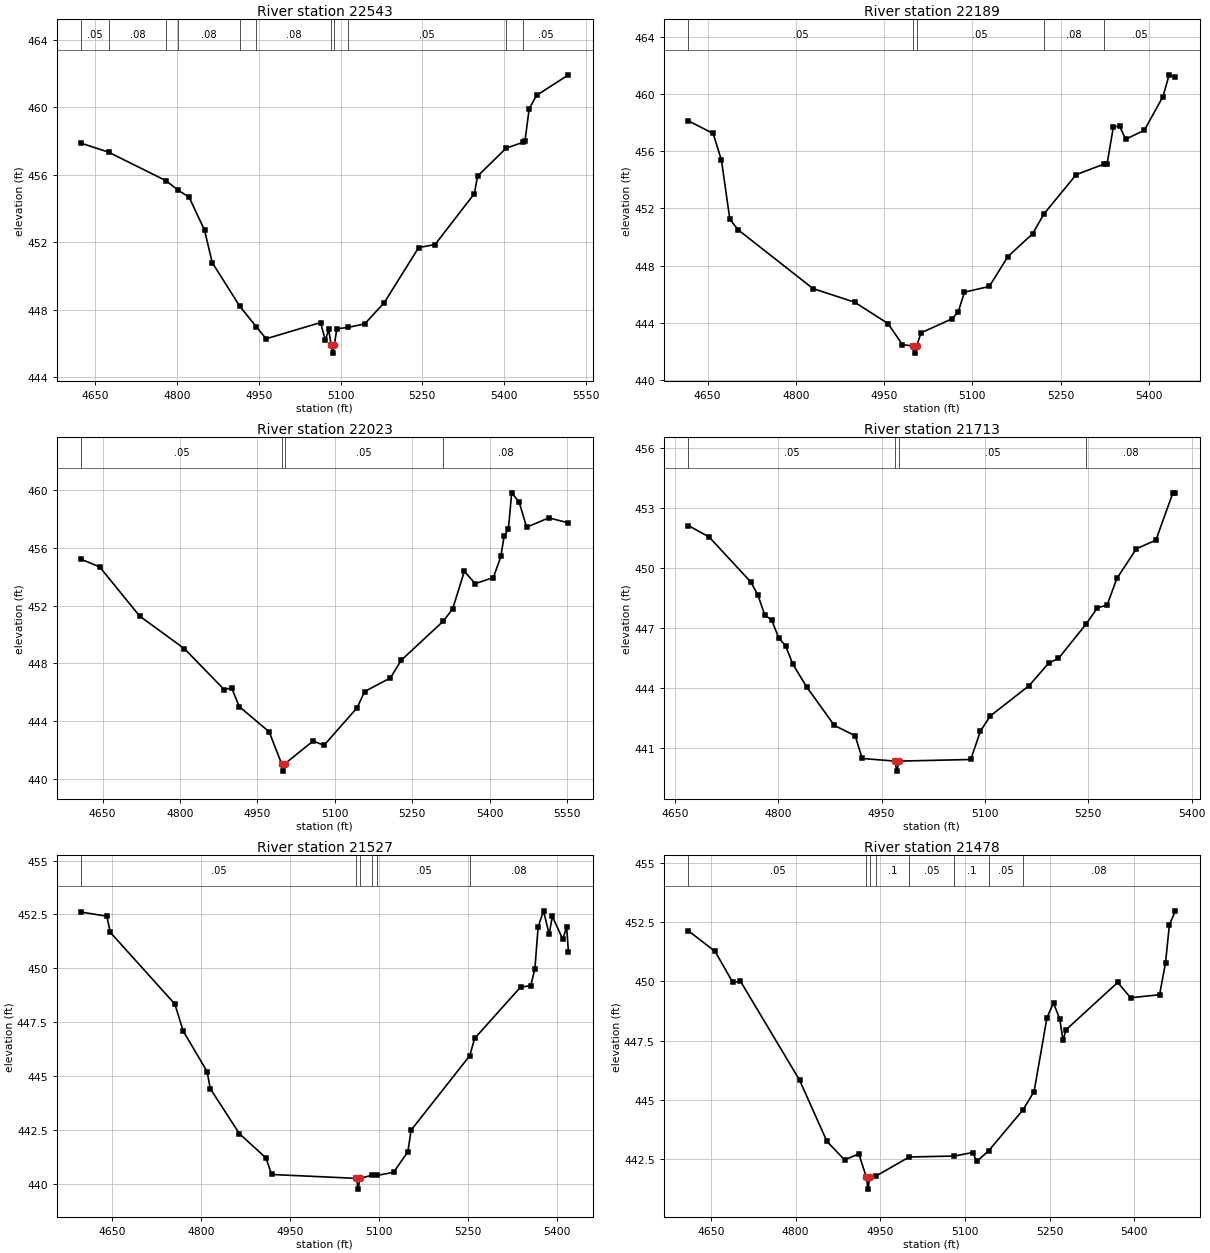
Type RM Length L Ch R = 1,22543,354,354,354
BEGIN DESCRIPTION:
UNT 013 IN UKCR 44.0
END DESCRIPTION:
XS GIS Cut Line= 3
      3575899.60     10594560.17      3575649.61     10594310.19
      3575349.59     10593860.16
#Sta/Elev= 30
  4624.0  457.87  4674.2  457.34  4780.1  455.64  4800.9  455.11  4822.0  454.67
  4850.3  452.72  4864.4  450.80  4914.7  448.23  4945.3  447.00  4963.4  446.29
  5063.2  447.25  5072.2  446.20  5078.2  446.84  5082.7  445.94  5085.5  445.44
  5088.7  445.94  5093.2  446.88  5112.9  446.96  5144.3  447.17  5180.3  448.43
  5243.4  451.69  5273.5  451.87  5345.6  454.88  5351.6  455.92  5404.1  457.58
  5434.7  457.92  5438.7  458.03  5446.3  459.91  5459.8  460.70  5518.4  461.92
#Mann=11,-1,0
  4624.0    0.05       0  4674.2    0.08       0  4780.1    0.07       0
  4800.9    0.08       0  4914.7     0.1       0  4945.3    0.08       0
  5082.7    0.07       0  5088.7    0.08       0  5112.9    0.05       0
  5404.1    0.08       0  5434.7    0.05       0
Bank Sta=5082.7,5088.7
Exp/Cntr=0.3,0.1

Type RM Length L Ch R = 1,22189,166,166,166
BEGIN DESCRIPTION:
UNT 013 IN UKCR 43.0
END DESCRIPTION:
XS GIS Cut Line= 3
      3576099.59     10594260.17      3575849.61     10594010.19
      3575399.58     10593860.18
#Sta/Elev= 30
  4617.1  458.12  4659.5  457.23  4673.6  455.36  4687.8  451.24  4701.9  450.50
  4829.2  446.39  4899.9  445.44  4956.5  443.95  4981.2  442.47  4999.3  442.38
  5002.0  441.88  5005.3  442.38  5012.8  443.30  5065.5  444.28  5076.0  444.77
  5086.6  446.14  5128.7  446.54  5160.4  448.63  5202.5  450.23  5221.3  451.59
  5276.3  454.35  5324.2  455.10  5329.0  455.12  5339.6  457.70  5350.1  457.74
  5360.6  456.83  5392.3  457.46  5423.9  459.81  5434.4  461.33  5445.0  461.16
#Mann=5,-1,0
  4617.1    0.05       0  4999.3    0.03       0  5005.3    0.05       0
  5221.3    0.08       0  5324.2    0.05       0
Bank Sta=4999.3,5005.3
Exp/Cntr=0.3,0.1

Type RM Length L Ch R = 1,22023,310,310,310
BEGIN DESCRIPTION:
Mapping XS 379ef66a
END DESCRIPTION:
XS GIS Cut Line= 2
      3576279.52     10594169.52      3575529.51     10593596.60
#Sta/Elev= 30
  4608.7  455.20  4644.4  454.67  4721.8  451.27  4808.6  449.01  4885.6  446.18
  4900.1  446.30  4914.6  445.01  4972.7  443.26  4996.9  441.04  4999.6  440.54
  5002.9  441.04  5058.0  442.63  5078.8  442.32  5143.2  444.93  5157.7  446.05
  5207.6  446.99  5228.4  448.21  5310.1  450.92  5328.2  451.77  5350.9  454.37
  5371.8  453.51  5407.1  453.94  5421.6  455.40  5427.9  456.82  5436.2  457.27
  5442.5  459.80  5457.0  459.16  5471.5  457.42  5514.6  458.07  5552.5  457.72
#Mann=4,-1,0
  4608.7    0.05       0  4996.9    0.03       0  5002.9    0.05       0
  5310.1    0.08       0
Bank Sta=4996.9,5002.9
Exp/Cntr=0.3,0.1

Type RM Length L Ch R = 1,21713,186,186,186
BEGIN DESCRIPTION:
UNT 013 IN UKCR 42.0
END DESCRIPTION:
XS GIS Cut Line= 3
      3576249.61     10594060.17      3576199.61     10593710.19
      3575949.60     10593460.18
#Sta/Elev= 30
  4669.3  452.12  4699.6  451.55  4760.2  449.30  4770.3  448.66  4780.4  447.66
  4790.5  447.40  4800.6  446.52  4810.7  446.11  4820.8  445.23  4841.0  444.08
  4881.4  442.15  4911.7  441.63  4921.8  440.50  4969.3  440.37  4972.1  439.87
  4975.3  440.37  5079.4  440.45  5093.5  441.87  5107.7  442.62  5164.3  444.14
  5192.5  445.26  5206.7  445.49  5246.5  447.19  5263.2  448.01  5277.4  448.16
  5291.5  449.48  5319.8  450.96  5348.1  451.39  5372.8  453.75  5376.4  453.75
#Mann=4,-1,0
  4669.3    0.05       0  4969.3   0.033       0  4975.3    0.05       0
  5246.5    0.08       0
Bank Sta=4969.3,4975.3
Exp/Cntr=0.3,0.1

Type RM Length L Ch R = 1,21527,49,49,49
BEGIN DESCRIPTION:
Mapping XS 64040f59
END DESCRIPTION:
XS GIS Cut Line= 4
      3576522.57     10594020.21      3576394.10     10593690.35
      3576317.71     10593565.35      3576020.75     10593444.50
#Sta/Elev= 30
  4598.3  452.61  4641.3  452.42  4647.2  451.67  4756.0  448.34  4770.0  447.09
  4810.4  445.20  4815.7  444.41  4864.7  442.32  4909.5  441.19  4919.1  440.42
  5062.1  440.24  5064.9  439.74  5068.1  440.24  5088.8  440.39  5097.2  440.38
  5124.7  440.52  5148.8  441.48  5154.2  442.48  5253.1  445.94  5261.2  446.74
  5338.8  449.13  5355.9  449.19  5362.9  449.99  5368.3  451.92  5377.4  452.67
  5386.9  451.58  5392.3  452.41  5409.8  451.35  5416.4  451.91  5419.4  450.75
#Mann=6,-1,0
  4598.3    0.05       0  5062.1   0.033       0  5068.1    0.05       0
  5088.8     0.1       0  5097.2    0.05       0  5253.1    0.08       0
Bank Sta=5062.1,5068.1
Exp/Cntr=0.3,0.1

Type RM Length L Ch R = 1,21478,68,68,68
BEGIN DESCRIPTION:
UNT 013 IN UKCR 41.0
END DESCRIPTION:
XS GIS Cut Line= 4
      3576550.36     10593995.94      3576456.60     10593679.94
      3576279.52     10593485.49      3576033.77     10593371.27
#Sta/Elev= 30
  4609.5  452.15  4657.2  451.27  4688.5  449.96  4702.1  450.01  4807.0  445.82
  4855.4  443.23  4886.7  442.45  4911.9  442.70  4925.4  441.71  4928.2  441.21
  4931.4  441.71  4942.9  441.77  5001.2  442.57  5080.5  442.61  5114.1  442.76
  5120.8  442.38  5142.0  442.83  5203.1  444.57  5222.6  445.34  5245.4  448.46
  5257.1  449.09  5268.2  448.40  5273.8  447.51  5279.4  447.96  5370.9  449.96
  5393.8  449.31  5445.1  449.44  5455.6  450.79  5462.5  452.40  5473.1  452.99
#Mann=8,-1,0
  4609.5    0.05       0  4925.4    0.07       0  4931.4    0.05       0
  4942.9     0.1       0  5001.2    0.05       0  5080.5     0.1       0
  5142.0    0.05       0  5203.1    0.08       0
Bank Sta=4925.4,4931.4
Exp/Cntr=0.3,0.1

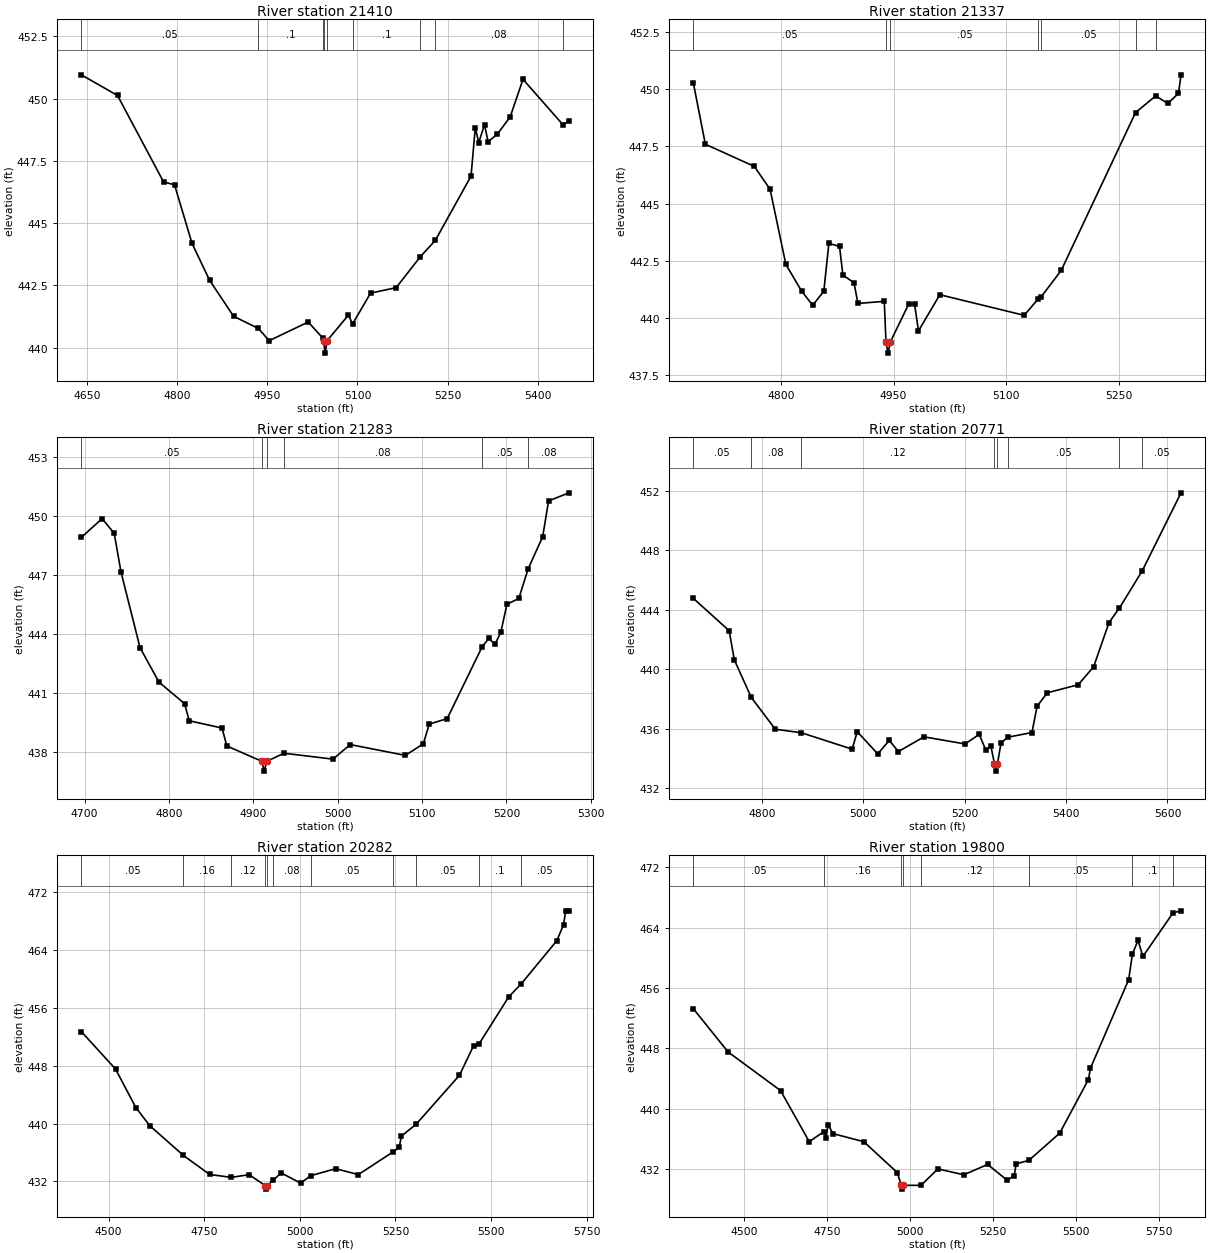
Type RM Length L Ch R = 1,21410,73,73,73
BEGIN DESCRIPTION:
Mapping XS 5e3af73e
END DESCRIPTION:
XS GIS Cut Line= 4
      3576626.73     10593943.81      3576505.21     10593655.63
      3576456.60     10593575.77      3576110.38     10593364.57
#Sta/Elev= 30
  4640.3  450.96  4700.6  450.13  4777.2  446.66  4795.5  446.54  4824.6  444.19
  4853.8  442.71  4893.8  441.26  4935.1  440.77  4953.1  440.28  5018.0  441.03
  5042.5  440.38  5043.5  440.28  5046.3  439.78  5049.5  440.28  5085.0  441.31
  5091.8  440.95  5121.8  442.19  5164.4  442.41  5204.9  443.66  5229.6  444.31
  5289.0  446.89  5296.1  448.83  5301.9  448.24  5311.5  448.96  5317.4  448.27
  5332.9  448.58  5354.2  449.27  5375.5  450.78  5442.2  448.95  5452.1  449.12
#Mann=9,-1,0
  4640.3    0.05       0  4935.1     0.1       0  5042.5    0.08       0
  5043.5    0.07       0  5049.5    0.08       0  5091.8     0.1       0
  5204.9    0.05       0  5229.6    0.08       0  5442.2    0.05       0
Bank Sta=5043.5,5049.5
Exp/Cntr=0.3,0.1

Type RM Length L Ch R = 1,21337,54,54,54
BEGIN DESCRIPTION:
Mapping XS 4b786155
END DESCRIPTION:
XS GIS Cut Line= 4
      3576807.28     10593714.65      3576644.10     10593600.08
      3576512.15     10593565.35      3576280.43     10593354.38
#Sta/Elev= 30
  4683.4  450.27  4699.4  447.59  4764.7  446.62  4785.6  445.62  4806.6  442.34
  4827.5  441.18  4842.3  440.56  4857.1  441.17  4863.8  443.26  4878.0  443.13
  4882.5  441.88  4897.3  441.54  4902.5  440.64  4937.6  440.73  4939.8  438.97
  4942.5  438.47  4945.8  438.97  4970.1  440.61  4977.9  440.61  4983.1  439.44
  5011.5  441.02  5123.8  440.12  5142.8  440.85  5146.7  440.94  5173.1  442.08
  5272.0  448.97  5298.9  449.70  5315.0  449.37  5329.2  449.81  5332.6  450.62
#Mann=7,-1,0
  4683.4    0.05       0  4939.8    0.07       0  4945.8    0.05       0
  5142.8     0.1       0  5146.7    0.05       0  5272.0    0.08       0
  5298.9    0.05       0
Bank Sta=4939.8,4945.8
Exp/Cntr=0.3,0.1

Type RM Length L Ch R = 1,21283,512,512,512
BEGIN DESCRIPTION:
Mapping XS e31d3fff
END DESCRIPTION:
XS GIS Cut Line= 4
      3576831.62     10593641.75      3576626.74     10593537.58
      3576526.04     10593516.74      3576348.99     10593346.63
#Sta/Elev= 30
  4696.0  448.91  4720.7  449.87  4735.0  449.12  4743.1  447.15  4765.6  443.31
  4788.0  441.56  4818.4  440.46  4824.0  439.59  4862.9  439.22  4868.5  438.31
  4910.0  437.53  4912.8  437.03  4916.0  437.53  4936.3  437.94  4994.4  437.64
  5014.8  438.38  5080.2  437.83  5101.5  438.42  5108.5  439.42  5129.8  439.70
  5171.2  443.35  5179.2  443.78  5186.4  443.47  5193.4  444.10  5200.6  445.51
  5214.7  445.81  5225.8  447.32  5243.0  448.95  5250.0  450.77  5274.2  451.18
#Mann=6,-1,0
  4696.0    0.05       0  4910.0    0.07       0  4916.0    0.05       0
  4936.3    0.08       0  5171.2    0.05       0  5225.8    0.08       0
Bank Sta=4910,4916
Exp/Cntr=0.3,0.1

Type RM Length L Ch R = 1,20771,489,489,489
BEGIN DESCRIPTION:
UNT 013 IN UKCR 40.0
END DESCRIPTION:
XS GIS Cut Line= 3
      3576849.61     10593610.21      3576899.61     10593260.19
      3576799.60     10592660.14
#Sta/Elev= 30
  4664.8  444.77  4735.5  442.59  4745.6  440.63  4779.0  438.10  4826.5  435.95
  4877.5  435.72  4978.0  434.61  4988.1  435.79  5028.5  434.29  5051.3  435.20
  5069.1  434.45  5119.8  435.44  5200.9  434.96  5228.7  435.61  5241.4  434.56
  5251.6  434.83  5258.7  433.63  5261.4  433.13  5264.7  433.63  5271.8  435.05
  5285.8  435.42  5332.7  435.73  5342.8  437.51  5363.1  438.41  5423.9  438.95
  5454.3  440.16  5484.7  443.14  5505.2  444.12  5550.1  446.62  5626.7  451.88
#Mann=8,-1,0
  4664.8    0.05       0  4779.0    0.08       0  4877.5    0.12       0
  5258.7    0.07       0  5264.7    0.12       0  5285.8    0.05       0
  5505.2    0.16       0  5550.1    0.05       0
Bank Sta=5258.7,5264.7
Exp/Cntr=0.3,0.1

Type RM Length L Ch R = 1,20282,482,482,482
BEGIN DESCRIPTION:
UNT 013 IN UKCR 39.0
END DESCRIPTION:
XS GIS Cut Line= 3
      3577549.60     10593560.17      3577299.61     10593060.19
      3576999.60     10592410.18
#Sta/Elev= 30
  4428.9  452.73  4518.3  447.55  4571.4  442.22  4607.8  439.71  4695.7  435.59
  4764.3  432.95  4820.6  432.55  4867.7  432.92  4909.4  431.42  4912.2  430.92
  4915.4  431.42  4929.9  432.14  4951.6  433.16  5002.1  431.75  5028.7  432.78
  5093.9  433.75  5153.1  432.93  5244.9  436.11  5260.0  436.69  5265.5  438.26
  5304.0  439.89  5417.4  446.68  5454.6  450.80  5468.8  451.03  5546.4  457.55
  5578.9  459.34  5672.1  465.32  5689.6  467.55  5695.1  469.43  5703.8  469.45
#Mann=11,-1,0
  4428.9    0.05       0  4695.7    0.16       0  4820.6    0.12       0
  4909.4    0.07       0  4915.4    0.12       0  4929.9    0.08       0
  5028.7    0.05       0  5244.9    0.08       0  5304.0    0.05       0
  5468.8     0.1       0  5578.9    0.05       0
Bank Sta=4909.4,4915.4
Exp/Cntr=0.3,0.1

Type RM Length L Ch R = 1,19800,479,479,479
BEGIN DESCRIPTION:
UNT 013 IN UKCR 38.0
END DESCRIPTION:
XS GIS Cut Line= 2
      3577984.39     10593620.93      3577149.63     10592410.22
#Sta/Elev= 30
  4346.6  453.27  4451.3  447.54  4609.6  442.42  4696.1  435.65  4740.7  436.99
  4746.8  436.12  4752.9  437.91  4767.8  436.71  4860.4  435.65  4961.9  431.54
  4973.7  429.86  4976.5  429.36  4979.7  429.86  5033.0  429.86  5084.2  432.04
  5162.0  431.26  5234.2  432.63  5293.2  430.53  5314.2  431.16  5320.2  432.71
  5358.4  433.17  5451.4  436.78  5537.9  443.88  5544.1  445.39  5659.3  457.12
  5670.8  460.55  5687.4  462.31  5702.3  460.20  5793.2  465.98  5817.2  466.24
#Mann=8,-1,0
  4346.6    0.05       0  4740.7    0.16       0  4973.7    0.07       0
  4979.7    0.16       0  5033.0    0.12       0  5358.4    0.05       0
  5670.8     0.1       0  5793.2    0.16       0
Bank Sta=4973.7,4979.7
Exp/Cntr=0.3,0.1

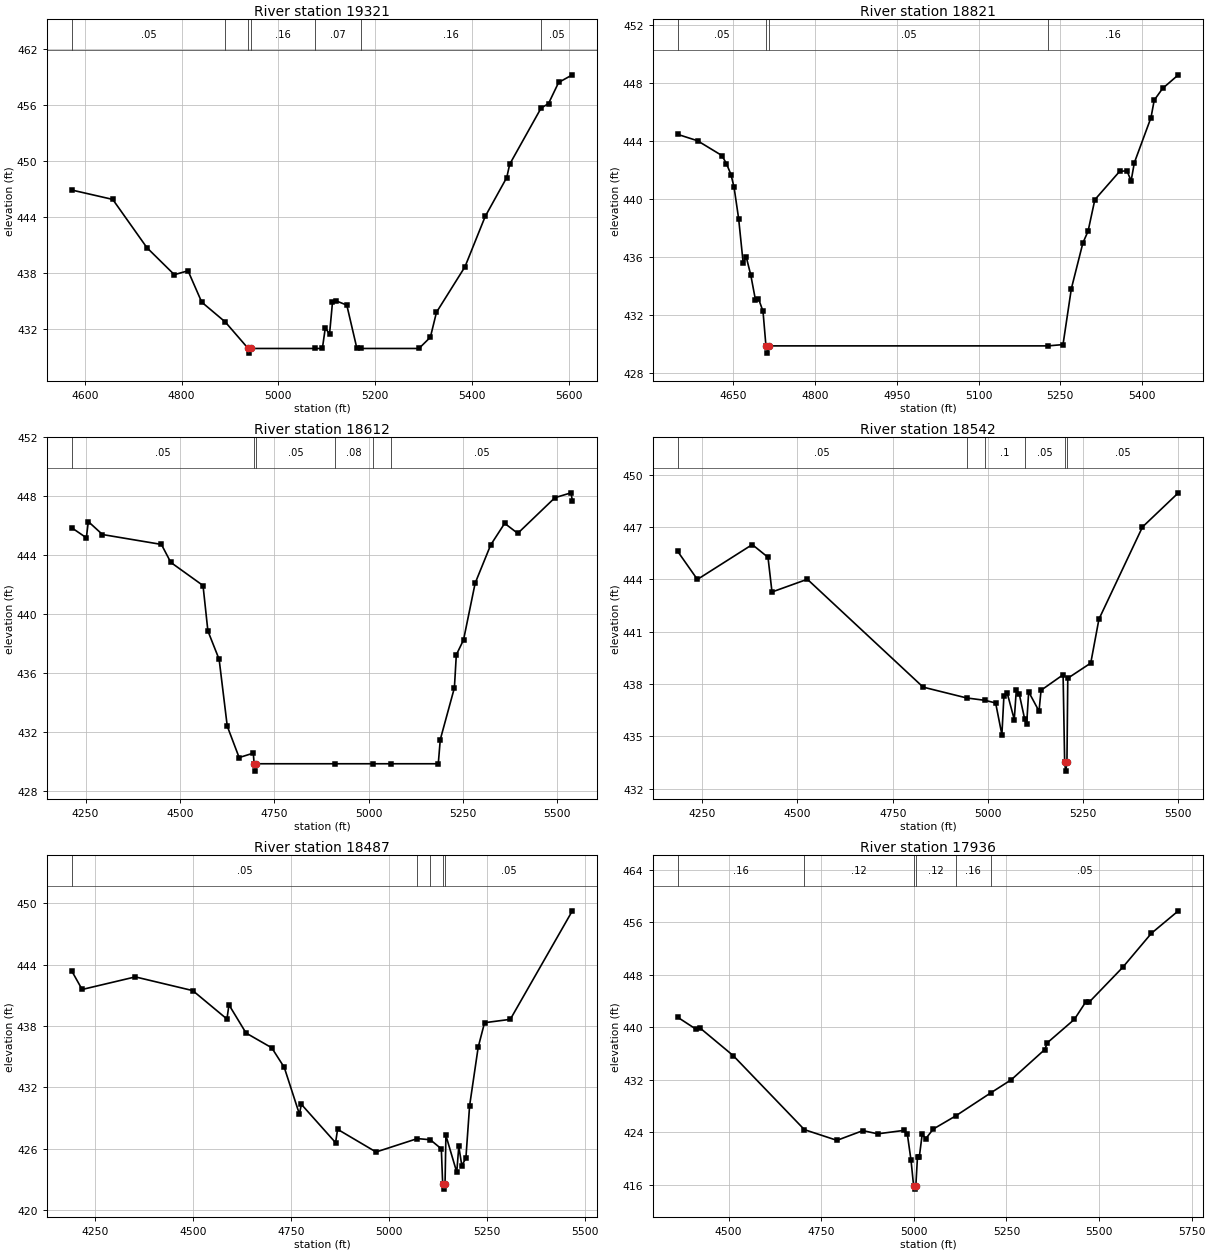
Type RM Length L Ch R = 1,19321,500,500,500
BEGIN DESCRIPTION:
UNT 013 IN UKCR 37.0
END DESCRIPTION:
XS GIS Cut Line= 3
      3578199.58     10593010.16      3577899.61     10592710.19
      3577399.57     10592360.16
#Sta/Elev= 30
  4572.9  446.89  4657.7  445.88  4728.4  440.69  4785.0  437.79  4813.3  438.21
  4841.6  434.84  4890.2  432.71  4937.6  429.86  4940.3  429.36  4943.6  429.86
  5076.3  429.86  5090.9  429.86  5097.0  432.08  5105.7  431.39  5111.8  434.82
  5119.2  434.98  5141.4  434.52  5162.3  429.86  5170.4  429.86  5290.5  429.86
  5314.1  431.07  5326.7  433.75  5385.6  438.64  5427.4  444.05  5471.9  448.23
  5478.0  449.66  5542.8  455.69  5558.2  456.18  5579.1  458.45  5607.5  459.27
#Mann=7,-1,0
  4572.9    0.05       0  4890.2    0.16       0  4937.6    0.07       0
  4943.6    0.16       0  5076.3    0.07       0  5170.4    0.16       0
  5542.8    0.05       0
Bank Sta=4937.6,4943.6
Exp/Cntr=0.3,0.1

Type RM Length L Ch R = 1,18821,209,209,209
BEGIN DESCRIPTION:
UNT 013 IN UKCR 36.0
END DESCRIPTION:
XS GIS Cut Line= 3
      3578449.63     10592760.23      3578249.61     10592360.19
      3577849.58     10592110.17
#Sta/Elev= 30
  4547.8  444.46  4584.2  444.02  4628.9  443.00  4637.3  442.44  4645.7  441.68
  4651.3  440.80  4659.7  438.64  4668.0  435.58  4673.6  436.00  4682.0  434.74
  4690.4  433.06  4696.0  433.13  4704.4  432.25  4709.8  429.86  4712.5  429.36
  4715.8  429.86  5227.7  429.86  5255.1  429.95  5270.4  433.81  5291.6  436.97
  5301.1  437.78  5313.5  439.95  5358.9  441.90  5372.4  441.95  5380.1  441.25
  5386.0  442.50  5416.6  445.62  5422.5  446.82  5437.9  447.63  5466.8  448.57
#Mann=4,-1,0
  4547.8    0.05       0  4709.8   0.033       0  4715.8    0.05       0
  5227.7    0.16       0
Bank Sta=4709.8,4715.8
Exp/Cntr=0.3,0.1

Type RM Length L Ch R = 1,18612,70,70,70
BEGIN DESCRIPTION:
Mapping XS 910e08bc
END DESCRIPTION:
XS GIS Cut Line= 2
      3578543.69     10592961.74      3578244.42     10591669.23
#Sta/Elev= 30
  4213.2  445.87  4252.1  445.19  4257.2  446.29  4294.8  445.41  4450.9  444.74
  4475.8  443.52  4561.2  441.95  4574.1  438.87  4603.9  436.94  4625.4  432.41
  4656.9  430.28  4694.4  430.58  4696.6  429.86  4699.3  429.36  4702.6  429.86
  4911.1  429.86  5012.7  429.86  5058.7  429.86  5184.6  429.86  5189.9  431.50
  5227.3  435.01  5232.4  437.25  5251.5  438.26  5282.3  442.11  5323.4  444.70
  5360.5  446.17  5395.2  445.49  5493.7  447.91  5536.4  448.24  5539.9  447.70
#Mann=6,-1,0
  4213.2    0.05       0  4696.6    0.07       0  4702.6    0.05       0
  4911.1    0.08       0  5012.7     0.1       0  5058.7    0.05       0
Bank Sta=4696.6,4702.6
Exp/Cntr=0.3,0.1

Type RM Length L Ch R = 1,18542,55,55,55
BEGIN DESCRIPTION:
Mapping XS 3320459c
END DESCRIPTION:
XS GIS Cut Line= 6
      3578613.13     10592970.40      3578548.09     10592709.35
      3578552.79     10592638.13      3578431.26     10592163.30
      3578326.46     10591819.81      3578296.30     10591698.74
#Sta/Elev= 30
  4185.5  445.61  4237.2  444.00  4381.3  446.00  4422.6  445.27  4433.1  443.28
  4525.9  444.01  4829.9  437.82  4944.0  437.20  4993.0  437.06  5020.3  436.91
  5036.7  435.09  5042.0  437.31  5050.8  437.47  5069.2  435.96  5074.5  437.64
  5082.2  437.43  5096.5  435.99  5101.7  435.68  5107.0  437.55  5134.2  436.44
  5139.5  437.64  5197.4  438.53  5201.5  433.50  5204.2  433.00  5207.5  433.50
  5209.7  438.33  5270.0  439.20  5291.5  441.72  5405.8  447.01  5500.0  448.97
#Mann=6,-1,0
  4185.5    0.05       0  4944.0    0.08       0  4993.0     0.1       0
  5096.5    0.05       0  5201.5    0.07       0  5207.5    0.05       0
Bank Sta=5201.5,5207.5
Exp/Cntr=0.3,0.1

Type RM Length L Ch R = 1,18487,551,551,551
BEGIN DESCRIPTION:
UNT 013 IN UKCR 35.0
END DESCRIPTION:
XS GIS Cut Line= 3
      3578660.88     10592948.75      3578487.27     10592163.15
      3578349.60     10591710.16
#Sta/Elev= 30
  4190.6  443.40  4217.2  441.58  4353.0  442.81  4499.6  441.47  4586.9  438.69
  4592.0  440.08  4635.7  437.32  4701.2  435.88  4733.2  433.96  4771.8  429.40
  4776.9  430.35  4864.2  426.60  4869.3  427.91  4967.5  425.69  5072.9  427.00
  5105.9  426.89  5134.1  426.00  5137.6  422.56  5140.4  422.06  5143.6  422.56
  5145.8  427.31  5173.5  423.71  5178.7  426.24  5186.4  424.37  5196.8  425.08
  5206.3  430.21  5228.2  435.93  5244.4  438.33  5310.2  438.66  5468.6  449.27
#Mann=5,-1,0
  4190.6    0.05       0  5072.9    0.16       0  5105.9    0.05       0
  5137.6    0.03       0  5143.6    0.05       0
Bank Sta=5137.6,5143.6
Exp/Cntr=0.3,0.1

Type RM Length L Ch R = 1,17936,367,367,367
BEGIN DESCRIPTION:
UNT 013 IN UKCR 34.0
END DESCRIPTION:
XS GIS Cut Line= 3
      3578949.61     10592560.23      3578949.61     10591910.19
      3578899.61     10591210.21
#Sta/Elev= 30
  4362.4  441.52  4412.4  439.68  4422.4  439.90  4512.4  435.67  4704.5  424.40
  4792.4  422.77  4862.4  424.25  4902.4  423.76  4972.4  424.28  4982.4  423.74
  4992.4  419.73  4999.4  415.84  5002.2  415.34  5005.4  415.84  5009.9  420.30
  5014.9  420.30  5022.5  423.67  5032.5  423.05  5052.5  424.49  5112.7  426.48
  5208.2  430.02  5263.1  432.00  5353.3  436.59  5360.8  437.65  5433.5  441.20
  5463.6  443.80  5473.6  443.83  5563.8  449.11  5641.5  454.31  5714.2  457.73
#Mann=6,-1,0
  4362.4    0.16       0  4704.5    0.12       0  4999.4    0.07       0
  5005.4    0.12       0  5112.7    0.16       0  5208.2    0.05       0
Bank Sta=4999.4,5005.4
Exp/Cntr=0.3,0.1

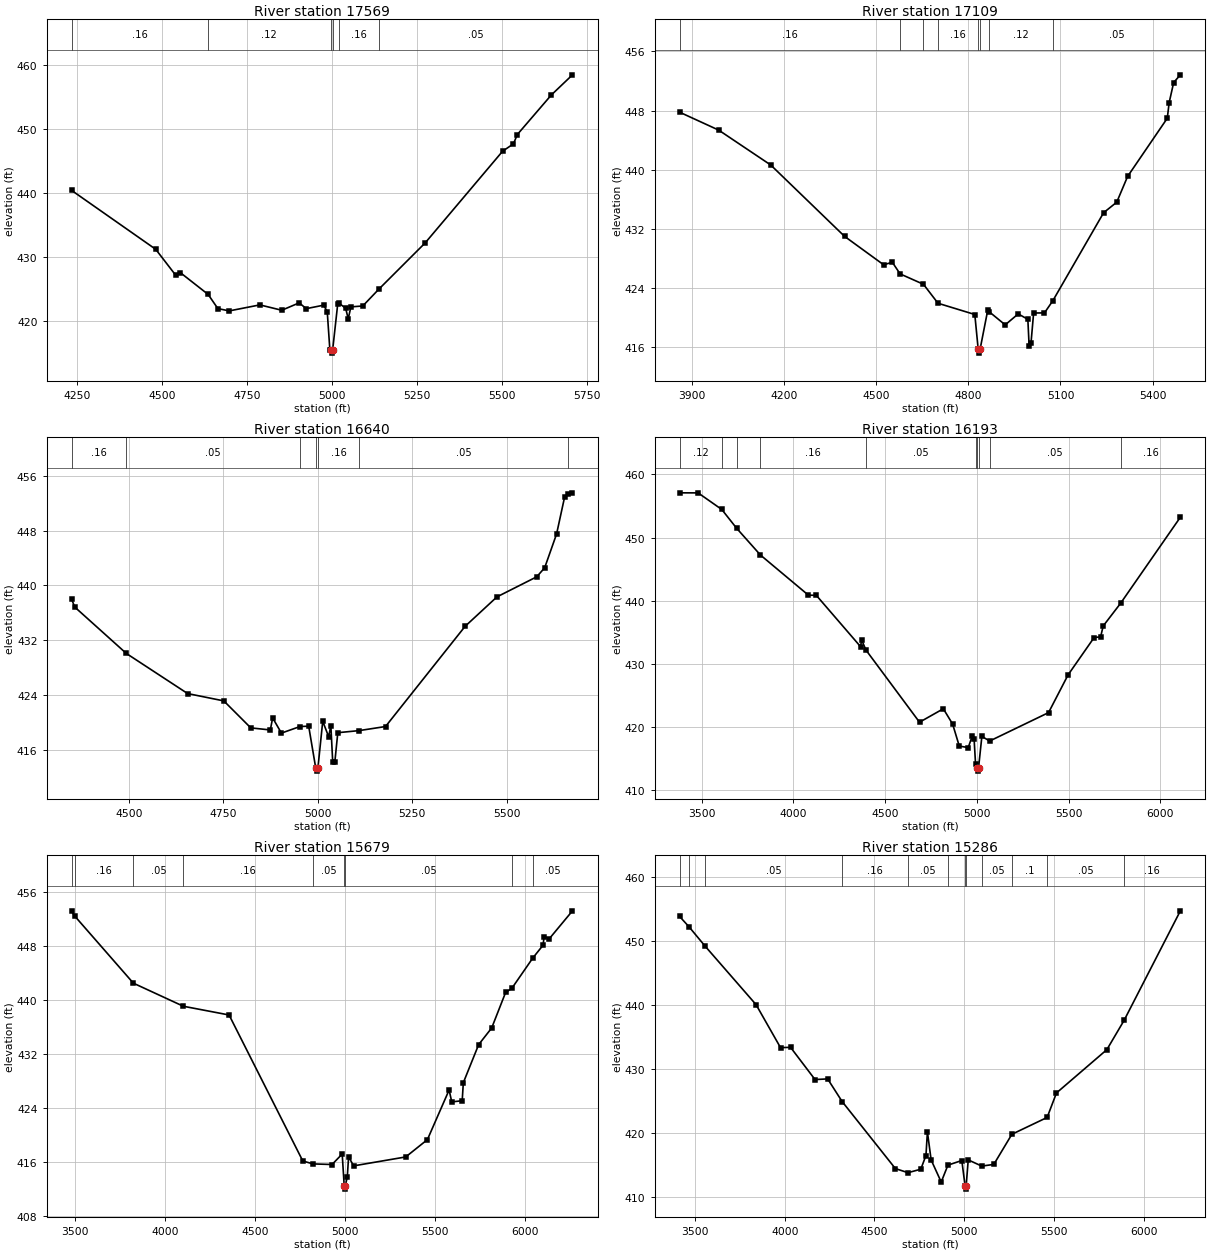
Type RM Length L Ch R = 1,17569,460,460,460
BEGIN DESCRIPTION:
UNT 013 IN UKCR 33.0
END DESCRIPTION:
XS GIS Cut Line= 3
      3579049.60     10592560.22      3579249.61     10591760.19
      3578999.63     10591160.23
#Sta/Elev= 30
  4233.8  440.40  4481.2  431.19  4540.5  427.10  4553.4  427.55  4635.5  424.13
  4664.2  421.91  4697.7  421.55  4787.9  422.49  4852.3  421.65  4903.8  422.81
  4924.4  421.90  4976.0  422.45  4986.3  421.40  4994.0  415.44  4996.2  415.44
  4998.9  414.94  5002.2  415.44  5017.2  422.67  5020.9  422.75  5040.4  421.97
  5048.1  420.31  5055.9  422.18  5090.9  422.32  5138.4  424.96  5274.6  432.19
  5502.6  446.54  5534.6  447.70  5545.9  449.15  5646.2  455.35  5708.4  458.50
#Mann=6,-1,0
  4233.8    0.16       0  4635.5    0.12       0  4996.2    0.07       0
  5002.2    0.12       0  5020.9    0.16       0  5138.4    0.05       0
Bank Sta=4996.2,5002.2
Exp/Cntr=0.3,0.1

Type RM Length L Ch R = 1,17109,469,469,469
BEGIN DESCRIPTION:
UNT 013 IN UKCR 32.0
END DESCRIPTION:
XS GIS Cut Line= 3
      3580349.63     10592310.21      3579549.61     10591510.19
      3579249.61     10591110.19
#Sta/Elev= 30
  3859.2  447.79  3986.5  445.37  4156.2  440.65  4396.6  431.01  4523.9  427.17
  4552.2  427.51  4577.5  425.94  4653.7  424.53  4701.0  421.97  4820.9  420.45
  4832.0  415.73  4834.8  415.23  4838.0  415.73  4863.3  421.09  4867.8  420.82
  4919.9  419.05  4962.3  420.53  4993.7  419.80  4997.9  416.17  5004.1  416.65
  5012.5  420.65  5047.9  420.67  5074.8  422.29  5240.6  434.21  5283.3  435.63
  5318.7  439.11  5447.9  446.97  5454.1  449.09  5468.7  451.80  5490.6  452.84
#Mann=8,-1,0
  3859.2    0.16       0  4577.5    0.12       0  4653.7    0.05       0
  4701.0    0.16       0  4832.0    0.07       0  4838.0    0.16       0
  4867.8    0.12       0  5074.8    0.05       0
Bank Sta=4832,4838
Exp/Cntr=0.3,0.1

Type RM Length L Ch R = 1,16640,447,447,447
BEGIN DESCRIPTION:
UNT 013 IN UKCR 31.0
END DESCRIPTION:
XS GIS Cut Line= 3
      3580199.59     10591860.16      3579849.61     10591260.19
      3579249.65     10591060.20
#Sta/Elev= 30
  4347.8  437.97  4355.6  436.85  4492.5  430.07  4655.0  424.21  4750.9  423.14
  4822.4  419.20  4874.1  418.90  4880.3  420.66  4903.5  418.44  4952.8  419.40
  4975.8  419.45  4994.3  413.39  4997.1  412.89  5000.3  413.39  5013.0  420.17
  5028.7  417.91  5034.5  419.53  5039.5  414.19  5045.0  414.19  5052.9  418.50
  5108.8  418.80  5179.4  419.40  5390.2  434.02  5474.6  438.32  5580.0  441.25
  5601.1  442.57  5632.7  447.51  5653.8  452.86  5664.2  453.41  5674.8  453.51
#Mann=7,-1,0
  4347.8    0.16       0  4492.5    0.05       0  4952.8    0.16       0
  4994.3    0.07       0  5000.3    0.16       0  5108.8    0.05       0
  5664.2    0.08       0
Bank Sta=4994.3,5000.3
Exp/Cntr=0.3,0.1

Type RM Length L Ch R = 1,16193,514,514,514
BEGIN DESCRIPTION:
UNT 013 IN UKCR 30.0
END DESCRIPTION:
XS GIS Cut Line= 3
      3580638.15     10592681.46      3580008.81     10590923.64
      3579455.44     10590261.77
#Sta/Elev= 30
  3379.6  457.08  3480.5  457.07  3609.6  454.44  3689.8  451.49  3820.5  447.22
  4082.0  440.86  4124.5  440.85  4366.3  432.70  4371.6  433.81  4395.0  432.19
  4687.4  420.74  4817.2  422.87  4868.0  420.44  4904.1  416.96  4952.9  416.72
  4974.2  418.49  4984.8  418.13  4993.0  414.06  5003.1  413.49  5005.8  412.99
  5009.1  413.49  5027.3  418.49  5069.8  417.76  5390.8  422.26  5497.5  428.25
  5639.3  434.16  5674.5  434.26  5688.8  435.99  5783.3  439.57  6109.4  453.22
#Mann=10,-1,0
  3379.6    0.12       0  3609.6    0.16       0  3689.8    0.12       0
  3820.5    0.16       0  4395.0    0.05       0  4993.0    0.16       0
  5003.1    0.07       0  5009.1    0.16       0  5069.8    0.05       0
  5783.3    0.16       0
Bank Sta=5003.1,5009.1
Exp/Cntr=0.3,0.1

Type RM Length L Ch R = 1,15679,393,393,393
BEGIN DESCRIPTION:
UNT 013 IN UKCR 29.0
END DESCRIPTION:
XS GIS Cut Line= 3
      3581538.78     10592008.74      3580117.32     10590663.23
      3579618.17     10590001.32
#Sta/Elev= 30
  3480.1  453.10  3496.1  452.43  3823.3  442.48  4101.3  439.07  4355.7  437.78
  4765.9  416.19  4822.7  415.76  4928.5  415.67  4985.1  417.22  4996.3  412.53
  4999.1  412.03  5002.3  412.53  5013.5  413.83  5020.7  416.82  5048.7  415.47
  5338.7  416.79  5459.2  419.35  5580.0  426.69  5594.6  424.93  5652.8  425.10
  5659.1  427.77  5744.4  433.40  5816.9  435.86  5894.3  441.11  5929.0  441.72
  6046.1  446.22  6102.5  448.09  6108.7  449.36  6137.9  449.07  6266.4  453.18
#Mann=9,-1,0
  3480.1    0.12       0  3496.1    0.16       0  3823.3    0.05       0
  4101.3    0.16       0  4822.7    0.05       0  4996.3    0.03       0
  5002.3    0.05       0  5929.0    0.16       0  6046.1    0.05       0
Bank Sta=4996.3,5002.3
Exp/Cntr=0.3,0.1

Type RM Length L Ch R = 1,15286,756,756,756
BEGIN DESCRIPTION:
UNT 013 IN UKCR 28.0
END DESCRIPTION:
XS GIS Cut Line= 3
      3581647.29     10591921.94      3580475.39     10590446.21
      3580052.71     10589644.21
#Sta/Elev= 30
  3414.1  453.80  3466.4  452.19  3556.0  449.17  3840.3  440.02  3976.5  433.31
  4032.6  433.35  4168.8  428.32  4239.2  428.42  4319.8  424.89  4616.7  414.41
  4686.9  413.77  4758.3  414.31  4787.1  416.45  4795.2  420.14  4816.0  415.76
  4872.1  412.31  4909.6  414.95  4987.0  415.67  5005.2  411.70  5008.0  411.20
  5011.2  411.70  5022.7  415.77  5097.9  414.80  5165.3  415.06  5266.0  419.77
  5462.5  422.40  5514.6  426.23  5795.3  432.99  5891.7  437.58  6205.1  454.68
#Mann=12,-1,0
  3414.1    0.12       0  3466.4    0.16       0  3556.0    0.05       0
  4319.8    0.16       0  4686.9    0.05       0  4909.6    0.16       0
  5005.2    0.07       0  5011.2    0.16       0  5097.9    0.05       0
  5266.0     0.1       0  5462.5    0.05       0  5891.7    0.16       0
Bank Sta=5005.2,5011.2
Exp/Cntr=0.3,0.1

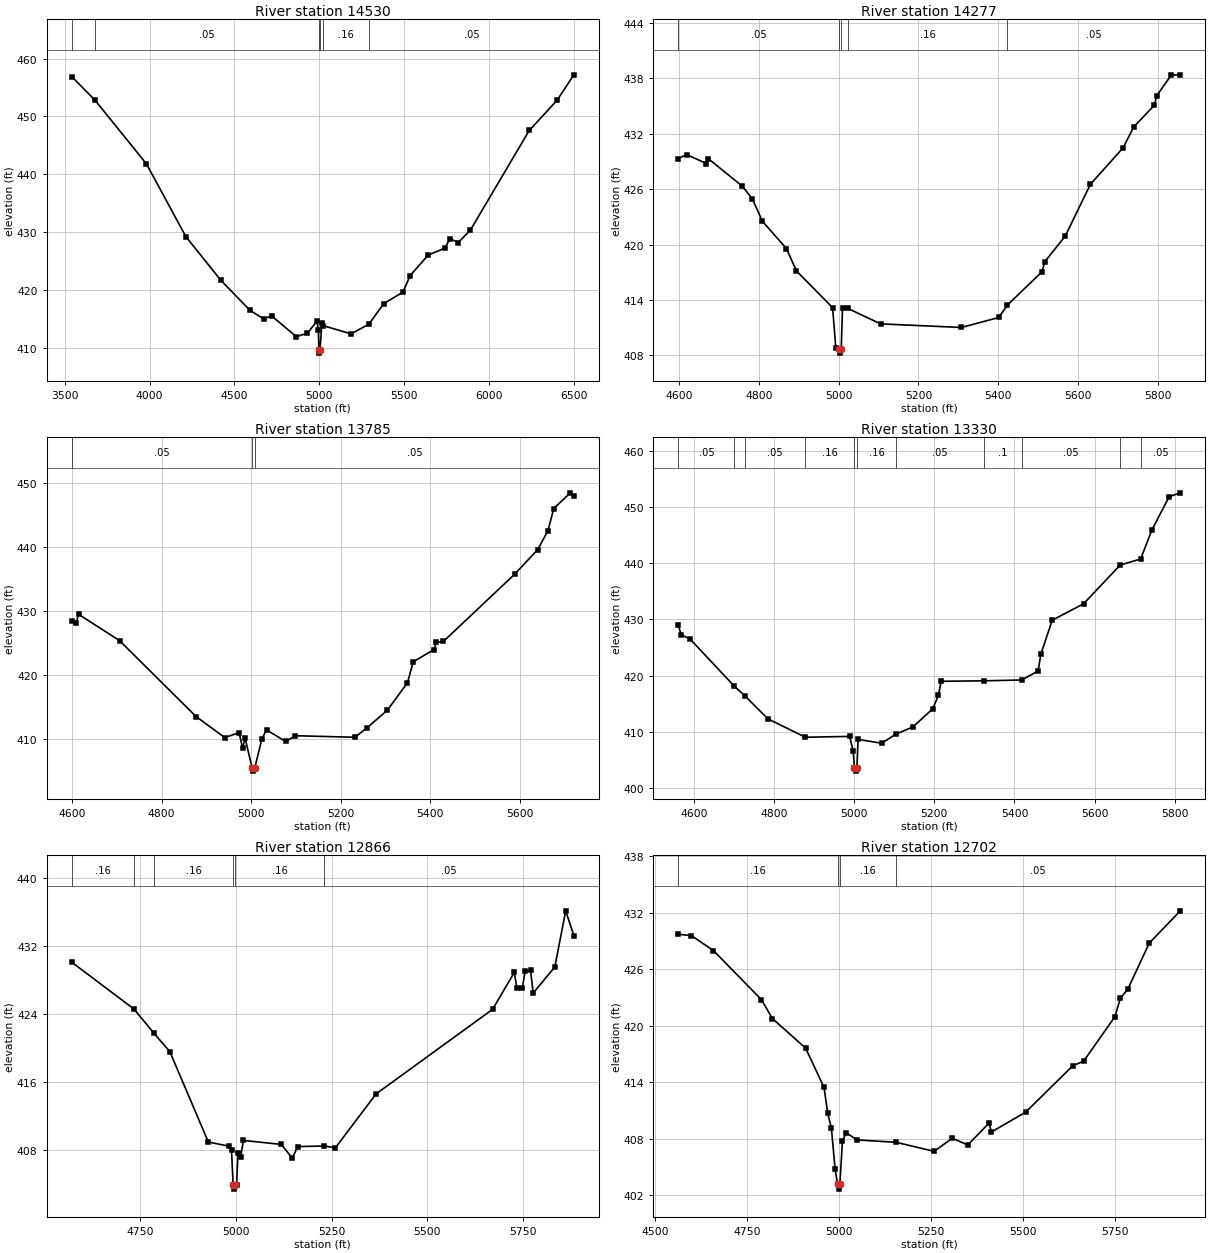
Type RM Length L Ch R = 1,14530,253,253,253
BEGIN DESCRIPTION:
UNT 013 IN UKCR 27.0
END DESCRIPTION:
XS GIS Cut Line= 4
      3581799.16     10591954.42      3581343.44     10590728.33
      3581093.88     10590381.11      3580301.75     10589447.92
#Sta/Elev= 30
  3541.6  456.87  3679.1  452.77  3981.7  441.78  4213.9  429.20  4421.0  421.61
  4592.5  416.43  4672.9  414.95  4719.6  415.47  4865.3  411.88  4930.4  412.47
  4986.8  414.54  4995.1  413.11  4998.6  409.53  5001.3  409.03  5004.6  409.53
  5016.3  414.24  5019.9  413.81  5188.2  412.37  5292.8  414.02  5380.6  417.60
  5493.7  419.57  5536.5  422.45  5643.1  426.01  5741.9  427.20  5770.5  428.85
  5819.9  428.16  5891.3  430.31  6238.4  447.55  6402.1  452.77  6501.3  457.18
#Mann=6,-1,0
  3541.6    0.12       0  3679.1    0.05       0  4998.6    0.03       0
  5004.6    0.05       0  5019.9    0.16       0  5292.8    0.05       0
Bank Sta=4998.6,5004.6
Exp/Cntr=0.3,0.1

Type RM Length L Ch R = 1,14277,492,492,492
BEGIN DESCRIPTION:
UNT 013 IN UKCR 26.0
END DESCRIPTION:
XS GIS Cut Line= 3
      3581799.65     10590610.20      3581399.61     10590460.19
      3580949.62     10589760.20
#Sta/Elev= 30
  4597.5  429.32  4618.9  429.75  4667.9  428.78  4673.2  429.30  4758.6  426.31
  4783.6  424.94  4808.5  422.53  4869.0  419.57  4893.9  417.15  4984.7  413.17
  4992.7  408.82  5000.4  408.74  5003.1  408.24  5006.4  408.74  5009.6  413.18
  5022.6  413.09  5105.0  411.41  5307.7  411.02  5401.5  412.10  5423.4  413.45
  5510.5  417.08  5516.5  418.12  5568.0  420.90  5631.4  426.53  5713.3  430.48
  5740.3  432.76  5791.9  435.10  5797.8  436.13  5834.1  438.36  5856.9  438.39
#Mann=5,-1,0
  4597.5    0.05       0  5000.4    0.03       0  5006.4    0.05       0
  5022.6    0.16       0  5423.4    0.05       0
Bank Sta=5000.4,5006.4
Exp/Cntr=0.3,0.1

Type RM Length L Ch R = 1,13785,455,455,455
BEGIN DESCRIPTION:
UNT 013 IN UKCR 25.0
END DESCRIPTION:
XS GIS Cut Line= 3
      3581749.62     10590460.21      3581599.61     10590060.19
      3581249.63     10589460.23
#Sta/Elev= 30
  4599.5  428.38  4609.3  428.07  4614.7  429.47  4706.3  425.35  4877.2  413.50
  4941.3  410.21  4973.3  410.98  4981.3  408.56  4986.7  410.15  5002.4  405.47
  5005.1  404.97  5008.4  405.47  5024.1  409.95  5034.6  411.41  5077.6  409.60
  5099.1  410.50  5232.2  410.26  5259.5  411.76  5304.6  414.48  5349.6  418.78
  5362.5  422.06  5408.4  423.93  5414.1  425.08  5429.9  425.23  5590.3  435.81
  5640.3  439.56  5663.5  442.53  5676.3  445.98  5713.5  448.44  5721.3  447.96
#Mann=3,-1,0
  4599.5    0.05       0  5002.4    0.03       0  5008.4    0.05       0
Bank Sta=5002.4,5008.4
Exp/Cntr=0.3,0.1

Type RM Length L Ch R = 1,13330,464,464,464
BEGIN DESCRIPTION:
UNT 013 IN UKCR 24.0
END DESCRIPTION:
XS GIS Cut Line= 3
      3582149.63     10590210.22      3581899.61     10589810.19
      3581299.58     10589310.16
#Sta/Elev= 30
  4561.0  428.94  4568.7  427.23  4589.9  426.55  4701.3  418.08  4726.5  416.45
  4785.1  412.28  4878.3  409.02  4988.5  409.17  4997.4  406.65  5000.8  403.49
  5003.6  402.99  5006.8  403.49  5009.7  408.64  5068.5  407.96  5104.5  409.59
  5146.6  410.86  5196.1  414.09  5210.4  416.51  5216.9  418.98  5325.2  419.07
  5417.9  419.21  5459.0  420.81  5465.6  423.76  5494.2  429.86  5572.3  432.77
  5663.9  439.68  5714.8  440.75  5742.8  445.90  5785.8  451.83  5813.8  452.53
#Mann=11,-1,0
  4561.0    0.05       0  4701.3    0.12       0  4726.5    0.05       0
  4878.3    0.16       0  5000.8    0.07       0  5006.8    0.16       0
  5104.5    0.05       0  5325.2     0.1       0  5417.9    0.05       0
  5663.9     0.1       0  5714.8    0.05       0
Bank Sta=5000.8,5006.8
Exp/Cntr=0.3,0.1

Type RM Length L Ch R = 1,12866,164,164,164
BEGIN DESCRIPTION:
UNT 013 IN UKCR 23.0
END DESCRIPTION:
XS GIS Cut Line= 3
      3582499.62     10590210.21      3582349.61     10589810.19
      3581749.62     10589160.20
#Sta/Elev= 30
  4571.2  430.12  4733.8  424.60  4785.1  421.80  4827.5  419.58  4928.1  408.94
  4983.3  408.45  4988.6  407.96  4992.8  403.90  4995.5  403.40  4998.8  403.90
  5001.8  403.90  5005.5  407.68  5012.3  407.15  5019.7  409.14  5118.9  408.66
  5147.3  407.04  5161.4  408.41  5230.6  408.48  5260.1  408.27  5366.2  414.61
  5670.7  424.57  5727.4  428.92  5734.2  427.09  5748.3  427.09  5755.7  429.03
  5769.9  429.17  5776.7  426.48  5833.4  429.57  5861.7  436.17  5883.0  433.26
#Mann=6,-1,0
  4571.2    0.16       0  4733.8    0.12       0  4785.1    0.16       0
  4992.8    0.07       0  4998.8    0.16       0  5230.6    0.05       0
Bank Sta=4992.8,4998.8
Exp/Cntr=0.3,0.1

Type RM Length L Ch R = 1,12702,571,571,571
BEGIN DESCRIPTION:
Mapping XS 2b293f8d
END DESCRIPTION:
XS GIS Cut Line= 3
      3582511.76     10590215.93      3582507.42     10589669.02
      3581865.05     10589165.54
#Sta/Elev= 30
  4563.7  429.70  4599.4  429.56  4659.4  427.97  4789.4  422.77  4819.4  420.76
  4909.5  417.62  4959.5  413.45  4969.5  410.72  4979.5  409.15  4989.5  404.82
  4996.5  403.16  4999.2  402.66  5002.5  403.16  5009.5  407.75  5019.5  408.64
  5049.5  407.88  5155.0  407.63  5258.3  406.67  5308.1  408.07  5349.7  407.34
  5407.5  409.67  5413.9  408.72  5507.0  410.83  5635.4  415.77  5664.3  416.23
  5749.3  420.96  5763.7  422.89  5784.5  423.90  5842.4  428.76  5926.8  432.19
#Mann=4,-1,0
  4563.7    0.16       0  4996.5    0.07       0  5002.5    0.16       0
  5155.0    0.05       0
Bank Sta=4996.5,5002.5
Exp/Cntr=0.3,0.1