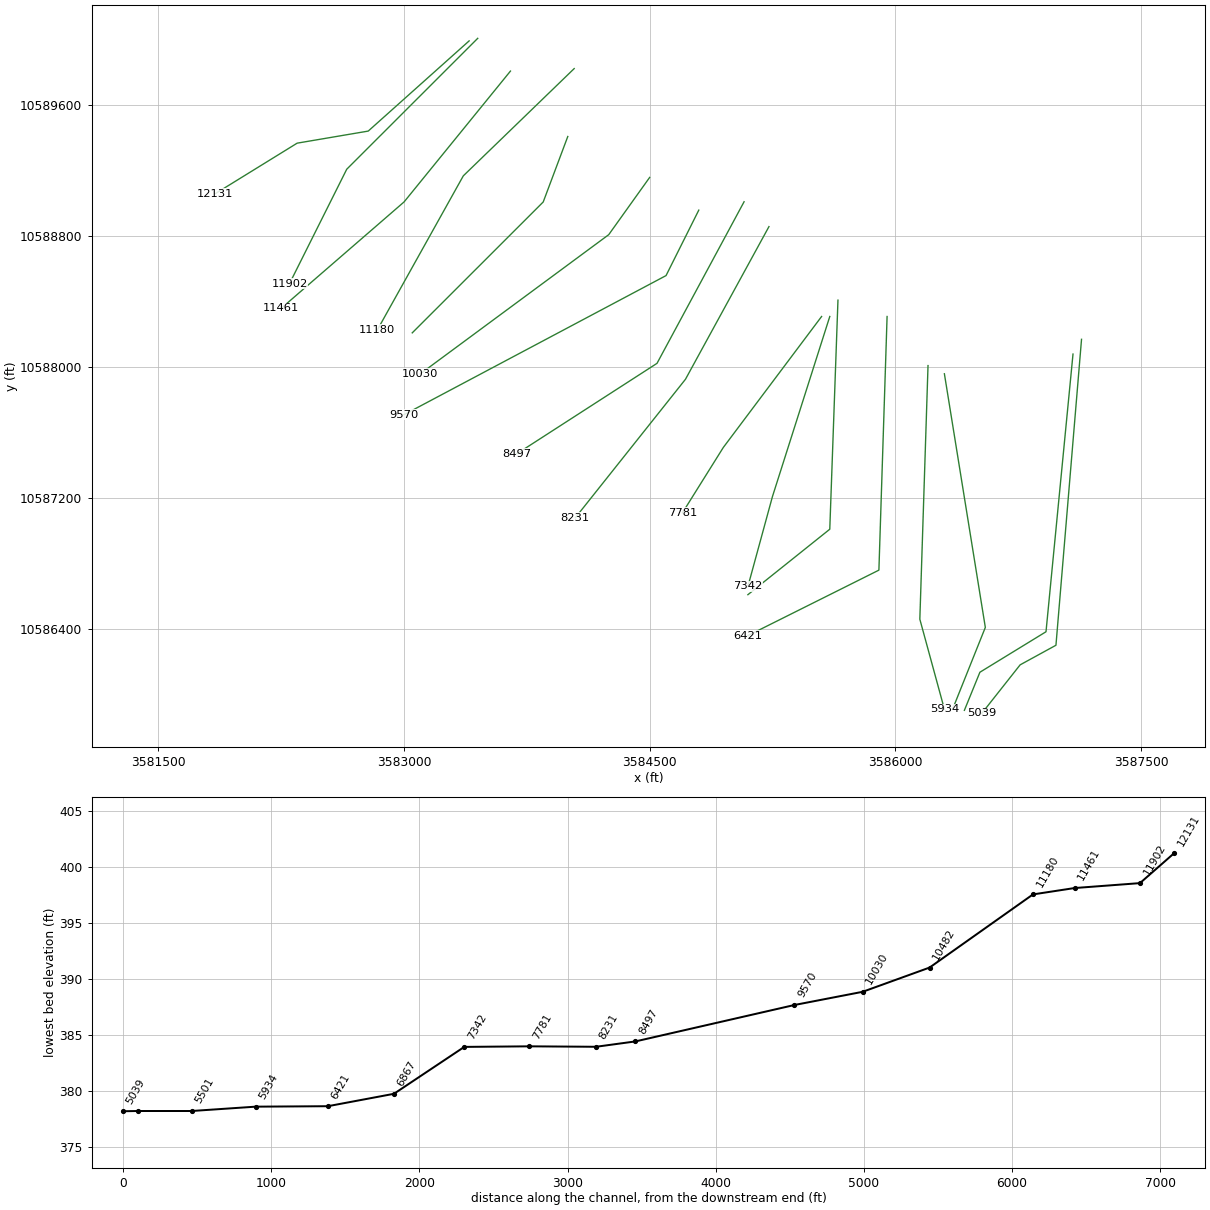
HEC-RAS study UNT 013 IN UKCR.prj: UNT 013 IN UKCR Base Level Engineering

--- UNT 013 IN UKCR.g01 (geometry) --- (continued)

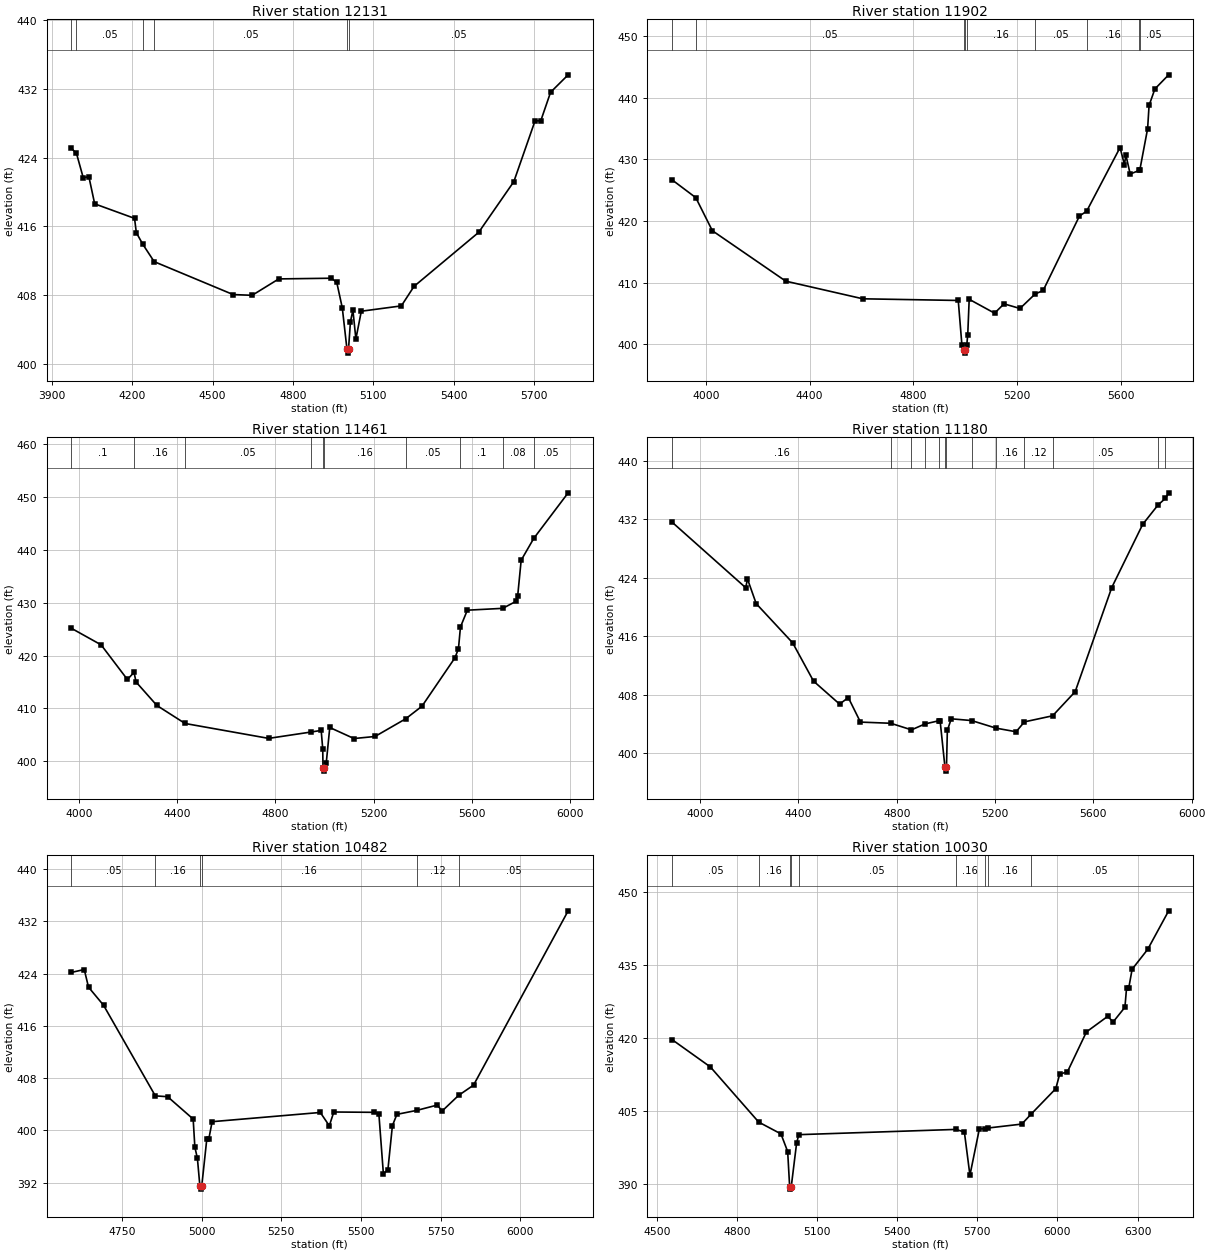
Type RM Length L Ch R = 1,12131,229,229,229
BEGIN DESCRIPTION:
UNT 013 IN UKCR 22.0
END DESCRIPTION:
XS GIS Cut Line= 4
      3583397.19     10589994.55      3582780.86     10589443.33
      3582346.83     10589369.54      3581847.72     10589061.39
#Sta/Elev= 30
  3973.2  425.07  3991.8  424.49  4017.1  421.65  4038.0  421.79  4059.7  418.62
  4208.5  416.93  4215.2  415.26  4239.6  413.90  4281.8  411.89  4576.3  408.06
  4647.4  407.97  4746.8  409.88  4943.3  409.96  4963.3  409.47  4983.9  406.51
  5001.2  401.74  5004.0  401.24  5007.2  401.74  5014.3  404.90  5023.5  406.24
  5034.6  402.89  5054.9  406.12  5204.3  406.74  5251.6  409.01  5492.9  415.30
  5624.2  421.21  5703.4  428.29  5724.6  428.28  5761.3  431.61  5826.9  433.64
#Mann=6,-1,0
  3973.2     0.1       0  3991.8    0.05       0  4239.6     0.1       0
  4281.8    0.05       0  5001.2    0.03       0  5007.2    0.05       0
Bank Sta=5001.2,5007.2
Exp/Cntr=0.3,0.1

Type RM Length L Ch R = 1,11902,441,441,441
BEGIN DESCRIPTION:
UNT 013 IN UKCR 21.0
END DESCRIPTION:
XS GIS Cut Line= 3
      3583449.59     10590010.16      3582649.61     10589210.19
      3582299.59     10588510.15
#Sta/Elev= 30
  3869.8  426.69  3961.5  423.79  4025.3  418.43  4308.2  410.25  4605.2  407.39
  4972.9  407.12  4987.0  399.91  4994.6  399.08  4997.4  398.58  5000.6  399.08
  5005.9  399.97  5009.5  401.56  5015.1  407.31  5112.9  405.06  5149.3  406.57
  5210.8  405.82  5269.0  408.16  5300.2  408.74  5440.0  420.81  5467.8  421.60
  5596.5  431.92  5613.3  429.15  5618.9  430.70  5635.6  427.62  5669.5  428.20
  5672.8  428.31  5702.7  434.98  5708.3  438.74  5730.7  441.42  5783.8  443.71
#Mann=9,-1,0
  3869.8     0.1       0  3961.5    0.05       0  4994.6    0.03       0
  5000.6    0.05       0  5005.9    0.16       0  5269.0    0.05       0
  5467.8    0.16       0  5669.5    0.08       0  5672.8    0.05       0
Bank Sta=4994.6,5000.6
Exp/Cntr=0.3,0.1

Type RM Length L Ch R = 1,11461,281,281,281
BEGIN DESCRIPTION:
UNT 013 IN UKCR 20.0
END DESCRIPTION:
XS GIS Cut Line= 3
      3583649.58     10589810.15      3582999.61     10589010.19
      3582249.61     10588360.19
#Sta/Elev= 30
  3969.7  425.17  4090.3  422.05  4197.4  415.49  4224.5  416.84  4232.6  415.02
  4317.5  410.57  4432.4  407.16  4772.7  404.34  4946.5  405.55  4986.8  405.85
  4993.2  402.32  4994.2  398.64  4997.0  398.14  5000.2  398.64  5007.6  399.76
  5021.8  406.40  5120.5  404.31  5206.1  404.70  5331.2  408.05  5397.4  410.43
  5531.8  419.60  5546.0  421.31  5554.2  425.43  5582.2  428.61  5726.3  428.96
  5780.7  430.29  5787.3  431.32  5801.5  438.07  5852.9  442.21  5992.9  450.83
#Mann=10,-1,0
  3969.7     0.1       0  4224.5    0.16       0  4432.4    0.05       0
  4946.5    0.16       0  4994.2    0.07       0  5000.2    0.16       0
  5331.2    0.05       0  5554.2     0.1       0  5726.3    0.08       0
  5852.9    0.05       0
Bank Sta=4994.2,5000.2
Exp/Cntr=0.3,0.1

Type RM Length L Ch R = 1,11180,698,698,698
BEGIN DESCRIPTION:
UNT 013 IN UKCR 19.0
END DESCRIPTION:
XS GIS Cut Line= 3
      3584038.74     10589825.27      3583361.67     10589169.90
      3582836.48     10588228.03
#Sta/Elev= 30
  3885.7  431.60  4185.7  422.63  4192.7  423.84  4228.2  420.46  4376.6  415.10
  4461.5  409.87  4567.5  406.73  4603.0  407.62  4652.4  404.27  4775.7  404.11
  4860.1  403.21  4915.0  404.02  4972.4  404.46  4976.5  404.45  4996.4  398.07
  4999.2  397.57  5002.4  398.07  5006.0  403.13  5021.9  404.72  5104.7  404.48
  5204.6  403.44  5285.7  402.95  5319.4  404.30  5434.2  405.13  5526.1  408.43
  5674.9  422.66  5800.9  431.30  5863.7  433.96  5893.4  434.85  5906.4  435.60
#Mann=13,-1,0
  3885.7    0.16       0  4775.7    0.05       0  4860.1    0.16       0
  4915.0    0.05       0  4972.4    0.16       0  4996.4    0.07       0
  5002.4    0.16       0  5104.7    0.12       0  5204.6    0.16       0
  5319.4    0.12       0  5434.2    0.05       0  5863.7    0.16       0
  5893.4    0.05       0
Bank Sta=4996.4,5002.4
Exp/Cntr=0.3,0.1

Type RM Length L Ch R = 1,10482,452,452,452
BEGIN DESCRIPTION:
UNT 013 IN UKCR 18.0
END DESCRIPTION:
XS GIS Cut Line= 3
      3583999.60     10589410.16      3583849.61     10589010.19
      3583049.64     10588210.22
#Sta/Elev= 30
  4592.0  424.18  4632.0  424.62  4645.4  421.92  4692.5  419.16  4855.0  405.29
  4893.7  405.16  4973.8  401.74  4979.1  397.44  4987.1  395.73  4994.8  391.52
  4997.6  391.02  5000.8  391.52  5016.5  398.65  5022.7  398.65  5033.3  401.34
  5372.7  402.75  5401.0  400.71  5415.1  402.82  5542.4  402.77  5556.6  402.49
  5570.7  393.36  5584.9  394.01  5599.0  400.73  5613.1  402.46  5675.7  403.07
  5740.4  403.89  5754.6  402.95  5806.9  405.37  5853.6  406.93  6150.5  433.60
#Mann=6,-1,0
  4592.0    0.05       0  4855.0    0.16       0  4994.8    0.07       0
  5000.8    0.16       0  5675.7    0.12       0  5806.9    0.05       0
Bank Sta=4994.8,5000.8
Exp/Cntr=0.3,0.1

Type RM Length L Ch R = 1,10030,460,460,460
BEGIN DESCRIPTION:
UNT 013 IN UKCR 17.0
END DESCRIPTION:
XS GIS Cut Line= 3
      3584499.59     10589160.16      3584249.61     10588810.19
      3583099.62     10587960.20
#Sta/Elev= 30
  4556.4  419.66  4700.1  414.02  4881.1  402.66  4964.4  400.23  4989.6  396.59
  4997.0  389.35  4999.8  388.85  5003.0  389.35  5023.1  398.34  5031.3  400.07
  5619.1  401.15  5651.4  400.62  5672.2  391.72  5707.7  401.29  5728.3  401.26
  5738.6  401.43  5866.4  402.25  5902.6  404.37  5993.7  409.54  6008.3  412.51
  6037.6  413.04  6108.6  421.24  6187.9  424.43  6208.8  423.30  6252.7  426.32
  6258.9  430.33  6267.3  430.38  6279.7  434.15  6338.2  438.26  6416.5  446.18
#Mann=9,-1,0
  4556.4    0.05       0  4881.1    0.16       0  4997.0    0.07       0
  5003.0    0.16       0  5031.3    0.05       0  5619.1    0.16       0
  5728.3    0.12       0  5738.6    0.16       0  5902.6    0.05       0
Bank Sta=4997,5003
Exp/Cntr=0.3,0.1

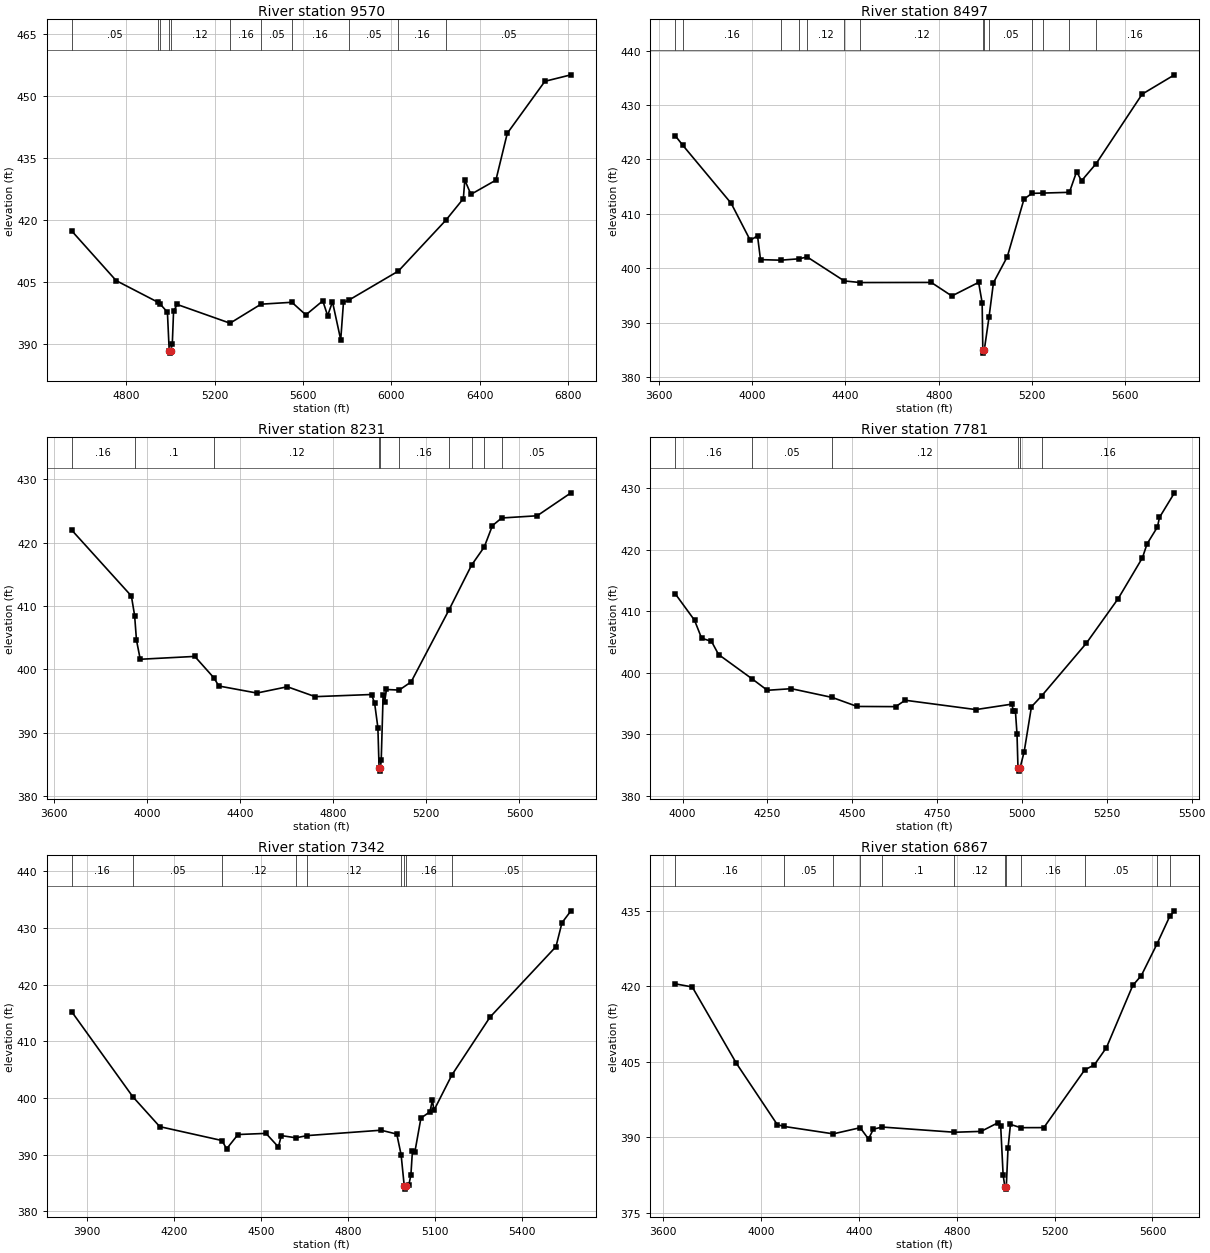
Type RM Length L Ch R = 1,9570,1073,1073,1073
BEGIN DESCRIPTION:
UNT 013 IN UKCR 16.0
END DESCRIPTION:
XS GIS Cut Line= 3
      3584799.63     10588960.23      3584599.61     10588560.19
      3582999.63     10587710.20
#Sta/Elev= 30
  4553.2  417.32  4754.5  405.26  4945.5  399.96  4952.1  399.67  4986.5  397.60
  4994.7  388.17  4997.4  387.67  5000.7  388.17  5008.6  389.91  5014.3  397.79
  5030.6  399.47  5269.8  394.93  5409.9  399.54  5549.6  400.00  5612.8  396.94
  5689.4  400.35  5711.3  396.76  5733.3  400.12  5770.5  390.90  5783.0  399.99
  5805.9  400.48  6031.6  407.58  6246.6  419.93  6325.3  425.13  6331.8  429.65
  6359.5  426.17  6472.5  429.62  6524.0  440.98  6694.2  453.59  6812.2  455.16
#Mann=11,-1,0
  4553.2    0.05       0  4945.5     0.1       0  4952.1    0.12       0
  4994.7    0.07       0  5000.7    0.12       0  5269.8    0.16       0
  5409.9    0.05       0  5549.6    0.16       0  5805.9    0.05       0
  6031.6    0.16       0  6246.6    0.05       0
Bank Sta=4994.7,5000.7
Exp/Cntr=0.3,0.1

Type RM Length L Ch R = 1,8497,266,266,266
BEGIN DESCRIPTION:
UNT 013 IN UKCR 15.0
END DESCRIPTION:
XS GIS Cut Line= 3
      3585076.24     10589011.44      3584544.54     10588023.99
      3583687.34     10587470.61
#Sta/Elev= 30
  3669.4  424.39  3703.1  422.57  3909.9  411.94  3991.9  405.13  4022.9  405.98
  4035.7  401.59  4122.1  401.49  4200.3  401.74  4235.9  402.08  4394.7  397.68
  4463.5  397.38  4768.2  397.40  4856.3  394.91  4971.2  397.41  4986.4  393.67
  4989.3  384.91  4992.1  384.41  4995.3  384.91  5016.2  391.13  5034.8  397.35
  5094.3  402.13  5165.8  412.70  5199.7  413.77  5245.9  413.82  5360.7  413.96
  5391.5  417.75  5412.7  416.08  5475.5  419.24  5672.7  432.00  5811.2  435.55
#Mann=14,-1,0
  3669.4    0.05       0  3703.1    0.16       0  4122.1     0.1       0
  4200.3    0.05       0  4235.9    0.12       0  4394.7    0.07       0
  4463.5    0.12       0  4989.3    0.07       0  4995.3    0.12       0
  5016.2    0.05       0  5199.7     0.1       0  5245.9    0.15       0
  5360.7    0.08       0  5475.5    0.16       0
Bank Sta=4989.3,4995.3
Exp/Cntr=0.3,0.1

Type RM Length L Ch R = 1,8231,450,450,450
BEGIN DESCRIPTION:
UNT 013 IN UKCR 14.0
END DESCRIPTION:
XS GIS Cut Line= 3
      3585228.16     10588859.53      3584718.16     10587926.34
      3584045.42     10587080.00
#Sta/Elev= 30
  3676.6  421.98  3933.2  411.56  3947.1  408.48  3955.1  404.59  3971.2  401.58
  4205.5  402.03  4287.3  398.66  4308.9  397.36  4472.1  396.25  4603.1  397.24
  4722.6  395.68  4964.7  396.02  4977.9  394.64  4991.9  390.79  4997.0  384.43
  4999.7  383.93  5003.0  384.43  5006.3  385.76  5014.4  395.92  5020.8  394.83
  5028.8  396.81  5083.4  396.72  5134.5  398.00  5297.3  409.37  5394.2  416.43
  5448.8  419.30  5483.7  422.66  5523.5  423.87  5676.0  424.22  5821.2  427.84
#Mann=10,-1,0
  3676.6    0.16       0  3947.1     0.1       0  4287.3    0.12       0
  4997.0    0.07       0  5003.0    0.12       0  5083.4    0.16       0
  5297.3     0.1       0  5394.2    0.05       0  5448.8    0.08       0
  5523.5    0.05       0
Bank Sta=4997,5003
Exp/Cntr=0.3,0.1

Type RM Length L Ch R = 1,7781,439,439,439
BEGIN DESCRIPTION:
UNT 013 IN UKCR 13.0
END DESCRIPTION:
XS GIS Cut Line= 3
      3585549.58     10588310.15      3584949.61     10587510.19
      3584699.64     10587110.23
#Sta/Elev= 30
  3977.7  412.85  4034.9  408.52  4055.8  405.59  4084.9  405.08  4105.8  402.94
  4204.8  398.97  4249.5  397.12  4320.4  397.38  4441.1  395.95  4514.1  394.49
  4627.7  394.46  4655.8  395.50  4864.1  393.98  4970.4  394.87  4974.5  393.73
  4980.6  393.73  4985.3  390.02  4988.2  384.47  4991.0  383.97  4994.2  384.47
  5006.5  387.15  5027.8  394.43  5058.6  396.25  5189.3  404.75  5283.7  412.05
  5355.0  418.68  5368.6  420.94  5399.2  423.68  5405.1  425.23  5449.3  429.24
#Mann=6,-1,0
  3977.7    0.16       0  4204.8    0.05       0  4441.1    0.12       0
  4988.2    0.07       0  4994.2    0.12       0  5058.6    0.16       0
Bank Sta=4988.2,4994.2
Exp/Cntr=0.3,0.1

Type RM Length L Ch R = 1,7342,475,475,475
BEGIN DESCRIPTION:
UNT 013 IN UKCR 12.0
END DESCRIPTION:
XS GIS Cut Line= 3
      3585599.61     10588310.18      3585249.61     10587210.19
      3585099.61     10586660.21
#Sta/Elev= 30
  3845.7  415.26  4056.8  400.24  4150.0  394.95  4364.8  392.50  4380.9  391.03
  4420.2  393.56  4516.9  393.76  4559.7  391.36  4569.8  393.37  4620.5  392.98
  4658.9  393.37  4914.2  394.32  4968.5  393.64  4983.5  389.99  4994.4  384.42
  4997.2  383.92  5000.4  384.42  5010.4  384.73  5017.3  386.42  5022.5  390.62
  5031.1  390.51  5051.9  396.46  5083.0  397.57  5091.6  399.66  5096.8  397.82
  5158.7  404.06  5290.3  414.27  5518.3  426.73  5539.0  430.95  5570.1  433.05
#Mann=9,-1,0
  3845.7    0.16       0  4056.8    0.05       0  4364.8    0.12       0
  4620.5    0.07       0  4658.9    0.12       0  4983.5    0.16       0
  4994.4    0.07       0  5000.4    0.16       0  5158.7    0.05       0
Bank Sta=4994.4,5000.4
Exp/Cntr=0.3,0.1

Type RM Length L Ch R = 1,6867,446,446,446
BEGIN DESCRIPTION:
UNT 013 IN UKCR 11.0
END DESCRIPTION:
XS GIS Cut Line= 3
      3585649.61     10588410.24      3585599.61     10587010.19
      3585099.57     10586610.16
#Sta/Elev= 30
  3648.6  420.47  3718.7  419.85  3898.8  404.72  4066.4  392.52  4093.0  392.17
  4295.1  390.69  4405.2  391.91  4439.2  389.67  4459.2  391.63  4495.7  392.04
  4790.5  391.01  4899.4  391.18  4969.5  392.92  4979.5  392.32  4989.5  382.57
  4996.5  380.22  4999.3  379.72  5002.5  380.22  5009.5  387.80  5019.5  392.57
  5061.3  391.92  5156.0  391.93  5323.0  403.38  5362.5  404.39  5412.1  407.83
  5519.4  420.14  5554.6  422.12  5617.6  428.29  5670.9  433.89  5689.9  434.96
#Mann=12,-1,0
  3648.6    0.16       0  4093.0    0.05       0  4295.1    0.12       0
  4405.2    0.07       0  4495.7     0.1       0  4790.5    0.12       0
  4996.5    0.07       0  5002.5    0.12       0  5061.3    0.16       0
  5323.0    0.05       0  5617.6    0.16       0  5670.9    0.05       0
Bank Sta=4996.5,5002.5
Exp/Cntr=0.3,0.1

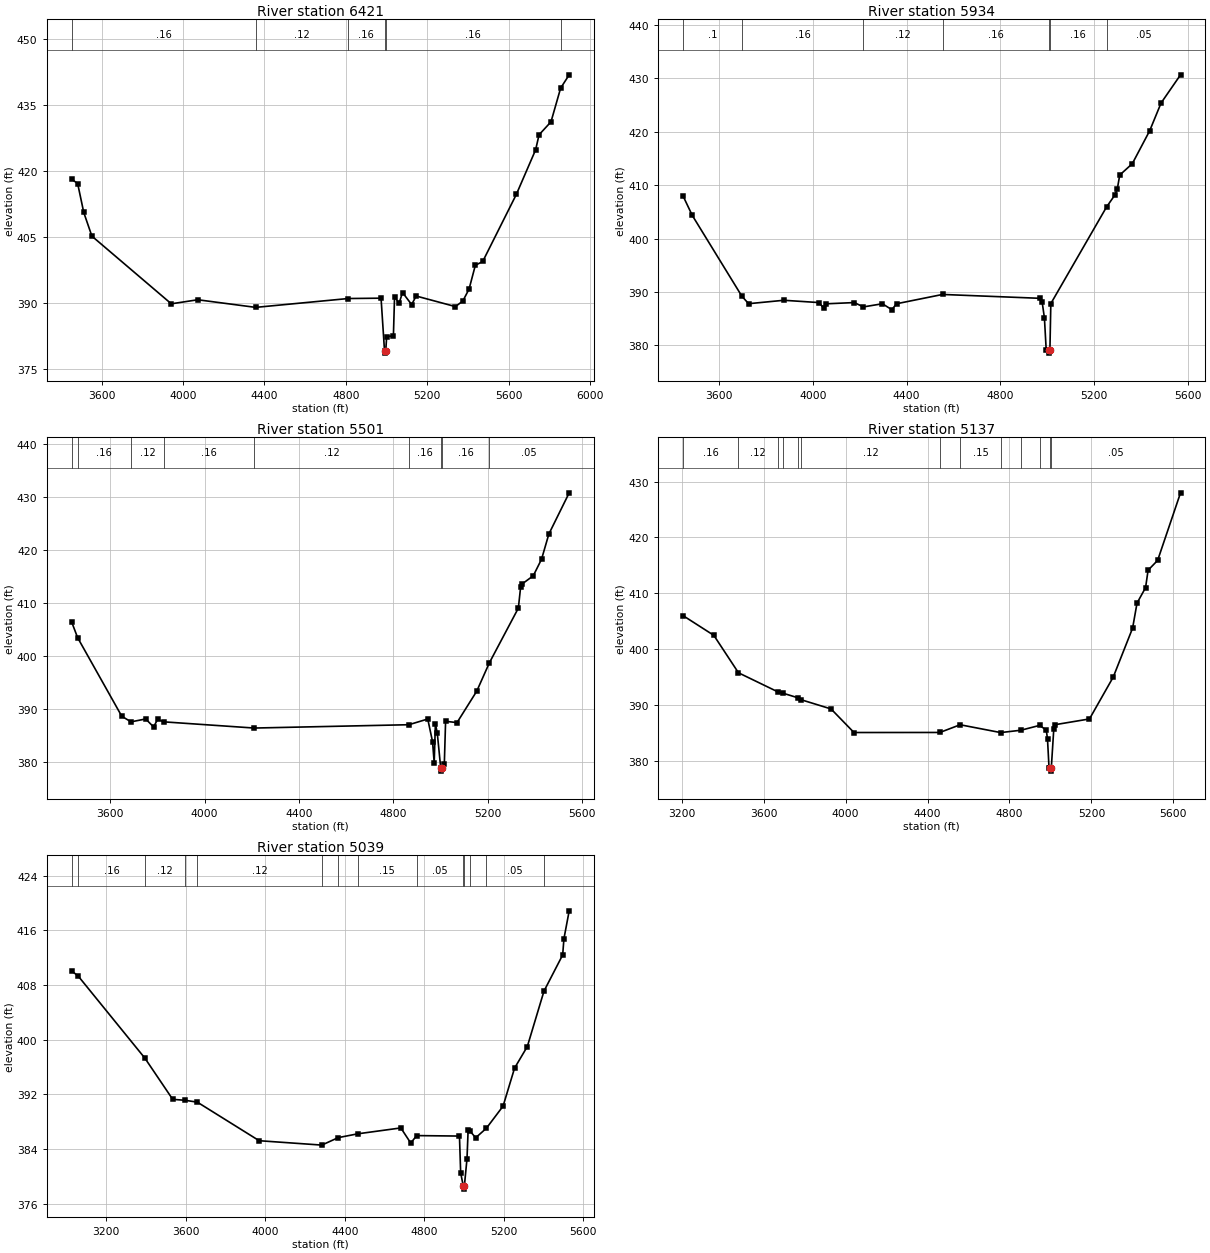
Type RM Length L Ch R = 1,6421,487,487,487
BEGIN DESCRIPTION:
UNT 013 IN UKCR 10.0
END DESCRIPTION:
XS GIS Cut Line= 3
      3585949.61     10588310.16      3585899.61     10586760.19
      3585099.61     10586360.19
#Sta/Elev= 30
  3452.2  418.16  3482.2  417.16  3512.2  410.58  3552.2  405.20  3942.4  389.82
  4072.5  390.74  4356.8  389.01  4811.4  391.02  4973.0  391.10  4990.0  379.11
  4992.7  378.61  4996.0  379.11  5000.5  382.33  5033.7  382.59  5039.3  391.44
  5061.7  389.94  5078.4  392.39  5123.2  389.65  5145.5  391.59  5338.4  389.19
  5374.7  390.45  5405.5  393.18  5436.2  398.57  5472.5  399.44  5637.5  414.67
  5732.5  424.83  5749.3  428.24  5808.0  431.19  5855.3  438.85  5897.4  441.87
#Mann=6,-1,0
  3452.2    0.16       0  4356.8    0.12       0  4811.4    0.16       0
  4990.0    0.07       0  4996.0    0.16       0  5855.3    0.05       0
Bank Sta=4990,4996
Exp/Cntr=0.3,0.1

Type RM Length L Ch R = 1,5934,433,433,433
BEGIN DESCRIPTION:
UNT 013 IN UKCR 9.0
END DESCRIPTION:
XS GIS Cut Line= 3
      3586199.61     10588010.17      3586149.61     10586460.19
      3586299.61     10585910.17
#Sta/Elev= 30
  3446.8  408.04  3486.8  404.34  3698.2  389.22  3726.9  387.82  3877.0  388.46
  4027.1  388.03  4047.1  386.97  4057.1  387.80  4177.2  388.03  4216.2  387.22
  4297.2  387.81  4337.2  386.70  4357.3  387.81  4553.6  389.55  4967.6  388.83
  4977.6  388.23  4987.6  385.16  4995.1  379.24  5005.0  379.07  5007.7  378.57
  5011.0  379.07  5014.9  387.84  5252.8  405.95  5287.8  408.15  5298.2  409.27
  5308.5  411.89  5362.1  414.02  5436.4  420.20  5484.8  425.38  5567.7  430.65
#Mann=7,-1,0
  3446.8     0.1       0  3698.2    0.16       0  4216.2    0.12       0
  4553.6    0.16       0  5005.0    0.07       0  5011.0    0.16       0
  5252.8    0.05       0
Bank Sta=5005,5011
Exp/Cntr=0.3,0.1

Type RM Length L Ch R = 1,5501,364,364,364
BEGIN DESCRIPTION:
UNT 013 IN UKCR 8.0
END DESCRIPTION:
XS GIS Cut Line= 3
      3586299.60     10587960.22      3586549.61     10586410.19
      3586349.60     10585910.17
#Sta/Elev= 30
  3436.6  406.46  3462.4  403.42  3649.3  388.57  3688.7  387.50  3750.6  388.05
  3784.1  386.55  3801.3  387.95  3828.5  387.50  4210.6  386.33  4866.0  386.96
  4945.9  388.04  4966.1  383.77  4973.2  379.77  4978.3  387.16  4986.4  385.32
  5001.1  378.68  5003.9  378.18  5007.1  378.68  5016.1  379.50  5021.5  387.61
  5069.9  387.36  5153.4  393.30  5207.1  398.68  5329.8  409.02  5339.2  412.92
  5344.6  413.55  5393.0  415.14  5428.1  418.27  5459.0  423.03  5545.2  430.83
#Mann=9,-1,0
  3436.6     0.1       0  3462.4    0.16       0  3688.7    0.12       0
  3828.5    0.16       0  4210.6    0.12       0  4866.0    0.16       0
  5001.1    0.07       0  5007.1    0.16       0  5207.1    0.05       0
Bank Sta=5001.1,5007.1
Exp/Cntr=0.3,0.1

Type RM Length L Ch R = 1,5137,98,98,98
BEGIN DESCRIPTION:
Mapping XS de6cba4c
END DESCRIPTION:
XS GIS Cut Line= 4
      3587085.02     10588080.62      3586920.10     10586383.62
      3586516.45     10586136.22      3586421.65     10585903.52
#Sta/Elev= 30
  3205.5  406.03  3356.6  402.48  3476.9  395.78  3670.1  392.35  3693.1  392.14
  3767.8  391.30  3781.7  390.97  3928.9  389.31  4040.8  385.09  4460.2  385.10
  4559.2  386.48  4757.0  385.08  4855.9  385.50  4947.7  386.37  4979.8  385.51
  4985.7  383.92  4993.2  378.72  4998.1  378.68  5000.9  378.18  5004.1  378.68
  5016.5  385.80  5022.4  386.49  5190.6  387.52  5306.7  395.02  5401.2  403.78
  5422.8  408.26  5464.5  411.02  5476.8  414.14  5523.4  415.90  5635.2  427.99
#Mann=13,-1,0
  3205.5    0.16       0  3476.9    0.12       0  3670.1    0.07       0
  3693.1     0.1       0  3767.8    0.07       0  3781.7    0.12       0
  4460.2    0.07       0  4559.2    0.15       0  4757.0    0.07       0
  4855.9    0.05       0  4947.7    0.12       0  4998.1    0.07       0
  5004.1    0.05       0
Bank Sta=4998.1,5004.1
Exp/Cntr=0.3,0.1

Type RM Length L Ch R = 1,5039,155,155,155
BEGIN DESCRIPTION:
Mapping XS d105a2f8
END DESCRIPTION:
XS GIS Cut Line= 4
      3587137.11     10588170.89      3586980.86     10586301.15
      3586762.11     10586181.36      3586527.98     10585884.80
#Sta/Elev= 30
  3025.9  410.08  3059.3  409.32  3395.2  397.30  3534.8  391.29  3597.5  391.15
  3658.7  390.88  3969.9  385.24  4284.8  384.60  4367.3  385.69  4466.0  386.25
  4682.4  387.11  4732.3  384.90  4762.2  385.99  4977.4  385.92  4983.4  380.56
  4996.2  378.66  4998.9  378.16  5002.2  378.66  5015.3  382.60  5021.0  386.83
  5030.4  386.66  5058.9  385.67  5113.0  387.07  5196.8  390.30  5254.6  395.86
  5318.7  399.01  5402.6  407.12  5496.6  412.41  5503.0  414.79  5529.4  418.86
#Mann=14,-1,0
  3025.9    0.12       0  3059.3    0.16       0  3395.2    0.12       0
  3597.5    0.07       0  3658.7    0.12       0  4284.8    0.07       0
  4367.3    0.08       0  4466.0    0.15       0  4762.2    0.05       0
  4996.2   0.035       0  5002.2    0.05       0  5030.4    0.16       0
  5113.0    0.05       0  5402.6     0.1       0
Bank Sta=4996.2,5002.2
Exp/Cntr=0.3,0.1