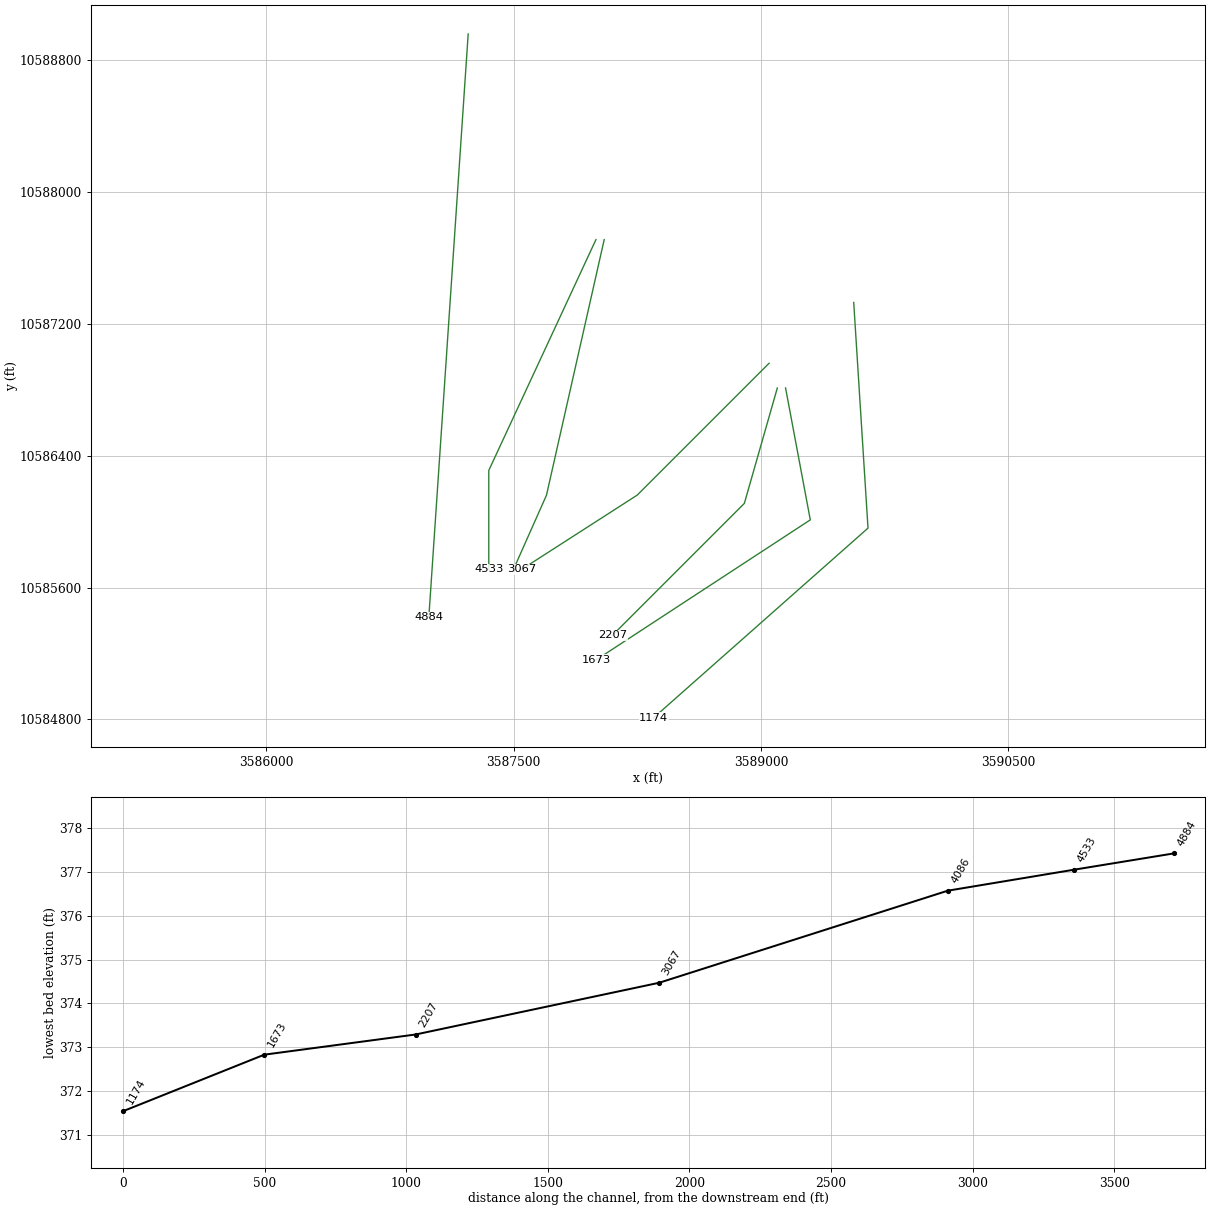
HEC-RAS study UNT 013 IN UKCR.prj: UNT 013 IN UKCR Base Level Engineering

--- UNT 013 IN UKCR.g01 (geometry) --- (continued)

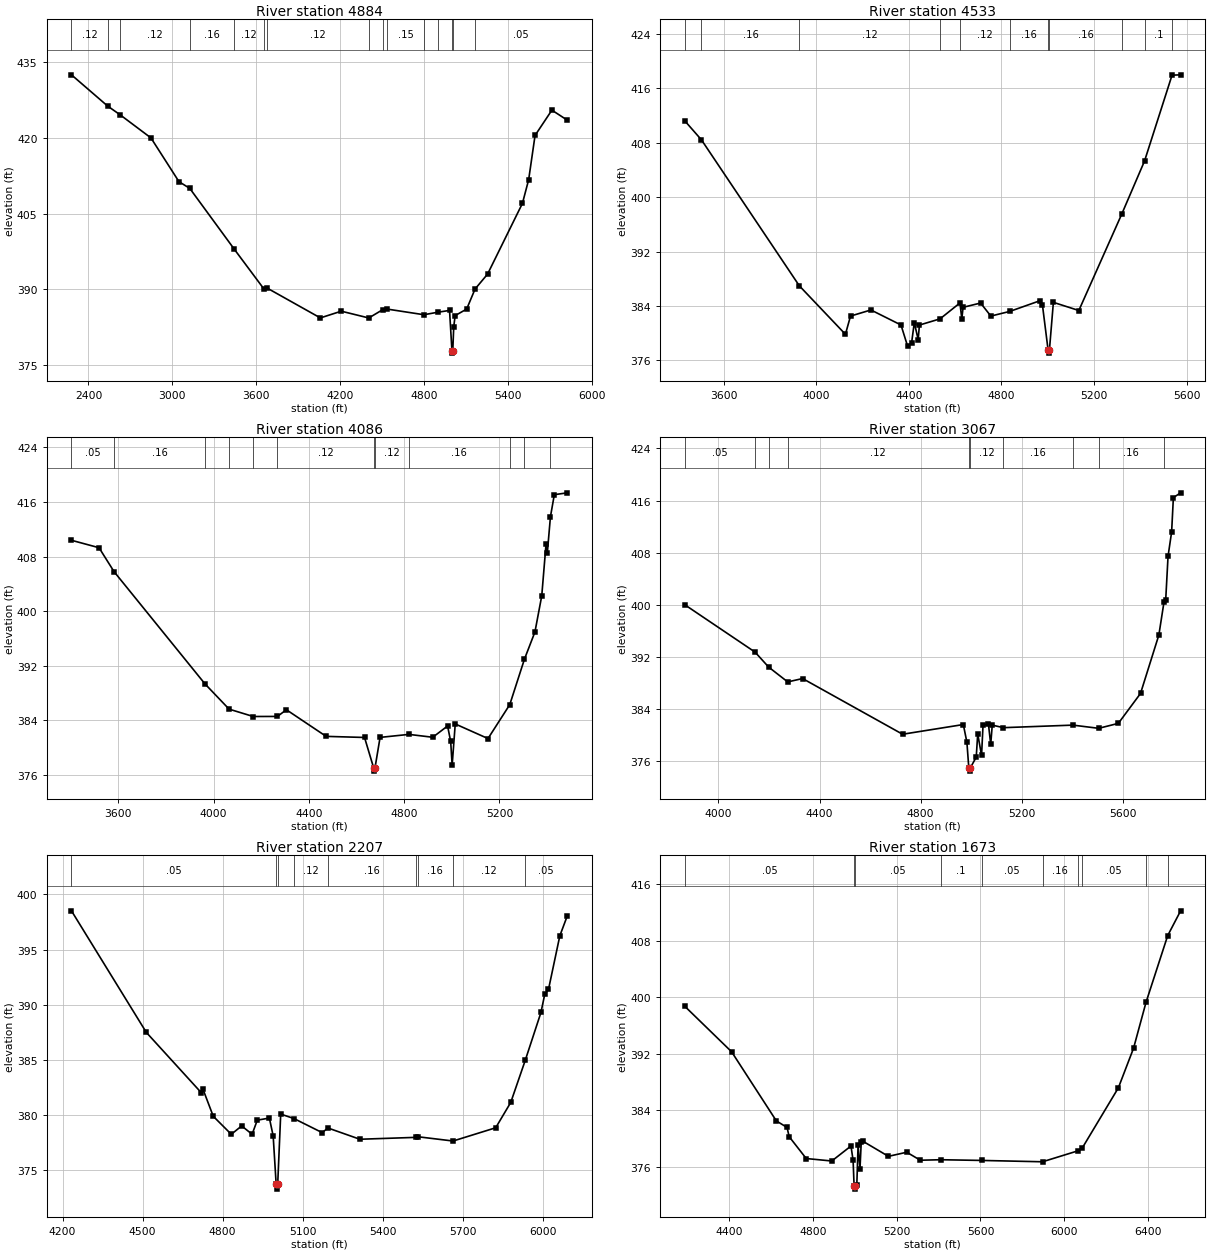
Type RM Length L Ch R = 1,4884,351,351,351
BEGIN DESCRIPTION:
UNT 013 IN UKCR 7.0
END DESCRIPTION:
XS GIS Cut Line= 2
      3587224.67     10588957.17      3586985.95     10585419.81
#Sta/Elev= 30
  2278.4  432.43  2537.0  426.26  2627.7  424.50  2846.7  419.96  3047.1  411.31
  3124.1  409.99  3441.7  397.99  3652.0  390.19  3678.6  390.26  4057.9  384.38
  4207.4  385.71  4404.0  384.37  4502.6  385.99  4534.4  386.13  4798.3  385.01
  4896.8  385.50  4981.5  385.86  4998.6  377.92  5001.3  377.42  5004.6  377.92
  5011.6  382.66  5021.6  384.84  5104.0  386.13  5163.9  390.09  5253.4  393.04
  5502.7  407.03  5547.2  411.71  5592.9  420.45  5713.2  425.45  5823.8  423.46
#Mann=15,-1,0
  2278.4    0.12       0  2537.0    0.16       0  2627.7    0.12       0
  3124.1    0.16       0  3441.7    0.12       0  3652.0    0.07       0
  3678.6    0.12       0  4404.0    0.07       0  4502.6     0.1       0
  4534.4    0.15       0  4798.3    0.05       0  4896.8    0.16       0
  4998.6    0.07       0  5004.6    0.16       0  5163.9    0.05       0
Bank Sta=4998.6,5004.6
Exp/Cntr=0.3,0.1

Type RM Length L Ch R = 1,4533,447,447,447
BEGIN DESCRIPTION:
UNT 013 IN UKCR 6.0
END DESCRIPTION:
XS GIS Cut Line= 3
      3587999.60     10587710.17      3587349.61     10586310.19
      3587349.61     10585710.20
#Sta/Elev= 30
  3430.9  411.23  3503.3  408.42  3926.3  386.95  4125.5  379.82  4147.5  382.50
  4235.7  383.40  4365.7  381.19  4394.1  378.09  4411.5  378.55  4423.2  381.54
  4439.9  379.05  4445.4  381.18  4534.5  382.09  4620.5  384.43  4628.6  382.07
  4634.1  383.79  4709.8  384.42  4754.1  382.50  4836.2  383.19  4965.7  384.75
  4976.9  384.19  5001.4  377.55  5004.2  377.05  5007.4  377.55  5024.4  384.52
  5134.4  383.32  5320.4  397.54  5418.5  405.32  5537.3  417.94  5574.4  417.99
#Mann=11,-1,0
  3430.9    0.05       0  3503.3    0.16       0  3926.3    0.12       0
  4534.5    0.07       0  4620.5    0.12       0  4836.2    0.16       0
  5001.4    0.07       0  5007.4    0.16       0  5320.4    0.05       0
  5418.5     0.1       0  5537.3    0.15       0
Bank Sta=5001.4,5007.4
Exp/Cntr=0.3,0.1

Type RM Length L Ch R = 1,4086,1019,1019,1019
BEGIN DESCRIPTION:
UNT 013 IN UKCR 5.0
END DESCRIPTION:
XS GIS Cut Line= 3
      3588049.61     10587710.19      3587699.61     10586160.19
      3587499.60     10585710.16
#Sta/Elev= 30
  3403.4  410.38  3519.1  409.29  3582.3  405.78  3963.5  389.36  4065.0  385.65
  4166.4  384.57  4267.9  384.58  4305.6  385.56  4472.5  381.66  4633.6  381.50
  4671.6  377.07  4674.4  376.57  4677.6  377.07  4698.8  381.51  4819.9  381.95
  4919.9  381.53  4982.2  383.18  4995.2  380.91  5001.3  377.43  5014.3  383.48
  5151.8  381.34  5243.2  386.31  5304.7  392.96  5348.8  396.95  5377.5  402.26
  5395.3  409.78  5400.7  408.48  5413.9  413.83  5430.2  417.06  5484.9  417.33
#Mann=12,-1,0
  3403.4    0.05       0  3582.3    0.16       0  3963.5    0.07       0
  4065.0    0.16       0  4166.4    0.05       0  4267.9    0.12       0
  4671.6    0.07       0  4677.6    0.12       0  4819.9    0.16       0
  5243.2    0.05       0  5304.7    0.08       0  5413.9     0.1       0
Bank Sta=4671.6,4677.6
Exp/Cntr=0.3,0.1

Type RM Length L Ch R = 1,3067,860,860,860
BEGIN DESCRIPTION:
UNT 013 IN UKCR 4.0
END DESCRIPTION:
XS GIS Cut Line= 3
      3589049.62     10586960.20      3588249.61     10586160.19
      3587549.65     10585710.21
#Sta/Elev= 30
  3866.3  400.01  4145.0  392.73  4198.5  390.44  4274.1  388.16  4333.0  388.68
  4729.0  380.13  4969.4  381.62  4983.5  378.92  4991.1  374.97  4993.9  374.47
  4997.1  374.97  5020.5  376.61  5026.4  380.18  5041.6  376.87  5047.5  381.56
  5069.0  381.64  5077.9  378.56  5083.9  381.53  5128.2  381.14  5403.3  381.53
  5505.4  381.04  5583.2  381.80  5671.0  386.39  5743.7  395.37  5764.0  400.43
  5770.7  400.71  5780.0  407.44  5794.2  411.18  5801.1  416.45  5829.8  417.18
#Mann=10,-1,0
  3866.3    0.05       0  4145.0    0.12       0  4198.5    0.05       0
  4274.1    0.12       0  4991.1    0.07       0  4997.1    0.12       0
  5128.2    0.16       0  5403.3    0.12       0  5505.4    0.16       0
  5764.0     0.1       0
Bank Sta=4991.1,4997.1
Exp/Cntr=0.3,0.1

Type RM Length L Ch R = 1,2207,534,534,534
BEGIN DESCRIPTION:
UNT 013 IN UKCR 3.0
END DESCRIPTION:
XS GIS Cut Line= 3
      3589099.60     10586810.17      3588899.61     10586110.19
      3588099.58     10585310.16
#Sta/Elev= 30
  4233.3  398.51  4514.1  387.49  4720.8  382.01  4726.0  382.37  4765.0  379.89
  4832.6  378.26  4871.6  379.02  4910.6  378.26  4930.1  379.54  4975.4  379.73
  4989.6  378.12  5000.7  373.79  5003.5  373.29  5006.7  373.79  5017.9  380.09
  5067.2  379.69  5173.4  378.41  5195.0  378.83  5314.8  377.81  5523.7  377.98
  5531.0  378.04  5664.2  377.65  5824.0  378.85  5880.5  381.15  5934.8  384.96
  5993.7  389.30  6007.8  390.93  6022.0  391.39  6064.4  396.24  6092.7  398.07
#Mann=9,-1,0
  4233.3    0.05       0  5000.7    0.03       0  5006.7    0.05       0
  5067.2    0.12       0  5195.0    0.16       0  5523.7    0.05       0
  5531.0    0.16       0  5664.2    0.12       0  5934.8    0.05       0
Bank Sta=5000.7,5006.7
Exp/Cntr=0.3,0.1

Type RM Length L Ch R = 1,1673,499,499,499
BEGIN DESCRIPTION:
UNT 013 IN UKCR 2.0
END DESCRIPTION:
XS GIS Cut Line= 3
      3589149.60     10586810.21      3589299.61     10586010.19
      3587999.60     10585160.18
#Sta/Elev= 30
  4188.3  398.71  4412.2  392.26  4625.8  382.48  4676.7  381.56  4686.9  380.25
  4768.3  377.16  4890.3  376.81  4981.9  378.93  4992.1  376.89  4996.7  373.33
  4999.5  372.83  5002.7  373.33  5009.8  373.47  5015.8  379.04  5024.9  375.68
  5030.9  379.49  5038.1  379.62  5160.6  377.47  5248.1  378.05  5312.9  376.92
  5410.6  376.99  5605.7  376.89  5896.3  376.70  6066.6  378.26  6087.0  378.70
  6258.4  387.17  6330.8  392.77  6390.4  399.27  6493.9  408.71  6555.5  412.21
#Mann=10,-1,0
  4188.3    0.05       0  4996.7    0.03       0  5002.7    0.05       0
  5410.6     0.1       0  5605.7    0.05       0  5896.3    0.16       0
  6066.6    0.12       0  6087.0    0.05       0  6390.4    0.16       0
  6493.9    0.05       0
Bank Sta=4996.7,5002.7
Exp/Cntr=0.3,0.1

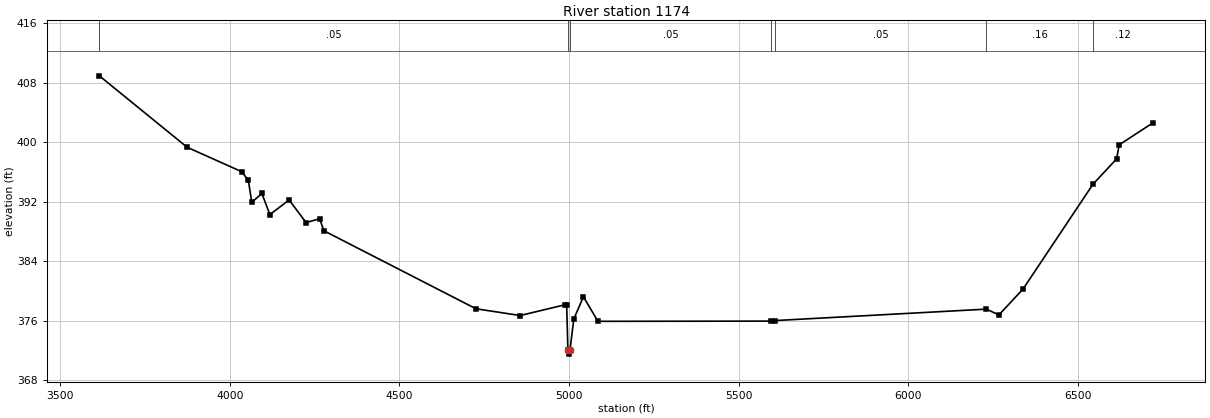
Type RM Length L Ch R = 1,1174,0,0,0
BEGIN DESCRIPTION:
UNT 013 IN UKCR 1.0
END DESCRIPTION:
XS GIS Cut Line= 3
      3589562.92     10587328.78      3589649.61     10585960.19
      3588349.60     10584810.18
#Sta/Elev= 30
  3614.8  408.96  3873.9  399.35  4034.2  396.08  4054.3  394.93  4064.3  391.95
  4094.3  393.14  4117.8  390.30  4174.5  392.27  4224.6  389.23  4264.7  389.74
  4277.0  388.13  4725.6  377.64  4855.9  376.73  4989.5  378.19  4993.2  378.08
  4996.9  372.04  4999.7  371.54  5002.9  372.04  5014.1  376.24  5042.6  379.26
  5085.3  375.95  5596.7  375.98  5607.1  376.05  6231.3  377.59  6268.0  376.81
  6339.1  380.28  6545.7  394.40  6615.1  397.78  6622.7  399.68  6721.8  402.62
#Mann=7,-1,0
  3614.8    0.05       0  4996.9    0.03       0  5002.9    0.05       0
  5596.7     0.1       0  5607.1    0.05       0  6231.3    0.16       0
  6545.7    0.12       0
Bank Sta=4996.9,5002.9
Exp/Cntr=0.3,0.1

Chan Stop Cuts=-1