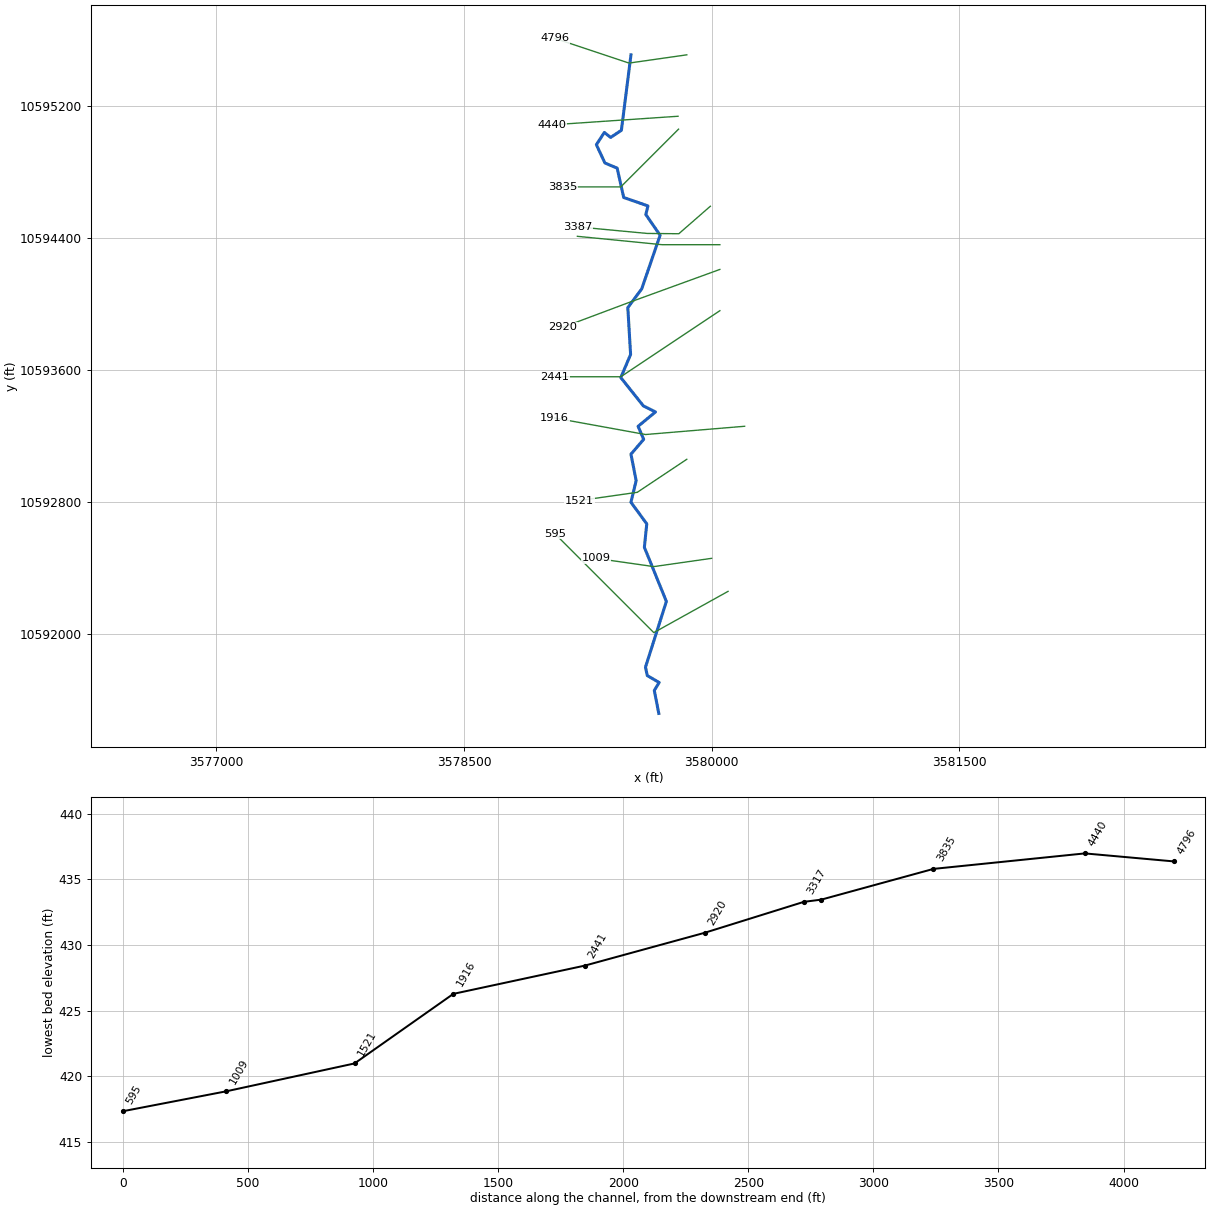
--- UNT 016 IN UKCR.prj (project) ---

Proj Title=UNT 016 IN UKCR Base Level Engineering
Current Plan=p01
Default Exp/Contr=0.3,0.1
English Units
Geom File=g01
Flow File=f01
Plan File=p01
Y Axis Title=Elevation
X Axis Title(PF)=Main Channel Distance
X Axis Title(XS)=Station
BEGIN DESCRIPTION:
UNT 016 IN UKCR
END DESCRIPTION:
DSS Export Rating Curves= 0
DSS Export Rating Curve Sorted= 0
DSS Export Volume Flow Curves= 0
DXF OffsetX= 0
DXF OffsetY= 0
DXF ScaleX= 1
DXF ScaleY= 10

--- UNT 016 IN UKCR.p01 (plan) ---

Plan Title=Multiple Run
Short Identifier=Multiple
Geom File=g01
Flow File=f01
Subcritical Flow
K Sum by GR= 0
Std Step Tol= 0.01
Critical Tol= 0.01
Num of Std Step Trials= 20
Max Error Tol= 0.3
Flow Tol Ratio= 0.001
Split Flow NTrial= 30
Split Flow Tol= 0.02
Split Flow Ratio= 0.02
Log Output Level= 0
Friction Slope Method= 1
Unsteady Friction Slope Method= 2
Unsteady Bridges Friction Slope Method= 1
Parabolic Critical Depth
Global Vel Dist=  1 , 1 , 1
Global Log Level= 0
CheckData=True
Encroach Param= -1, 0, 0, 0
BEGIN DESCRIPTION:
Multiple Run
END DESCRIPTION:

--- UNT 016 IN UKCR.f01 (steady flow) ---

Flow Title=Multiple
Number of Profiles=7
Profile Names=10-year,25-year,50-year,1pct_min,100-year,1pct_plu,500-year
River Rch & RM= UNT 016 IN UKCR,Reach-1,4796
     832    1124    1360    1203    1627    2200    2317
Boundary for River Rch & Prof#=UNT 016 IN UKCR,Reach-1,1
Up Type=0
Dn Type=3
Dn Slope=0.005
Boundary for River Rch & Prof#=UNT 016 IN UKCR,Reach-1,2
Up Type=0
Dn Type=3
Dn Slope=0.005
Boundary for River Rch & Prof#=UNT 016 IN UKCR,Reach-1,3
Up Type=0
Dn Type=3
Dn Slope=0.005
Boundary for River Rch & Prof#=UNT 016 IN UKCR,Reach-1,4
Up Type=0
Dn Type=3
Dn Slope=0.005
Boundary for River Rch & Prof#=UNT 016 IN UKCR,Reach-1,5
Up Type=0
Dn Type=3
Dn Slope=0.005
Boundary for River Rch & Prof#=UNT 016 IN UKCR,Reach-1,6
Up Type=0
Dn Type=3
Dn Slope=0.005
Boundary for River Rch & Prof#=UNT 016 IN UKCR,Reach-1,7
Up Type=0
Dn Type=3
Dn Slope=0.005

--- UNT 016 IN UKCR.g01 (geometry) ---

Geom Title=Existing Conditions
Program Version=4.10

River Reach=UNT 016 IN UKCR ,Reach-1
Reach XY= 30
      3579511.25       10595510.      3579453.25       10595053.
        3579388.       10595010.        3579350.       10595040.
      3579301.75       10594966.       3579353.5       10594855.
       3579427.5       10594824.      3579467.25       10594646.
      3579614.25       10594595.      3579601.25       10594543.
      3579687.75       10594417.      3579576.25       10594092.
      3579492.25       10593979.        3579509.       10593695.
      3579449.75       10593555.        3579586.       10593384.
      3579659.75       10593347.       3579554.5       10593260.
      3579588.25       10593181.      3579511.25       10593091.
      3579542.75       10592931.        3579511.       10592800.
        3579607.       10592669.       3579592.5       10592527.
      3579725.75       10592199.      3579599.25       10591801.
        3579610.       10591750.        3579682.       10591708.
       3579652.5       10591660.      3579679.75       10591521.

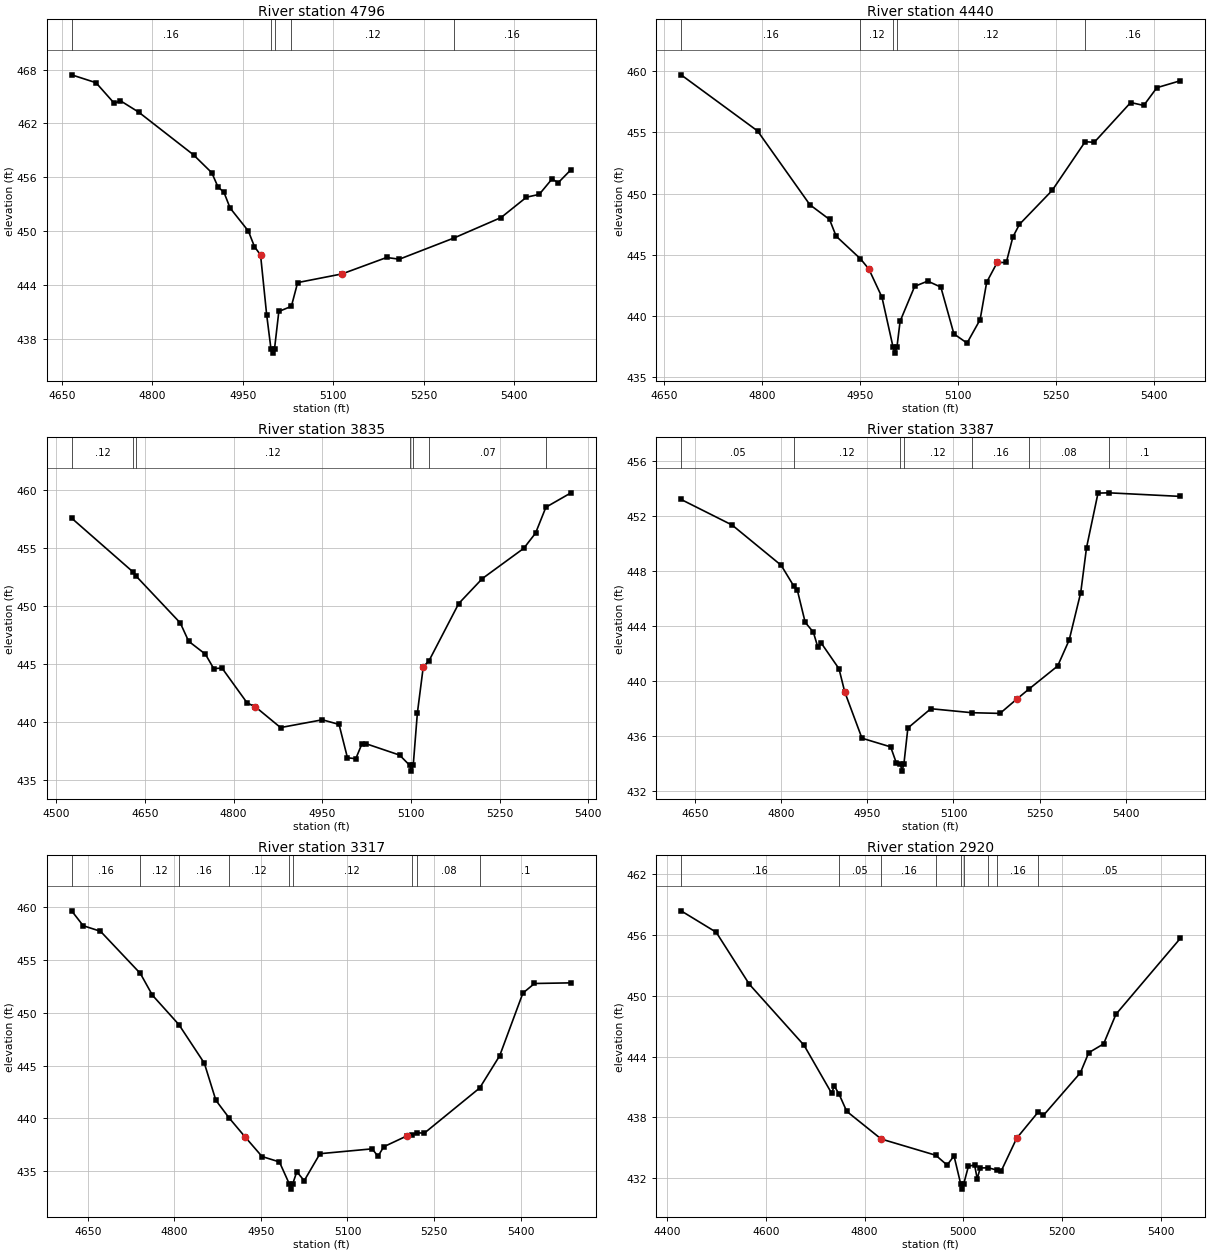
Type RM Length L Ch R = 1 ,4796    ,356,356,356
BEGIN DESCRIPTION:
UNT 016 IN UKCR 10.0
END DESCRIPTION:
XS GIS Cut Line= 3
      3579849.63     10595510.19      3579499.61     10595460.19
      3579049.63     10595610.18
#Sta/Elev= 30
  4666.4  467.42  4706.8  466.54  4737.1  464.24  4747.2  464.53  4777.5  463.26
  4868.5  458.49  4898.8  456.49  4908.9  454.93    4919   454.3  4929.1  452.56
  4959.4  449.99  4969.5  448.25  4979.6  447.32  4989.7  440.67  4996.8  436.87
  4999.5  436.37  5002.8  436.87  5009.9  441.02  5030.7  441.59  5041.1  444.24
  5114.8  445.21  5188.6  447.04  5209.7  446.85  5299.7   449.2  5378.4   451.5
  5420.5  453.77  5441.6  454.08  5462.7  455.79  5473.2  455.39  5494.3  456.84
#Mann= 5 ,-1 , 0
  4666.4     .16       0  4996.8     .07       0  5002.8     .16       0
  5030.7     .12       0  5299.7     .16       0
Bank Sta=4979.6,5114.8
XS Rating Curve= 0 ,0
Exp/Cntr=0.3,0.1

Type RM Length L Ch R = 1 ,4440    ,605,605,605
BEGIN DESCRIPTION:
UNT 016 IN UKCR 9.0
END DESCRIPTION:
XS GIS Cut Line= 2
      3579796.48     10595138.19      3579033.55     10595086.17
#Sta/Elev= 30
  4675.5   459.7  4792.6  455.12  4872.8  449.09  4902.9  447.89  4912.9  446.53
  4950.2  444.68    4963  443.85  4983.1  441.55  5000.1  437.48  5002.9  436.98
  5006.1  437.48  5010.9  439.58  5033.2  442.43  5053.2  442.86  5073.3  442.37
  5093.3  438.55  5113.4   437.8  5133.4  439.71  5143.5  442.77  5159.6  444.38
  5173.5  444.38  5183.6  446.46  5193.6  447.49  5243.7  450.26  5294.3  454.24
  5308.2  454.19    5364  457.44    5384   457.2  5404.1  458.65  5440.2  459.22
#Mann= 5 ,-1 , 0
  4675.5     .16       0  4950.2     .12       0  5000.1     .07       0
  5006.1     .12       0  5294.3     .16       0
Bank Sta=4963,5159.6
XS Rating Curve= 0 ,0
Exp/Cntr=0.3,0.1

Type RM Length L Ch R = 1 ,3835    ,448,448,448
BEGIN DESCRIPTION:
UNT 016 IN UKCR 8.0
END DESCRIPTION:
XS GIS Cut Line= 3
       3579799.6     10595060.18      3579449.61     10594710.19
      3579099.57     10594710.19
#Sta/Elev= 30
    4526  457.58  4630.5  452.92  4635.1  452.59  4709.8  448.56    4724  446.98
  4752.3  445.87  4766.4  444.63  4780.5  444.67    4823  441.67  4837.1  441.33
  4879.5  439.55  4950.3  440.22  4978.5  439.82  4992.7  436.95  5006.8  436.87
  5017.4  438.17  5023.5  438.17    5081  437.18    5098   436.3  5100.7   435.8
    5104   436.3    5111  440.79    5121  444.78  5130.7   445.3    5181  450.23
    5221  452.38    5291  454.98    5311  456.29  5328.5  458.52    5371  459.76
#Mann= 7 ,-1 , 0
    4526     .12       0  4630.5     .16       0  4635.1     .12       0
    5098     .07       0    5104     .12       0  5130.7     .07       0
  5328.5     .16       0
Bank Sta=4837.1,5121
XS Rating Curve= 0 ,0
Exp/Cntr=0.3,0.1

Type RM Length L Ch R = 1 ,3387    ,70,70,70
BEGIN DESCRIPTION:
Mapping XS 867c4aec
END DESCRIPTION:
XS GIS Cut Line= 4
       3579992.2     10594593.19      3579801.24     10594426.53
      3579610.27     10594428.27      3579186.68      10594468.2
#Sta/Elev= 30
  4625.5  453.18  4714.5  451.32  4799.9   448.4    4822  446.88    4828   446.6
  4841.7  444.26  4855.9  443.55  4863.5  442.49  4870.1  442.73  4900.6  440.89
  4910.6  439.21  4940.6  435.85  4990.6  435.22  5000.6  434.04  5007.6  433.96
  5010.3  433.46  5013.6  433.96  5020.6  436.59  5060.6  437.99  5131.9   437.7
  5181.1  437.65  5211.2  438.72  5231.6  439.42  5281.5  441.09  5301.6  442.98
  5321.7  446.42  5331.8  449.68  5351.8  453.64  5371.1  453.66  5495.4   453.4
#Mann= 7 ,-1 , 0
  4625.5     .05       0    4822     .12       0  5007.6     .07       0
  5013.6     .12       0  5131.9     .16       0  5231.6     .08       0
  5371.1      .1       0
Bank Sta=4910.6,5211.2
XS Rating Curve= 0 ,0
Exp/Cntr=0.3,0.1

Type RM Length L Ch R = 1 ,3317    ,397,397,397
BEGIN DESCRIPTION:
UNT 016 IN UKCR 7.0
END DESCRIPTION:
XS GIS Cut Line= 3
      3580049.65     10594360.19      3579699.61     10594360.19
      3579186.65     10594410.91
#Sta/Elev= 30
  4621.9  459.68  4641.9  458.27  4671.9  457.74    4741  453.74  4761.9  451.68
  4807.8  448.89  4851.9  445.23  4871.9  441.71    4895  440.03  4921.9  438.28
  4951.9  436.38    4982  435.87  4999.1  433.79  5001.8  433.29  5005.1  433.79
  5012.1  434.94    5025  434.09  5052.3  436.65  5142.8  437.11  5152.8   436.4
  5162.9  437.31  5203.1  438.34  5211.4  438.43  5221.2  438.63  5233.2   438.6
  5329.1  442.88  5363.8  445.94    5404  451.88  5424.1  452.79  5487.4  452.85
#Mann= 9 ,-1 , 0
  4621.9     .16       0    4741     .12       0  4807.8     .16       0
    4895     .12       0  4999.1     .07       0  5005.1     .12       0
  5211.4     .16       0  5221.2     .08       0  5329.1      .1       0
Bank Sta=4921.9,5203.1
XS Rating Curve= 0 ,0
Exp/Cntr=0.3,0.1

Type RM Length L Ch R = 1 ,2920    ,479,479,479
BEGIN DESCRIPTION:
UNT 016 IN UKCR 6.0
END DESCRIPTION:
XS GIS Cut Line= 3
      3580049.66     10594210.21      3579499.61     10594010.19
      3579099.59     10593860.18
#Sta/Elev= 30
  4427.8  458.37    4499  456.26  4566.2  451.13  4677.2  445.11  4733.1  440.38
  4738.4  441.11  4747.9  440.32  4763.7   438.6  4833.6  435.87  4944.2  434.27
  4967.2   433.3  4981.2  434.21  4994.8  431.43  4997.5  430.93  5000.8  431.43
  5010.4  433.18  5022.9  433.32  5028.2  431.95  5034.4  433.02    5051  433.03
    5068  432.81  5077.2  432.75  5108.3  435.95  5152.2  438.55  5162.6  438.21
  5237.4   442.4  5254.3  444.38  5284.5  445.25  5309.5  448.17  5440.3  455.67
#Mann= 9 ,-1 , 0
  4427.8     .16       0  4747.9     .05       0  4833.6     .16       0
  4944.2     .12       0  4994.8     .07       0  5000.8     .12       0
    5051     .05       0    5068     .16       0  5152.2     .05       0
Bank Sta=4833.6,5108.3
XS Rating Curve= 0 ,0
Exp/Cntr=0.3,0.1

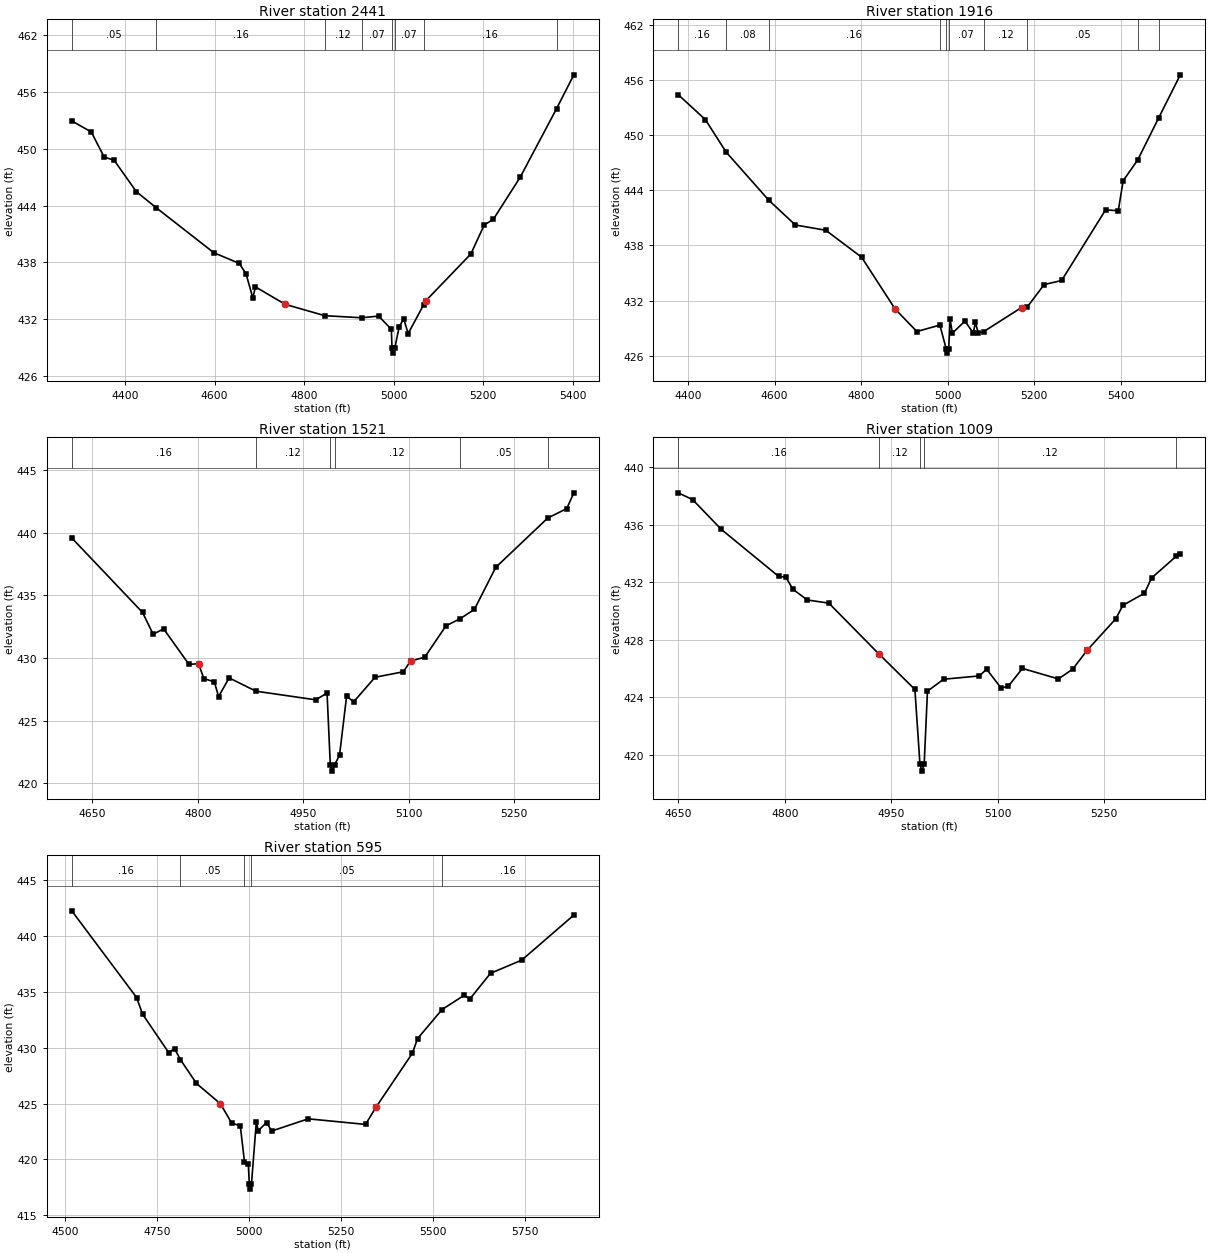
Type RM Length L Ch R = 1 ,2441    ,525,525,525
BEGIN DESCRIPTION:
UNT 016 IN UKCR 5.0
END DESCRIPTION:
XS GIS Cut Line= 3
      3580049.63      10593960.2      3579449.61     10593560.19
      3579049.65     10593560.19
#Sta/Elev= 30
  4281.2  452.93  4324.8  451.76  4353.3  449.13  4375.9  448.77  4425.5  445.46
  4470.3  443.75  4598.2  439.03  4655.3  437.89  4670.3   436.8  4685.4  434.27
  4691.4  435.42  4757.5  433.58  4846.2  432.38  4928.7  432.16  4966.3  432.34
  4994.8  430.95  4996.3  428.93  4999.1  428.43  5002.3  428.93  5012.3   431.2
  5022.3  432.07  5032.3  430.49  5066.9  433.53  5072.3  433.98  5172.3  438.89
  5202.3  441.96  5222.3  442.53  5282.3  446.97  5363.6  454.21  5402.3  457.79
#Mann= 8 ,-1 , 0
  4281.2     .05       0  4470.3     .16       0  4846.2     .12       0
  4928.7     .07       0  4996.3     .07       0  5002.3     .07       0
  5066.9     .16       0  5363.6     .05       0
Bank Sta=4757.5,5072.3
XS Rating Curve= 0 ,0
Exp/Cntr=0.3,0.1

Type RM Length L Ch R = 1 ,1916    ,395,395,395
BEGIN DESCRIPTION:
UNT 016 IN UKCR 4.0
END DESCRIPTION:
XS GIS Cut Line= 3
      3580199.65     10593260.19      3579599.61     10593210.19
      3579049.64     10593310.18
#Sta/Elev= 30
  4377.2  454.38    4440  451.67  4487.6  448.16  4586.5  442.91  4648.2  440.21
  4718.4  439.64  4801.2  436.71    4879  431.06  4929.1  428.63  4982.3  429.33
  4996.6  426.78  4999.4  426.28  5002.6  426.78    5006  429.94  5011.1  428.45
  5040.3  429.76  5059.4  428.47  5064.4  429.62  5070.8  428.51  5083.6  428.62
  5171.2  431.24  5184.8  431.32  5223.3  433.73  5263.9  434.18  5365.5  441.86
  5394.8  441.76  5406.2  445.03  5439.5  447.26  5488.6  451.89  5538.3  456.54
#Mann= 10 ,-1 , 0
  4377.2     .16       0  4487.6     .08       0  4586.5     .16       0
  4982.3     .07       0  4996.6     .07       0  5002.6     .07       0
  5083.6     .12       0  5184.8     .05       0  5439.5     .16       0
  5488.6     .05       0
Bank Sta=4879,5171.2
XS Rating Curve= 0 ,0
Exp/Cntr=0.3,0.1

Type RM Length L Ch R = 1 ,1521    ,512,512,512
BEGIN DESCRIPTION:
UNT 016 IN UKCR 3.0
END DESCRIPTION:
XS GIS Cut Line= 3
      3579849.61     10593060.19      3579549.61     10592860.19
      3579199.62     10592810.19
#Sta/Elev= 30
  4620.6  439.59  4721.3  433.64  4736.3  431.91  4751.3  432.33  4787.4  429.49
  4800.9  429.56  4808.4  428.37  4823.4   428.1  4829.4  426.93  4844.4  428.42
  4882.5  427.36  4967.6  426.67  4983.7  427.21  4988.3  421.48    4991  420.98
  4994.3  421.48  5001.4  422.24  5011.5  426.96  5021.6  426.51  5051.9  428.47
  5092.3  428.91  5102.4  429.77  5122.6  430.07  5152.9  432.58  5172.9  433.14
  5193.3  433.89  5223.6  437.24  5297.6  441.18  5324.6  441.93  5334.7  443.19
#Mann= 6 ,-1 , 0
  4620.6     .16       0  4882.5     .12       0  4988.3     .07       0
  4994.3     .12       0  5172.9     .05       0  5297.6     .16       0
Bank Sta=4800.9,5102.4
XS Rating Curve= 0 ,0
Exp/Cntr=0.3,0.1

Type RM Length L Ch R = 1 ,1009    ,414,414,414
BEGIN DESCRIPTION:
UNT 016 IN UKCR 2.0
END DESCRIPTION:
XS GIS Cut Line= 3
      3579999.59     10592460.19      3579649.61     10592410.19
      3579299.59     10592460.19
#Sta/Elev= 30
    4650  438.21  4670.2  437.74  4710.6  435.67  4791.4   432.4  4801.5  432.35
  4811.6   431.5  4831.8  430.76  4862.1  430.54  4932.7     427  4932.8     427
  4983.3  424.54  4990.4  419.36  4993.2  418.86  4996.4  419.36    5001  424.42
  5023.7  425.25  5074.2  425.48  5084.3  425.95  5104.5  424.65  5114.6  424.75
  5134.8     426  5185.4  425.27  5205.6  425.95  5225.8  427.26  5266.2  429.45
  5276.3  430.39  5306.6  431.23  5316.7  432.29  5351.1  433.79  5357.1  433.99
#Mann= 5 ,-1 , 0
    4650     .16       0  4932.7     .12       0  4990.4     .07       0
  4996.4     .12       0  5351.1     .16       0
Bank Sta=4932.8,5225.8
XS Rating Curve= 0 ,0
Exp/Cntr=0.3,0.1

Type RM Length L Ch R = 1 ,595     ,0,0,0
BEGIN DESCRIPTION:
UNT 016 IN UKCR 1.0
END DESCRIPTION:
XS GIS Cut Line= 3
      3580099.57     10592260.17      3579649.61     10592010.19
      3579049.59     10592610.21
#Sta/Elev= 30
  4518.7  442.24  4694.8  434.48  4710.8     433  4781.8  429.56  4797.8   429.9
  4813.8  428.92  4857.3   426.8  4922.5  424.97  4953.4  423.22  4976.2  423.03
  4987.7  419.78    4998  419.62  5000.7  417.84  5003.4  417.34  5006.7  417.84
  5019.7  423.31  5025.4  422.58  5047.6   423.3  5061.7  422.54  5160.7  423.63
  5316.3  423.13  5344.6  424.66  5443.6   429.5  5457.7  430.81  5524.2  433.41
    5585   434.7  5599.1  434.33  5655.7  436.65  5740.5  437.83    5882  441.86
#Mann= 5 ,-1 , 0
  4518.7     .16       0  4813.8     .05       0  4987.7     .03       0
  5006.7     .05       0  5524.2     .16       0
Bank Sta=4922.5,5344.6
XS Rating Curve= 0 ,0
Exp/Cntr=0.3,0.1

Chan Stop Cuts=-1
Use User Specified Reach Order=0
Composite Channel Slope=5