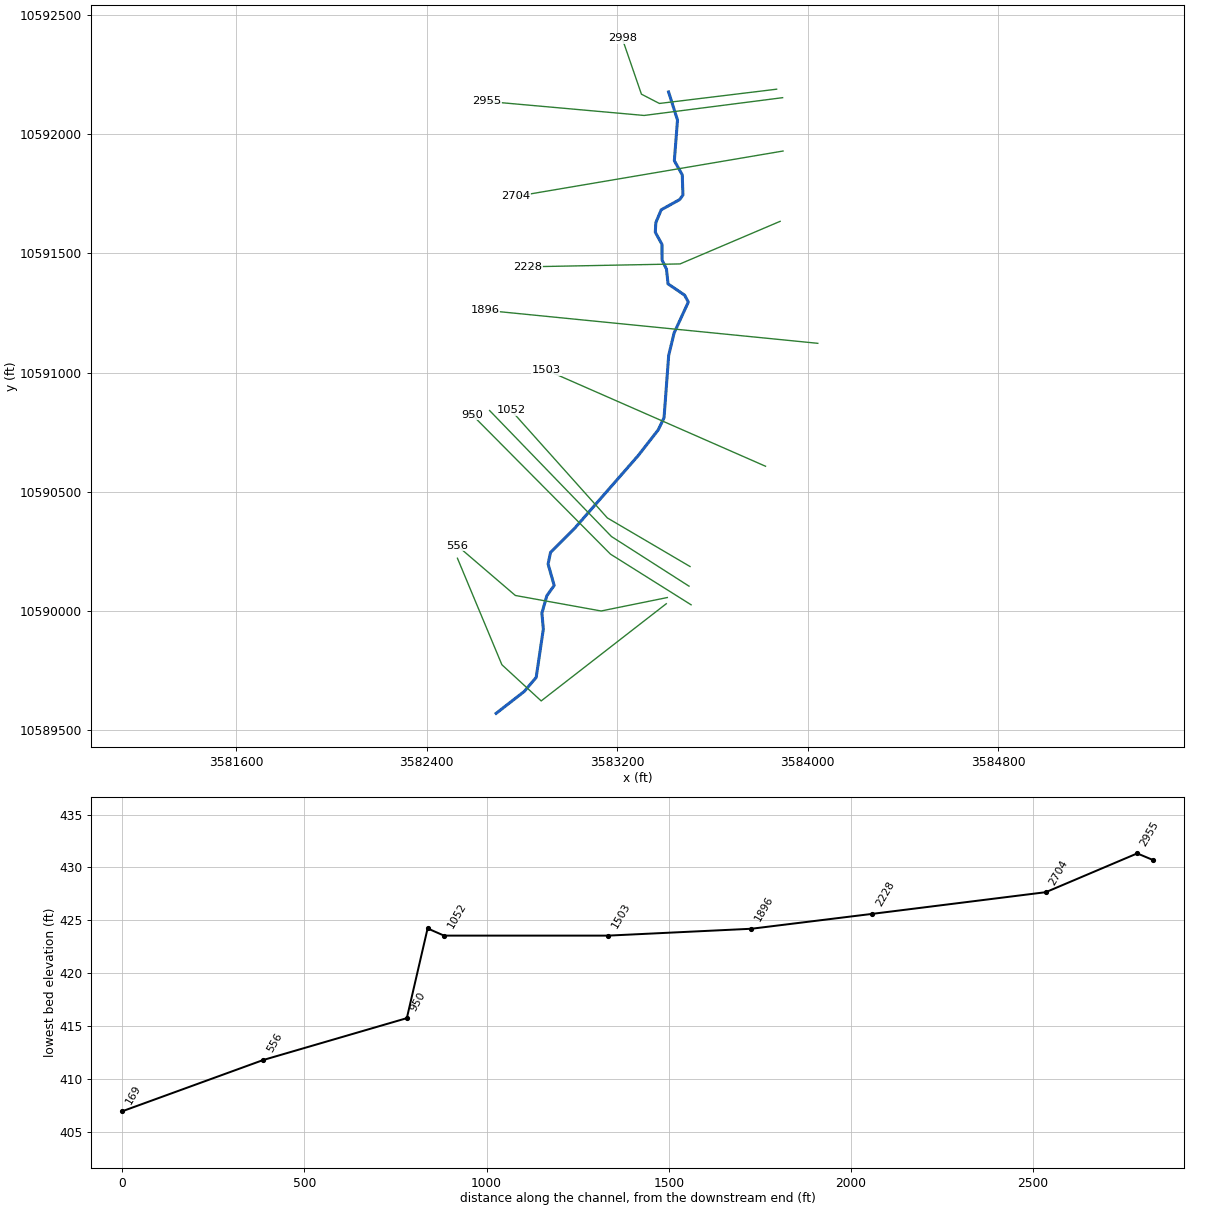
--- UNT 018 IN UKCR.prj (project) ---

Proj Title=UNT 018 IN UKCR Base Level Engineering
Current Plan=p01
Default Exp/Contr=0.3,0.1
English Units
Geom File=g01
Flow File=f01
Plan File=p01
Y Axis Title=Elevation
X Axis Title(PF)=Main Channel Distance
X Axis Title(XS)=Station
BEGIN DESCRIPTION:
UNT 018 IN UKCR
END DESCRIPTION:
DSS Export Rating Curves= 0
DSS Export Rating Curve Sorted= 0
DSS Export Volume Flow Curves= 0
DXF OffsetX= 0
DXF OffsetY= 0
DXF ScaleX= 1
DXF ScaleY= 10

--- UNT 018 IN UKCR.p01 (plan) ---

Plan Title=Multiple Run
Short Identifier=Multiple
Geom File=g01
Flow File=f01
Subcritical Flow
K Sum by GR= 0
Std Step Tol= 0.01
Critical Tol= 0.01
Num of Std Step Trials= 20
Max Error Tol= 0.3
Flow Tol Ratio= 0.001
Split Flow NTrial= 30
Split Flow Tol= 0.02
Split Flow Ratio= 0.02
Log Output Level= 0
Friction Slope Method= 1
Unsteady Friction Slope Method= 2
Unsteady Bridges Friction Slope Method= 1
Parabolic Critical Depth
Global Vel Dist=  1 , 1 , 1
Global Log Level= 0
CheckData=True
Encroach Param= -1, 0, 0, 0
BEGIN DESCRIPTION:
Multiple Run
END DESCRIPTION:

--- UNT 018 IN UKCR.f01 (steady flow) ---

Flow Title=Multiple
Number of Profiles=7
Profile Names=10-year,25-year,50-year,1pct_min,100-year,1pct_plu,500-year
River Rch & RM= UNT 018 IN UKCR,Reach-1,2998
     149     172     187     149     201     272     231
Boundary for River Rch & Prof#=UNT 018 IN UKCR,Reach-1,1
Up Type=0
Dn Type=3
Dn Slope=0.005
Boundary for River Rch & Prof#=UNT 018 IN UKCR,Reach-1,2
Up Type=0
Dn Type=3
Dn Slope=0.005
Boundary for River Rch & Prof#=UNT 018 IN UKCR,Reach-1,3
Up Type=0
Dn Type=3
Dn Slope=0.005
Boundary for River Rch & Prof#=UNT 018 IN UKCR,Reach-1,4
Up Type=0
Dn Type=3
Dn Slope=0.005
Boundary for River Rch & Prof#=UNT 018 IN UKCR,Reach-1,5
Up Type=0
Dn Type=3
Dn Slope=0.005
Boundary for River Rch & Prof#=UNT 018 IN UKCR,Reach-1,6
Up Type=0
Dn Type=3
Dn Slope=0.005
Boundary for River Rch & Prof#=UNT 018 IN UKCR,Reach-1,7
Up Type=0
Dn Type=3
Dn Slope=0.005

--- UNT 018 IN UKCR.g01 (geometry) ---

Geom Title=Existing Conditions

River Reach=UNT 018 IN UKCR,Reach-1
Reach XY= 30
      3583415.50     10592178.00      3583453.00     10592060.00
      3583439.75     10591889.00      3583473.00     10591830.00
      3583475.75     10591745.00      3583462.00     10591726.00
      3583384.50     10591683.00      3583362.00     10591629.00
      3583359.75     10591589.00      3583387.75     10591538.00
      3583388.25     10591472.00      3583406.75     10591434.00
      3583413.25     10591372.00      3583482.75     10591325.00
      3583498.50     10591296.00      3583438.75     10591166.00
      3583416.00     10591072.00      3583396.50     10590810.00
      3583372.00     10590759.00      3583287.75     10590651.00
      3583021.25     10590346.00      3582920.00     10590245.00
      3582909.75     10590196.00      3582935.25     10590106.00
      3582904.50     10590063.00      3582883.75     10589990.00
      3582889.75     10589923.00      3582859.75     10589720.00
      3582809.50     10589661.00      3582691.50     10589569.00

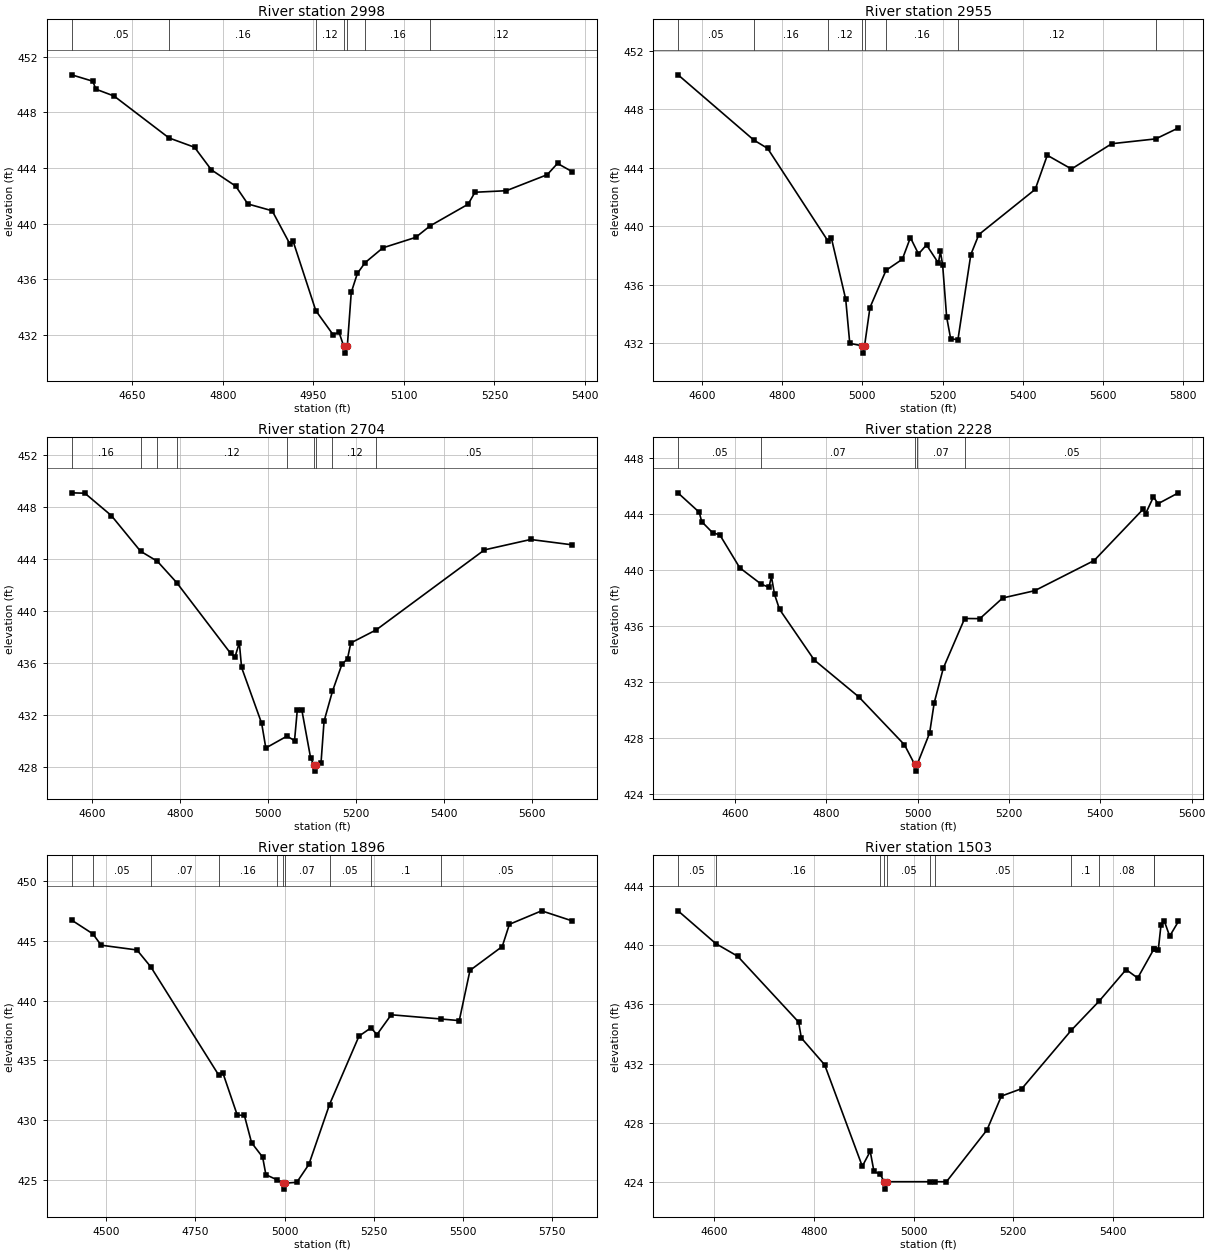
Type RM Length L Ch R = 1,2998,43,43,43
BEGIN DESCRIPTION:
UNT 018 IN UKCR 4.0
END DESCRIPTION:
XS GIS Cut Line= 4
      3583869.20     10592189.43      3583377.02     10592129.54
      3583301.50     10592168.60      3583220.78     10592402.96
#Sta/Elev= 30
  4549.8  450.69  4584.8  450.23  4589.8  449.66  4619.9  449.17  4710.9  446.16
  4753.2  445.49  4781.1  443.87  4821.4  442.70  4841.5  441.42  4881.8  440.93
  4911.5  438.52  4916.6  438.73  4954.1  433.76  4982.6  432.04  4992.6  432.20
  5000.3  431.21  5003.0  430.71  5006.3  431.21  5012.8  435.07  5022.9  436.43
  5035.6  437.20  5065.2  438.27  5119.5  439.02  5143.2  439.84  5206.3  441.40
  5217.7  442.26  5269.6  442.37  5337.3  443.52  5354.4  444.33  5378.5  443.74
#Mann=7,-1,0
  4549.8    0.05       0  4710.9    0.16       0  4954.1    0.12       0
  5000.3    0.07       0  5006.3    0.12       0  5035.6    0.16       0
  5143.2    0.12       0
Bank Sta=5000.3,5006.3
Exp/Cntr=0.3,0.1

Type RM Length L Ch R = 1,2955,251,251,251
BEGIN DESCRIPTION:
Mapping XS afd69199
END DESCRIPTION:
XS GIS Cut Line= 3
      3583894.34     10592153.84      3583312.79     10592079.19
      3582653.84     10592138.15
#Sta/Elev= 30
  4540.4  450.36  4729.3  445.90  4763.7  445.33  4913.4  439.03  4922.9  439.18
  4958.5  435.01  4968.6  432.00  4999.5  431.83  5002.2  431.33  5005.5  431.83
  5019.0  434.45  5059.0  436.99  5099.7  437.75  5119.8  439.23  5140.0  438.11
  5160.0  438.73  5189.6  437.49  5194.6  438.28  5200.2  437.36  5210.2  433.80
  5220.3  432.30  5238.4  432.26  5270.5  438.07  5290.6  439.44  5431.1  442.53
  5461.2  444.86  5521.5  443.92  5621.9  445.65  5731.7  445.98  5788.3  446.73
#Mann=8,-1,0
  4540.4    0.05       0  4729.3    0.16       0  4913.4    0.12       0
  4999.5    0.07       0  5005.5    0.12       0  5059.0    0.16       0
  5238.4    0.12       0  5731.7    0.16       0
Bank Sta=4999.5,5005.5
Exp/Cntr=0.3,0.1

Type RM Length L Ch R = 1,2704,476,476,476
BEGIN DESCRIPTION:
Mapping XS 231e3ecc
END DESCRIPTION:
XS GIS Cut Line= 2
      3583896.11     10591929.88      3582772.88     10591739.21
#Sta/Elev= 30
  4552.8  449.07  4582.8  449.04  4643.1  447.32  4709.5  444.58  4748.0  443.80
  4791.7  442.17  4914.4  436.73  4924.5  436.43  4934.5  437.53  4939.6  435.64
  4985.4  431.33  4994.8  429.44  5042.9  430.35  5060.2  430.01  5066.5  432.37
  5076.7  432.38  5097.0  428.64  5104.1  428.16  5106.9  427.66  5110.1  428.16
  5120.5  428.30  5127.4  431.50  5146.6  433.81  5168.0  435.87  5180.8  436.31
  5188.3  437.52  5246.3  438.53  5492.6  444.68  5597.8  445.48  5692.1  445.07
#Mann=9,-1,0
  4552.8    0.16       0  4709.5    0.12       0  4748.0    0.07       0
  4791.7    0.12       0  5042.9    0.07       0  5104.1    0.07       0
  5110.1    0.07       0  5146.6    0.12       0  5246.3    0.05       0
Bank Sta=5104.1,5110.1
Exp/Cntr=0.3,0.1

Type RM Length L Ch R = 1,2228,332,332,332
BEGIN DESCRIPTION:
Mapping XS 109abb5c
END DESCRIPTION:
XS GIS Cut Line= 3
      3583883.92     10591634.73      3583463.83     10591455.93
      3582824.91     10591443.77
#Sta/Elev= 30
  4475.6  445.53  4521.9  444.15  4527.3  443.48  4551.0  442.69  4567.2  442.52
  4610.7  440.17  4657.2  439.01  4674.6  438.77  4680.0  439.55  4686.8  438.27
  4697.7  437.20  4773.7  433.57  4871.5  430.92  4971.2  427.50  4993.4  426.11
  4996.1  425.61  4999.4  426.11  5026.4  428.34  5036.4  430.50  5056.4  432.99
  5103.1  436.54  5136.4  436.53  5186.4  438.01  5256.4  438.53  5386.5  440.69
  5494.2  444.38  5499.2  444.04  5516.5  445.25  5526.5  444.76  5571.2  445.54
#Mann=5,-1,0
  4475.6    0.05       0  4657.2    0.07       0  4993.4    0.07       0
  4999.4    0.07       0  5103.1    0.05       0
Bank Sta=4993.4,4999.4
Exp/Cntr=0.3,0.1

Type RM Length L Ch R = 1,1896,393,393,393
BEGIN DESCRIPTION:
Mapping XS ce30ffbb
END DESCRIPTION:
XS GIS Cut Line= 2
      3584041.95     10591122.59      3582644.54     10591261.47
#Sta/Elev= 30
  4402.7  446.74  4462.1  445.59  4485.4  444.64  4585.9  444.24  4624.8  442.82
  4815.2  433.76  4827.1  433.93  4867.3  430.41  4887.4  430.37  4907.5  428.09
  4938.6  426.88  4947.7  425.41  4979.0  424.98  4995.0  424.70  4997.7  424.20
  5001.0  424.70  5034.4  424.77  5068.3  426.27  5126.3  431.29  5209.0  437.02
  5242.9  437.72  5259.2  437.14  5299.4  438.81  5437.8  438.46  5490.4  438.32
  5520.5  442.53  5611.0  444.53  5631.1  446.39  5721.5  447.52  5807.0  446.68
#Mann=10,-1,0
  4402.7    0.16       0  4462.1    0.05       0  4624.8    0.07       0
  4815.2    0.16       0  4979.0    0.07       0  4995.0    0.07       0
  5001.0    0.07       0  5126.3    0.05       0  5242.9     0.1       0
  5437.8    0.05       0
Bank Sta=4995,5001
Exp/Cntr=0.3,0.1

Type RM Length L Ch R = 1,1503,451,451,451
BEGIN DESCRIPTION:
Mapping XS 94412c14
END DESCRIPTION:
XS GIS Cut Line= 2
      3583822.52     10590606.52      3582903.47     10591009.69
#Sta/Elev= 30
  4527.6  442.31  4603.3  440.10  4647.1  439.25  4769.4  434.81  4774.8  433.74
  4821.6  431.93  4897.1  425.09  4913.0  426.10  4920.5  424.74  4933.0  424.56
  4940.9  424.05  4943.6  423.55  4946.9  424.05  5033.5  424.05  5042.9  424.05
  5065.9  424.05  5147.2  427.54  5176.0  429.82  5217.3  430.33  5316.0  434.25
  5372.6  436.24  5426.2  438.35  5449.4  437.78  5481.7  439.72  5482.4  439.72
  5490.7  439.67  5496.1  441.33  5502.7  441.63  5513.6  440.60  5531.2  441.60
#Mann=11,-1,0
  4527.6    0.05       0  4603.3    0.16       0  4933.0    0.05       0
  4940.9   0.033       0  4946.9    0.05       0  5033.5    0.16       0
  5042.9    0.05       0  5316.0     0.1       0  5372.6    0.08       0
  5481.7     0.1       0  5482.4    0.05       0
Bank Sta=4940.9,4946.9
Exp/Cntr=0.3,0.1

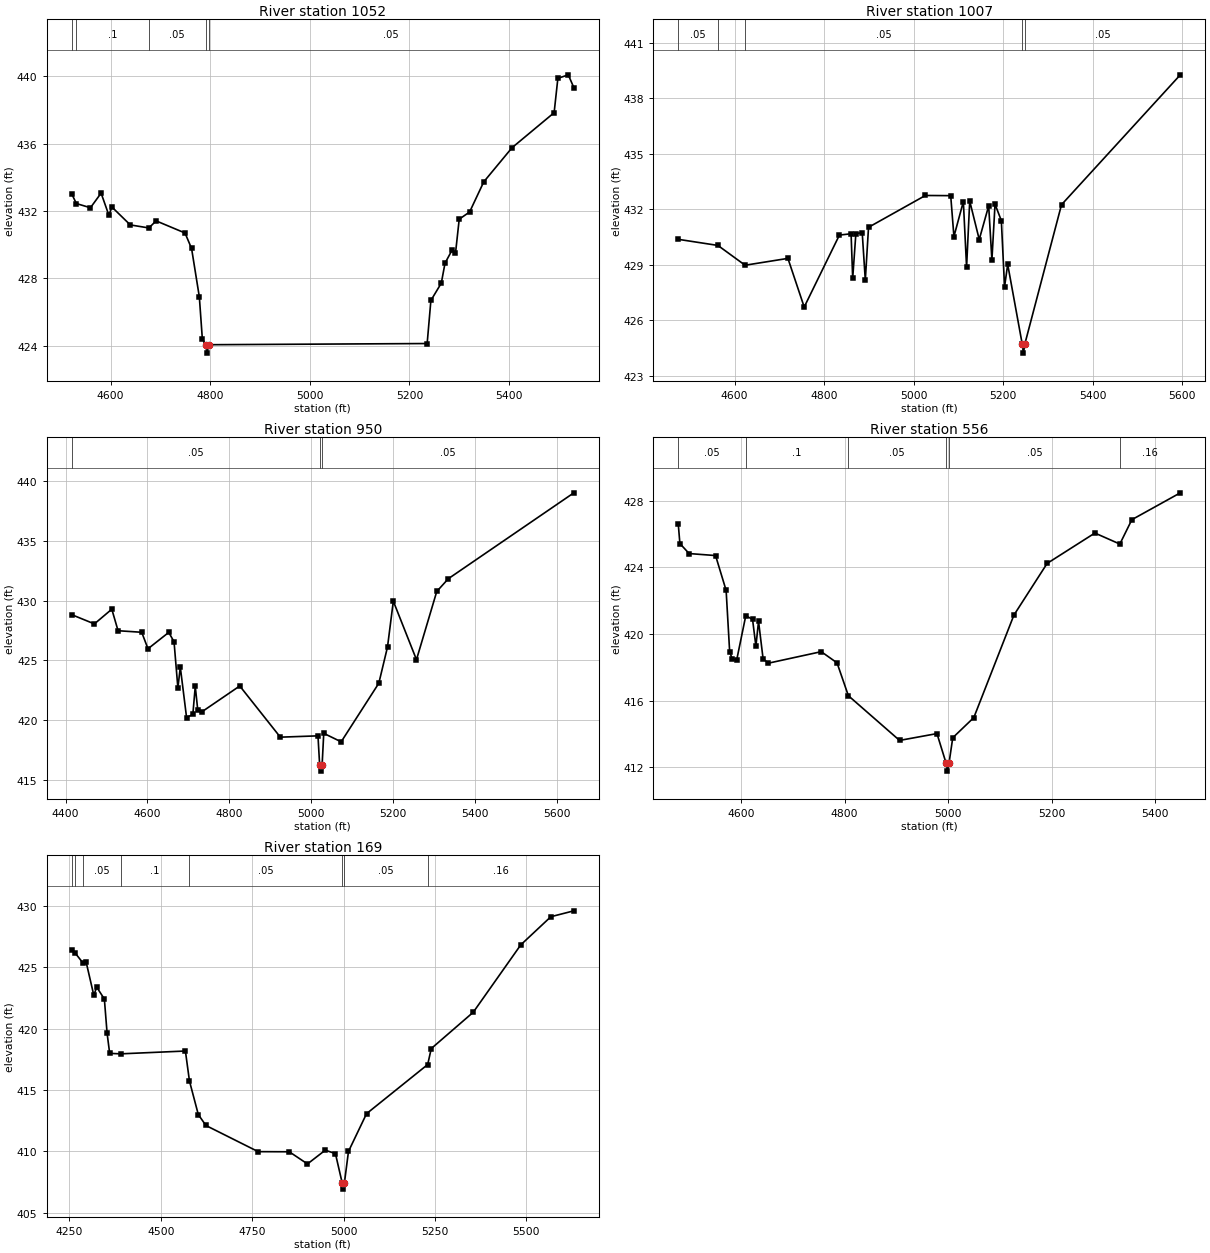
Type RM Length L Ch R = 1,1052,45,45,45
BEGIN DESCRIPTION:
Mapping XS 2b84fe16
END DESCRIPTION:
XS GIS Cut Line= 3
      3583505.70     10590185.50      3583158.46     10590389.51
      3582754.80     10590840.91
#Sta/Elev= 30
  4522.0  433.01  4531.2  432.44  4559.5  432.19  4580.9  433.06  4596.6  431.74
  4602.4  432.24  4639.5  431.17  4676.8  430.99  4691.4  431.41  4749.4  430.69
  4762.6  429.77  4778.2  426.89  4784.2  424.40  4790.9  424.05  4793.6  423.55
  4796.9  424.05  5235.7  424.12  5243.2  426.68  5264.1  427.71  5271.6  428.90
  5285.9  429.68  5292.6  429.48  5300.1  431.51  5321.0  431.94  5349.4  433.73
  5406.2  435.76  5490.7  437.84  5498.2  439.88  5519.1  440.09  5530.3  439.33
#Mann=5,-1,0
  4522.0    0.05       0  4531.2     0.1       0  4676.8    0.05       0
  4790.9   0.033       0  4796.9    0.05       0
Bank Sta=4790.9,4796.9
Exp/Cntr=0.3,0.1

Type RM Length L Ch R = 1,1007,57,57,57
BEGIN DESCRIPTION:
UNT 018 IN UKCR 3.0
END DESCRIPTION:
XS GIS Cut Line= 3
      3583501.30     10590103.07      3583175.82     10590311.38
      3582664.16     10590840.39
#Sta/Elev= 30
  4473.9  430.38  4562.6  430.05  4623.4  428.98  4719.1  429.35  4755.5  426.72
  4834.2  430.61  4860.3  430.68  4863.9  428.27  4871.0  430.69  4885.2  430.74
  4892.1  428.17  4899.3  431.03  5026.4  432.75  5083.0  432.74  5090.2  430.53
  5111.3  432.42  5118.5  428.87  5125.5  432.45  5146.8  430.37  5167.9  432.19
  5175.1  429.26  5182.1  432.28  5196.2  431.39  5203.4  427.81  5210.4  429.03
  5242.8  424.73  5245.6  424.23  5248.8  424.73  5330.7  432.25  5596.3  439.27
#Mann=5,-1,0
  4473.9    0.05       0  4562.6     0.1       0  4623.4    0.05       0
  5242.8    0.03       0  5248.8    0.05       0
Bank Sta=5242.8,5248.8
Exp/Cntr=0.3,0.1

Type RM Length L Ch R = 1,950,394,394,394
BEGIN DESCRIPTION:
UNT 018 IN UKCR 2.0
END DESCRIPTION:
XS GIS Cut Line= 3
      3583510.00     10590024.94      3583171.48     10590237.60
      3582589.85     10590823.57
#Sta/Elev= 30
  4415.3  428.82  4470.5  428.05  4513.0  429.28  4528.3  427.48  4586.0  427.35
  4601.3  425.97  4652.0  427.34  4664.9  426.56  4674.3  422.69  4680.2  424.44
  4695.5  420.22  4710.8  420.48  4716.7  422.83  4722.8  420.84  4732.0  420.68
  4825.3  422.86  4924.3  418.58  5016.2  418.69  5020.3  416.24  5023.0  415.74
  5026.3  416.24  5030.3  418.90  5072.8  418.19  5164.7  423.09  5185.9  426.12
  5200.1  429.95  5256.6  425.06  5306.1  430.76  5334.4  431.83  5640.7  439.01
#Mann=3,-1,0
  4415.3    0.05       0  5020.3    0.03       0  5026.3    0.05       0
Bank Sta=5020.3,5026.3
Exp/Cntr=0.3,0.1

Type RM Length L Ch R = 1,556,387,387,387
BEGIN DESCRIPTION:
Mapping XS 1c01760f
END DESCRIPTION:
XS GIS Cut Line= 4
      3583410.24     10590055.31      3583132.42     10589998.88
      3582772.18     10590063.99      3582529.11     10590272.33
#Sta/Elev= 30
  4478.6  426.61  4481.8  425.42  4499.6  424.82  4550.7  424.70  4571.1  422.61
  4577.9  418.94  4583.0  418.49  4591.5  418.44  4609.0  421.09  4622.1  420.88
  4628.6  419.27  4633.7  420.76  4642.5  418.51  4652.7  418.25  4754.8  418.94
  4785.3  418.27  4807.2  416.30  4906.1  413.62  4978.3  414.03  4995.7  412.28
  4998.4  411.78  5001.7  412.28  5008.8  413.78  5049.5  414.99  5126.9  421.13
  5191.1  424.23  5283.3  426.05  5331.5  425.39  5354.7  426.85  5448.3  428.46
#Mann=6,-1,0
  4478.6    0.05       0  4609.0     0.1       0  4807.2    0.05       0
  4995.7    0.03       0  5001.7    0.05       0  5331.5    0.16       0
Bank Sta=4995.7,5001.7
Exp/Cntr=0.3,0.1

Type RM Length L Ch R = 1,169,0,0,0
BEGIN DESCRIPTION:
UNT 018 IN UKCR 1.0
END DESCRIPTION:
XS GIS Cut Line= 4
      3583405.87     10590029.28      3582880.68     10589621.28
      3582715.75     10589773.19      3582529.13     10590220.22
#Sta/Elev= 30
  4256.3  426.39  4266.0  426.13  4286.3  425.36  4295.7  425.40  4316.5  422.72
  4324.7  423.36  4345.5  422.40  4352.9  419.63  4360.0  417.98  4389.9  417.94
  4567.2  418.17  4578.3  415.73  4602.5  413.00  4623.3  412.11  4766.3  409.98
  4851.4  409.97  4901.2  408.98  4949.9  410.10  4977.7  409.82  4996.2  407.43
  4999.0  406.93  5002.2  407.43  5013.4  410.00  5062.8  413.07  5230.1  417.07
  5239.9  418.37  5354.9  421.33  5484.8  426.81  5567.1  429.10  5630.0  429.58
#Mann=8,-1,0
  4256.3    0.05       0  4266.0     0.1       0  4286.3    0.05       0
  4389.9     0.1       0  4578.3    0.05       0  4996.2    0.03       0
  5002.2    0.05       0  5230.1    0.16       0
Bank Sta=4996.2,5002.2
Exp/Cntr=0.3,0.1

Chan Stop Cuts=-1