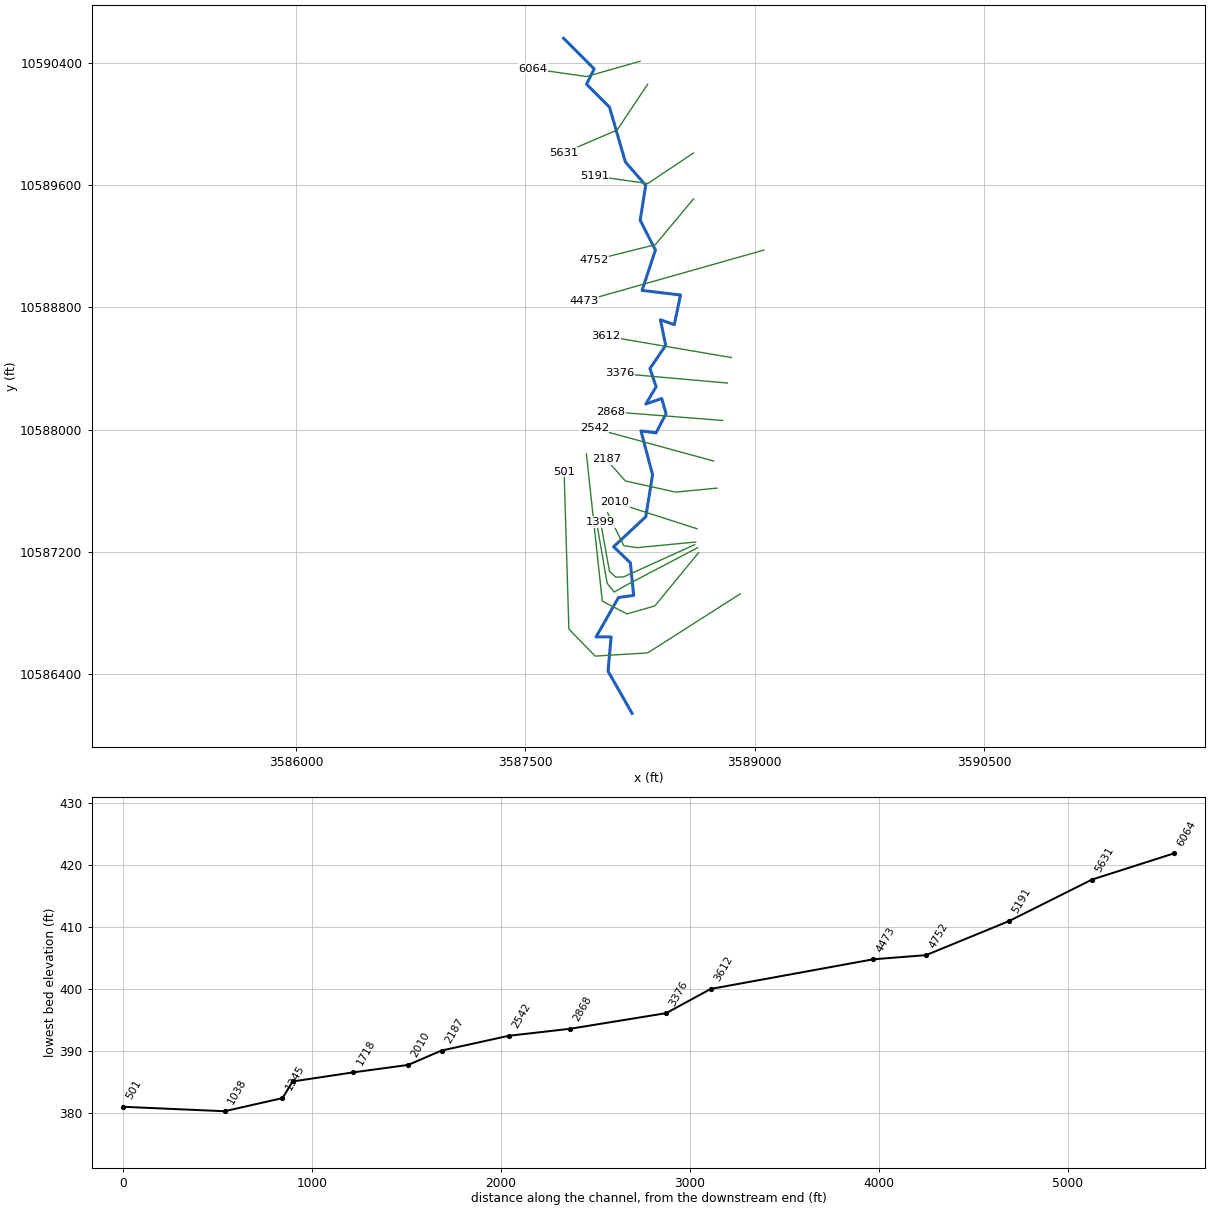
--- UNT 021 IN UKCR.prj (project) ---

Proj Title=UNT 021 IN UKCR Base Level Engineering
Current Plan=p01
Default Exp/Contr=0.3,0.1
English Units
Geom File=g01
Flow File=f01
Plan File=p01
Y Axis Title=Elevation
X Axis Title(PF)=Main Channel Distance
X Axis Title(XS)=Station
BEGIN DESCRIPTION:
UNT 021 IN UKCR
END DESCRIPTION:
DSS Export Rating Curves= 0
DSS Export Rating Curve Sorted= 0
DSS Export Volume Flow Curves= 0
DXF OffsetX= 0
DXF OffsetY= 0
DXF ScaleX= 1
DXF ScaleY= 10

--- UNT 021 IN UKCR.p01 (plan) ---

Plan Title=Multiple Run
Short Identifier=Multiple
Geom File=g01
Flow File=f01
Subcritical Flow
K Sum by GR= 0
Std Step Tol= 0.01
Critical Tol= 0.01
Num of Std Step Trials= 20
Max Error Tol= 0.3
Flow Tol Ratio= 0.001
Split Flow NTrial= 30
Split Flow Tol= 0.02
Split Flow Ratio= 0.02
Log Output Level= 0
Friction Slope Method= 1
Unsteady Friction Slope Method= 2
Unsteady Bridges Friction Slope Method= 1
Parabolic Critical Depth
Global Vel Dist=  1 , 1 , 1
Global Log Level= 0
CheckData=True
Encroach Param= -1, 0, 0, 0
BEGIN DESCRIPTION:
Multiple Run
END DESCRIPTION:

--- UNT 021 IN UKCR.f01 (steady flow) ---

Flow Title=Multiple
Number of Profiles=7
Profile Names=10-year,25-year,50-year,1pct_min,100-year,1pct_plu,500-year
River Rch & RM= UNT 021 IN UKCR,Reach-1,6064
     478     625     741     644     870    1177    1193
Boundary for River Rch & Prof#=UNT 021 IN UKCR,Reach-1,1
Up Type=0
Dn Type=3
Dn Slope=0.005
Boundary for River Rch & Prof#=UNT 021 IN UKCR,Reach-1,2
Up Type=0
Dn Type=3
Dn Slope=0.005
Boundary for River Rch & Prof#=UNT 021 IN UKCR,Reach-1,3
Up Type=0
Dn Type=3
Dn Slope=0.005
Boundary for River Rch & Prof#=UNT 021 IN UKCR,Reach-1,4
Up Type=0
Dn Type=3
Dn Slope=0.005
Boundary for River Rch & Prof#=UNT 021 IN UKCR,Reach-1,5
Up Type=0
Dn Type=3
Dn Slope=0.005
Boundary for River Rch & Prof#=UNT 021 IN UKCR,Reach-1,6
Up Type=0
Dn Type=3
Dn Slope=0.005
Boundary for River Rch & Prof#=UNT 021 IN UKCR,Reach-1,7
Up Type=0
Dn Type=3
Dn Slope=0.005

--- UNT 021 IN UKCR.g01 (geometry) ---

Geom Title=Existing Conditions

River Reach=UNT 021 IN UKCR,Reach-1
Reach XY= 30
      3587749.61     10590560.19      3587949.61     10590360.19
      3587899.61     10590260.19      3588049.61     10590110.19
      3588153.75     10589751.00      3588286.75     10589599.00
      3588250.50     10589371.00      3588349.75     10589175.00
      3588263.00     10588911.00      3588514.25     10588881.00
      3588473.75     10588687.00      3588383.00     10588719.00
      3588417.25     10588551.00      3588314.25     10588400.00
      3588355.00     10588281.00      3588287.50     10588168.00
      3588391.25     10588204.00      3588419.75     10588105.00
      3588354.00     10587979.00      3588255.50     10587992.00
      3588331.50     10587705.00      3588287.25     10587431.00
      3588076.50     10587234.00      3588186.25     10587129.00
      3588207.75     10586916.00      3588108.75     10586902.00
      3587961.75     10586644.00      3588060.25     10586644.00
      3588040.25     10586420.00      3588197.25     10586144.00

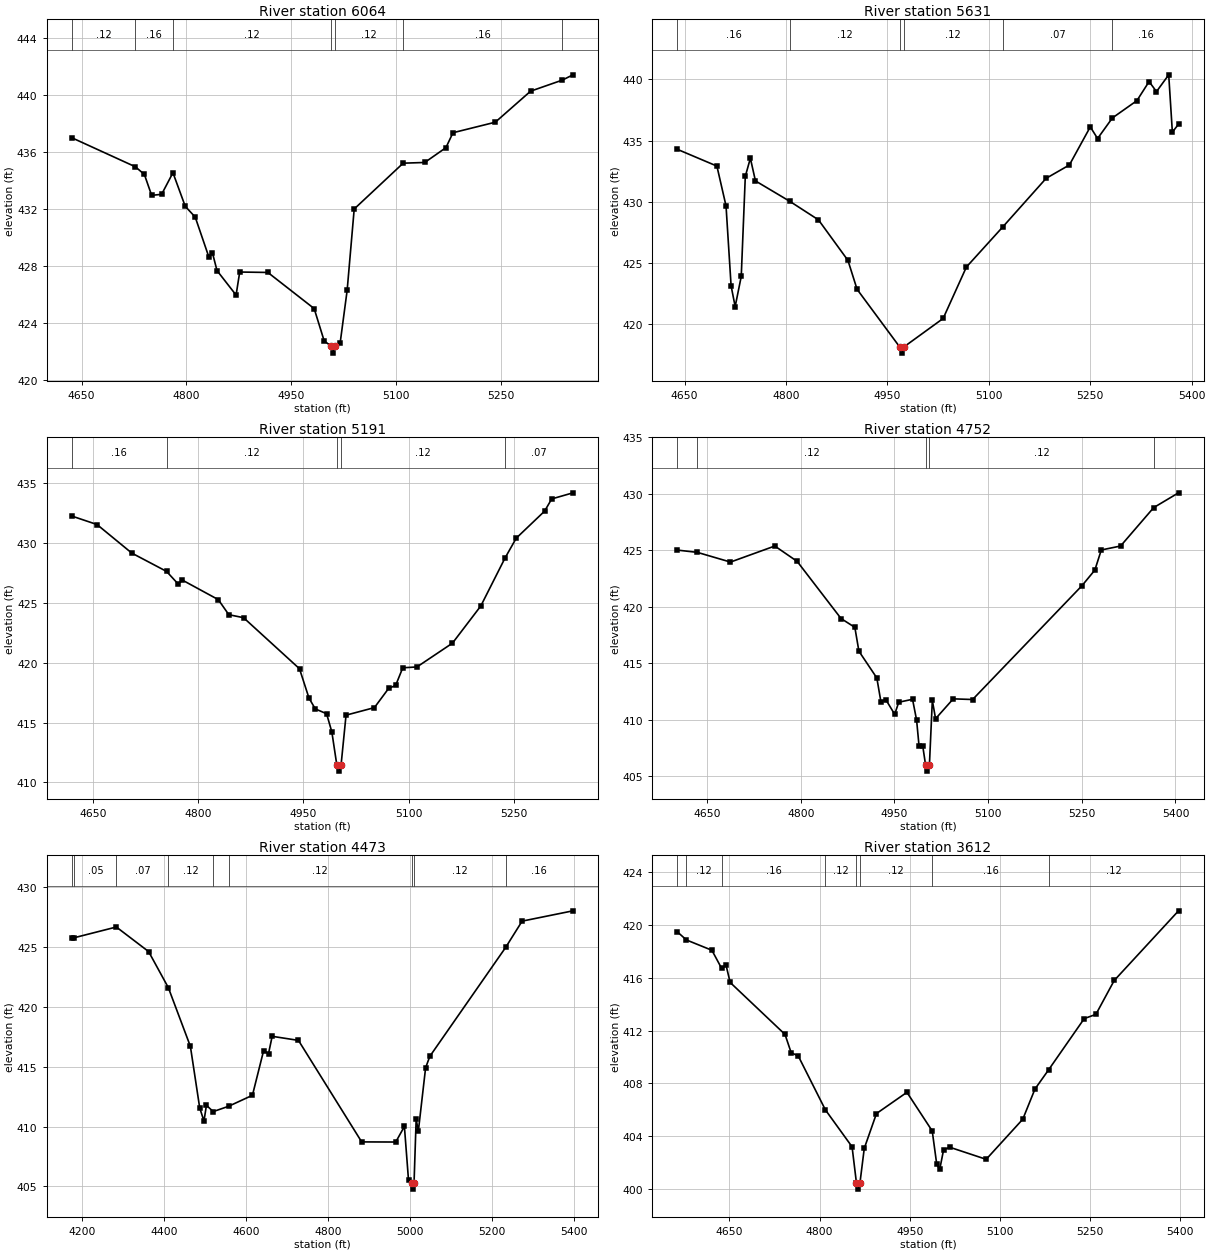
Type RM Length L Ch R = 1,6064,433,433,433
BEGIN DESCRIPTION:
UNT 021 IN UKCR 7.0
END DESCRIPTION:
XS GIS Cut Line= 3
      3588249.60     10590410.19      3587899.61     10590310.19
      3587549.56     10590360.20
#Sta/Elev= 30
  4636.0  437.02  4727.0  434.98  4740.0  434.44  4750.4  432.97  4764.7  433.04
  4780.9  434.56  4798.5  432.20  4812.8  431.44  4832.3  428.64  4837.5  428.92
  4844.0  427.68  4871.3  425.96  4876.5  427.58  4916.8  427.55  4983.1  425.01
  4997.4  422.74  5007.1  422.38  5009.9  421.88  5013.1  422.38  5020.2  422.56
  5030.3  426.29  5040.4  432.01  5110.5  435.23  5141.4  435.28  5171.7  436.32
  5181.8  437.37  5242.4  438.11  5292.9  440.29  5338.4  441.07  5353.6  441.44
#Mann=7,-1,0
  4636.0    0.12       0  4727.0    0.16       0  4780.9    0.12       0
  5007.1    0.07       0  5013.1    0.12       0  5110.5    0.16       0
  5338.4    0.05       0
Bank Sta=5007.1,5013.1
Exp/Cntr=0.3,0.1

Type RM Length L Ch R = 1,5631,440,440,440
BEGIN DESCRIPTION:
UNT 021 IN UKCR 6.0
END DESCRIPTION:
XS GIS Cut Line= 3
      3588299.59     10590260.16      3588099.61     10589960.19
      3587749.62     10589810.19
#Sta/Elev= 30
  4639.3  434.30  4697.9  432.93  4711.4  429.68  4718.9  423.15  4724.9  421.46
  4733.9  423.92  4739.9  432.09  4747.4  433.57  4754.9  431.72  4805.5  430.06
  4848.1  428.54  4891.7  425.23  4905.2  422.87  4968.3  418.16  4971.0  417.66
  4974.3  418.16  5032.5  420.49  5066.9  424.69  5120.8  427.97  5184.8  431.93
  5219.2  433.02  5250.1  436.13  5260.9  435.18  5282.8  436.86  5319.0  438.27
  5337.1  439.83  5348.0  439.01  5366.1  440.38  5371.5  435.70  5380.6  436.35
#Mann=6,-1,0
  4639.3    0.16       0  4805.5    0.12       0  4968.3    0.07       0
  4974.3    0.12       0  5120.8    0.07       0  5282.8    0.16       0
Bank Sta=4968.3,4974.3
Exp/Cntr=0.3,0.1

Type RM Length L Ch R = 1,5191,439,439,439
BEGIN DESCRIPTION:
UNT 021 IN UKCR 5.0
END DESCRIPTION:
XS GIS Cut Line= 3
      3588599.58     10589810.17      3588299.61     10589610.19
      3587949.59     10589660.19
#Sta/Elev= 30
  4619.9  432.28  4655.9  431.57  4705.5  429.18  4755.0  427.65  4771.6  426.59
  4777.6  426.92  4828.7  425.29  4843.7  424.03  4864.7  423.78  4944.4  419.51
  4957.9  417.06  4966.9  416.15  4983.0  415.75  4990.5  414.22  4997.6  411.45
  5000.4  410.95  5003.6  411.45  5010.7  415.63  5051.1  416.26  5071.3  417.86
  5081.4  418.12  5091.5  419.59  5111.7  419.66  5162.3  421.65  5202.7  424.76
  5237.3  428.78  5253.2  430.43  5293.6  432.69  5303.7  433.71  5334.0  434.22
#Mann=5,-1,0
  4619.9    0.16       0  4755.0    0.12       0  4997.6    0.07       0
  5003.6    0.12       0  5237.3    0.07       0
Bank Sta=4997.6,5003.6
Exp/Cntr=0.3,0.1

Type RM Length L Ch R = 1,4752,279,279,279
BEGIN DESCRIPTION:
UNT 021 IN UKCR 4.0
END DESCRIPTION:
XS GIS Cut Line= 3
      3588599.60     10589510.17      3588349.61     10589210.19
      3587949.61     10589110.19
#Sta/Elev= 30
  4602.1  425.02  4634.1  424.82  4687.3  423.96  4758.3  425.38  4794.1  424.02
  4864.4  418.96  4886.5  418.18  4893.0  416.07  4921.7  413.70  4928.2  411.61
  4936.0  411.79  4950.3  410.48  4956.8  411.55  4978.9  411.81  4985.4  409.97
  4989.3  407.69  4995.2  407.69  4999.9  405.95  5002.7  405.45  5005.9  405.95
  5010.6  411.71  5015.8  410.09  5044.1  411.85  5075.1  411.79  5250.3  421.87
  5270.9  423.25  5281.2  425.03  5312.1  425.38  5365.1  428.78  5404.9  430.09
#Mann=5,-1,0
  4602.1    0.16       0  4634.1    0.12       0  4999.9    0.07       0
  5005.9    0.12       0  5365.1    0.16       0
Bank Sta=4999.9,5005.9
Exp/Cntr=0.3,0.1

Type RM Length L Ch R = 1,4473,861,861,861
BEGIN DESCRIPTION:
Mapping XS c762072b
END DESCRIPTION:
XS GIS Cut Line= 2
      3589059.91     10589174.92      3587883.76     10588841.85
#Sta/Elev= 30
  4174.2  425.71  4180.8  425.76  4283.0  426.65  4361.7  424.60  4409.8  421.59
  4463.6  416.69  4486.3  411.56  4496.7  410.46  4502.7  411.77  4519.3  411.25
  4556.6  411.69  4614.9  412.61  4642.2  416.34  4654.1  416.08  4663.0  417.53
  4727.1  417.19  4881.3  408.72  4964.4  408.71  4985.5  410.01  4995.6  405.50
  5003.0  405.28  5005.7  404.78  5009.0  405.28  5014.2  410.63  5019.4  409.59
  5037.2  414.90  5047.5  415.86  5232.5  424.95  5272.6  427.14  5396.6  428.00
#Mann=9,-1,0
  4174.2    0.08       0  4180.8    0.05       0  4283.0    0.07       0
  4409.8    0.12       0  4519.3    0.07       0  4556.6    0.12       0
  5003.0    0.07       0  5009.0    0.12       0  5232.5    0.16       0
Bank Sta=5003,5009
Exp/Cntr=0.3,0.1

Type RM Length L Ch R = 1,3612,236,236,236
BEGIN DESCRIPTION:
UNT 021 IN UKCR 3.0
END DESCRIPTION:
XS GIS Cut Line= 2
      3588846.37     10588471.81      3588024.09     10588612.33
#Sta/Elev= 30
  4563.2  419.50  4578.5  418.88  4620.8  418.10  4637.1  416.72  4644.4  416.96
  4651.2  415.66  4742.5  411.72  4752.7  410.34  4764.6  410.08  4809.7  406.00
  4854.1  403.20  4861.3  400.49  4864.0  399.99  4867.3  400.49  4874.4  403.08
  4894.7  405.72  4945.4  407.33  4987.5  404.40  4995.0  401.88  5000.0  401.49
  5006.3  402.95  5016.4  403.17  5077.3  402.25  5138.2  405.29  5158.5  407.58
  5181.4  409.05  5240.5  412.92  5259.9  413.24  5290.4  415.81  5397.4  421.09
#Mann=8,-1,0
  4563.2    0.05       0  4578.5    0.12       0  4637.1    0.16       0
  4809.7    0.12       0  4861.3    0.07       0  4867.3    0.12       0
  4987.5    0.16       0  5181.4    0.12       0
Bank Sta=4861.3,4867.3
Exp/Cntr=0.3,0.1

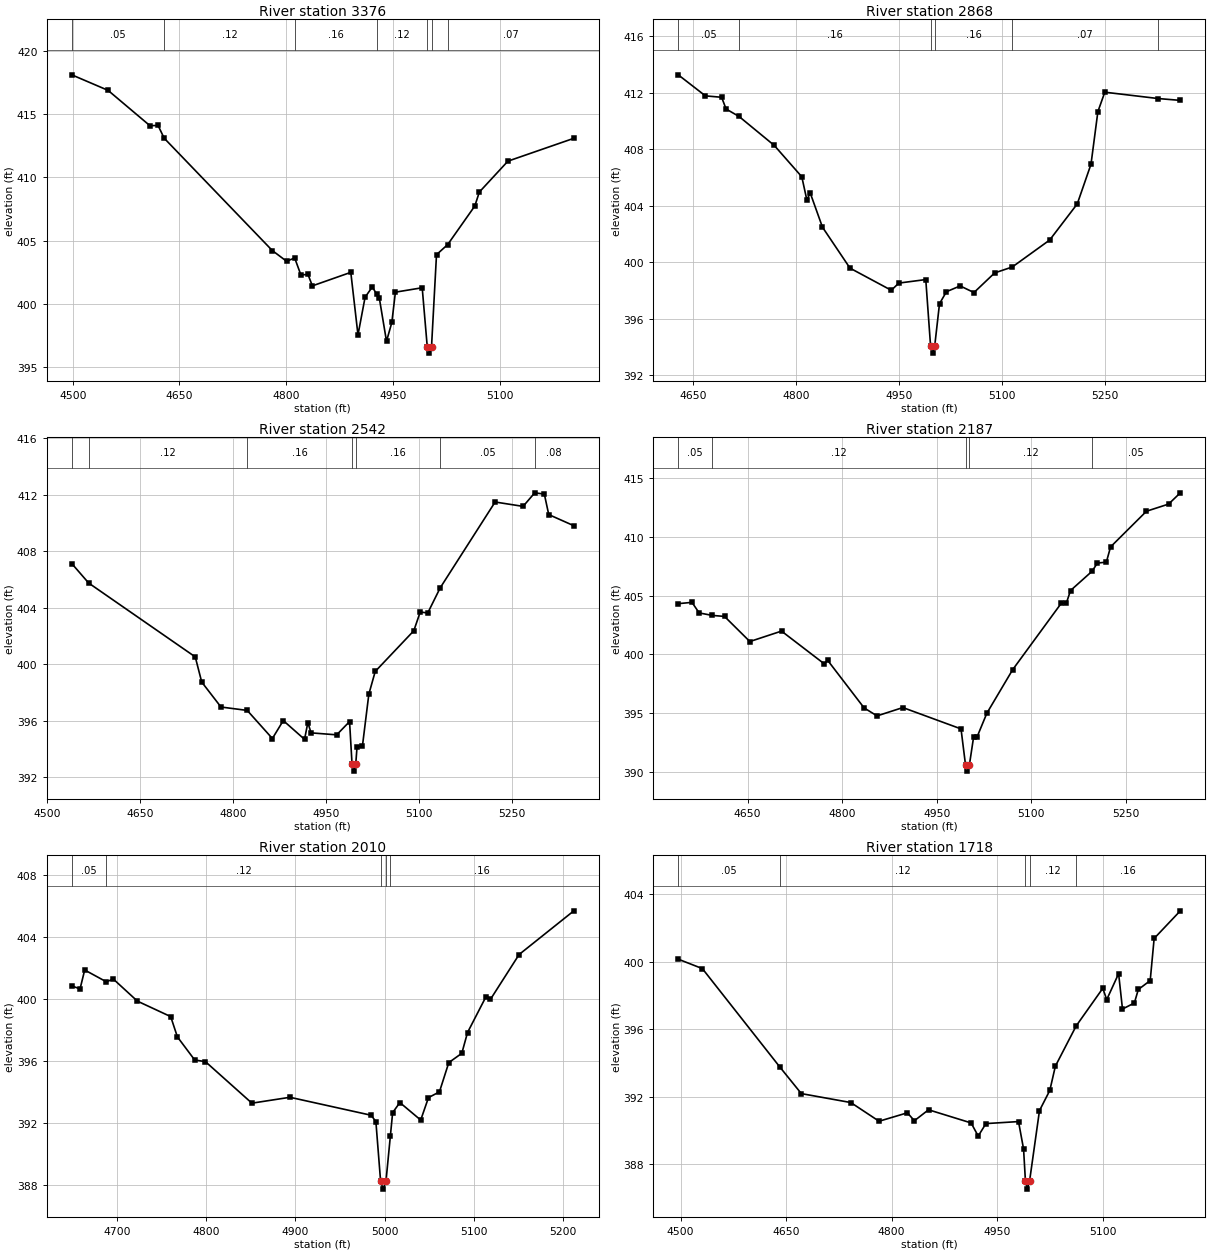
Type RM Length L Ch R = 1,3376,508,508,508
BEGIN DESCRIPTION:
Mapping XS 3e8ce3c3
END DESCRIPTION:
XS GIS Cut Line= 2
      3588820.41     10588305.13      3588117.28     10588367.63
#Sta/Elev= 30
  4498.6  418.13  4549.6  416.90  4608.5  414.10  4619.9  414.12  4628.5  413.11
  4780.5  404.21  4800.6  403.36  4812.0  403.62  4820.7  402.28  4830.7  402.31
  4836.9  401.41  4890.9  402.48  4901.0  397.52  4911.0  400.51  4921.1  401.32
  4927.5  400.74  4931.1  400.41  4941.1  397.02  4948.6  398.51  4953.6  400.91
  4991.3  401.26  4998.4  396.58  5001.1  396.08  5004.4  396.58  5011.4  403.88
  5027.1  404.68  5065.3  407.74  5071.6  408.84  5111.8  411.29  5204.5  413.10
#Mann=7,-1,0
  4498.6    0.05       0  4628.5    0.12       0  4812.0    0.16       0
  4927.5    0.12       0  4998.4    0.07       0  5004.4    0.12       0
  5027.1    0.07       0
Bank Sta=4998.4,5004.4
Exp/Cntr=0.3,0.1

Type RM Length L Ch R = 1,2868,326,326,326
BEGIN DESCRIPTION:
UNT 021 IN UKCR 2.0
END DESCRIPTION:
XS GIS Cut Line= 2
      3588789.07     10588060.35      3588059.92     10588117.64
#Sta/Elev= 30
  4627.9  413.27  4667.5  411.78  4691.1  411.68  4697.6  410.85  4716.5  410.32
  4767.8  408.27  4807.9  406.05  4815.2  404.42  4820.2  404.90  4838.0  402.48
  4878.1  399.58  4938.3  398.01  4949.2  398.52  4988.5  398.77  4995.5  394.06
  4998.3  393.56  5001.5  394.06  5008.5  397.06  5018.6  397.91  5038.6  398.32
  5058.7  397.85  5088.8  399.24  5114.5  399.66  5169.0  401.57  5209.2  404.13
  5229.2  406.94  5239.2  410.66  5249.3  412.04  5327.1  411.59  5359.3  411.46
#Mann=6,-1,0
  4627.9    0.05       0  4716.5    0.16       0  4995.5    0.07       0
  5001.5    0.16       0  5114.5    0.07       0  5327.1    0.15       0
Bank Sta=4995.5,5001.5
Exp/Cntr=0.3,0.1

Type RM Length L Ch R = 1,2542,355,355,355
BEGIN DESCRIPTION:
Mapping XS 06dc14d2
END DESCRIPTION:
XS GIS Cut Line= 2
      3588731.81     10587794.72      3587950.56     10588008.26
#Sta/Elev= 30
  4539.4  407.12  4566.7  405.74  4738.6  400.51  4749.0  398.73  4780.1  396.96
  4822.4  396.72  4863.0  394.73  4880.6  396.00  4914.9  394.67  4920.2  395.86
  4925.4  395.13  4966.7  394.99  4987.5  395.93  4991.5  392.92  4994.2  392.42
  4997.5  392.92  4999.6  394.16  5008.2  394.17  5018.6  397.87  5028.9  399.48
  5091.1  402.36  5101.5  403.69  5113.6  403.62  5133.7  405.40  5222.3  411.48
  5267.4  411.17  5286.2  412.13  5301.7  412.04  5308.8  410.59  5349.3  409.80
#Mann=7,-1,0
  4539.4    0.05       0  4566.7    0.12       0  4822.4    0.16       0
  4991.5    0.07       0  4997.5    0.16       0  5133.7    0.05       0
  5286.2    0.08       0
Bank Sta=4991.5,4997.5
Exp/Cntr=0.3,0.1

Type RM Length L Ch R = 1,2187,177,177,177
BEGIN DESCRIPTION:
Mapping XS bc7cfa05
END DESCRIPTION:
XS GIS Cut Line= 4
      3588752.65     10587617.63      3588481.83     10587591.59
      3588153.70     10587664.51      3588028.73     10587805.10
#Sta/Elev= 30
  4540.1  404.32  4561.9  404.43  4573.3  403.53  4593.8  403.32  4613.5  403.23
  4653.7  401.09  4703.9  401.98  4771.9  399.18  4776.9  399.50  4834.9  395.43
  4855.4  394.75  4896.4  395.46  4988.6  393.64  4995.8  390.54  4998.6  390.04
  5001.8  390.54  5008.5  392.93  5013.7  392.91  5029.6  394.98  5070.5  398.69
  5147.8  404.37  5155.6  404.36  5162.3  405.44  5196.4  407.08  5204.9  407.78
  5219.1  407.86  5225.8  409.16  5282.7  412.20  5317.8  412.81  5336.4  413.77
#Mann=5,-1,0
  4540.1    0.05       0  4593.8    0.12       0  4995.8    0.07       0
  5001.8    0.12       0  5196.4    0.05       0
Bank Sta=4995.8,5001.8
Exp/Cntr=0.3,0.1

Type RM Length L Ch R = 1,2010,292,292,292
BEGIN DESCRIPTION:
Mapping XS dc903a7d
END DESCRIPTION:
XS GIS Cut Line= 2
      3588622.42     10587352.02      3588085.98     10587523.89
#Sta/Elev= 30
  4649.0  400.84  4658.3  400.65  4663.5  401.87  4687.7  401.11  4695.7  401.28
  4722.6  399.86  4760.0  398.86  4767.5  397.55  4786.9  396.06  4799.0  395.95
  4851.1  393.27  4893.8  393.65  4984.9  392.49  4990.2  392.08  4995.5  388.22
  4998.2  387.72  5001.5  388.22  5006.5  391.18  5009.0  392.66  5017.1  393.31
  5040.5  392.18  5049.2  393.63  5061.5  394.00  5072.0  395.89  5086.6  396.49
  5093.0  397.83  5113.5  400.12  5118.7  399.97  5150.9  402.87  5212.3  405.69
#Mann=5,-1,0
  4649.0    0.05       0  4687.7    0.12       0  4995.5    0.07       0
  5001.5    0.12       0  5006.5    0.16       0
Bank Sta=4995.5,5001.5
Exp/Cntr=0.3,0.1

Type RM Length L Ch R = 1,1718,319,319,319
BEGIN DESCRIPTION:
Mapping XS ee78393c
END DESCRIPTION:
XS GIS Cut Line= 5
      3588613.79     10587265.06      3588229.64     10587228.16
      3588142.83     10587241.18      3588108.11     10587312.80
      3588037.23     10587456.70
#Sta/Elev= 30
  4496.6  400.16  4530.9  399.60  4641.2  393.75  4671.6  392.18  4741.9  391.65
  4782.1  390.54  4822.3  391.04  4832.3  390.57  4852.4  391.22  4912.9  390.44
  4923.0  389.66  4934.0  390.40  4980.3  390.52  4987.5  388.89  4990.1  387.01
  4992.8  386.51  4996.1  387.01  5010.1  391.17  5024.8  392.37  5032.7  393.81
  5062.3  396.20  5100.1  398.43  5105.7  397.76  5122.6  399.30  5128.1  397.20
  5145.0  397.56  5150.6  398.36  5167.5  398.89  5173.1  401.39  5210.3  403.03
#Mann=5,-1,0
  4496.6    0.05       0  4641.2    0.12       0  4990.1    0.07       0
  4996.1    0.12       0  5062.3    0.16       0
Bank Sta=4990.1,4996.1
Exp/Cntr=0.3,0.1

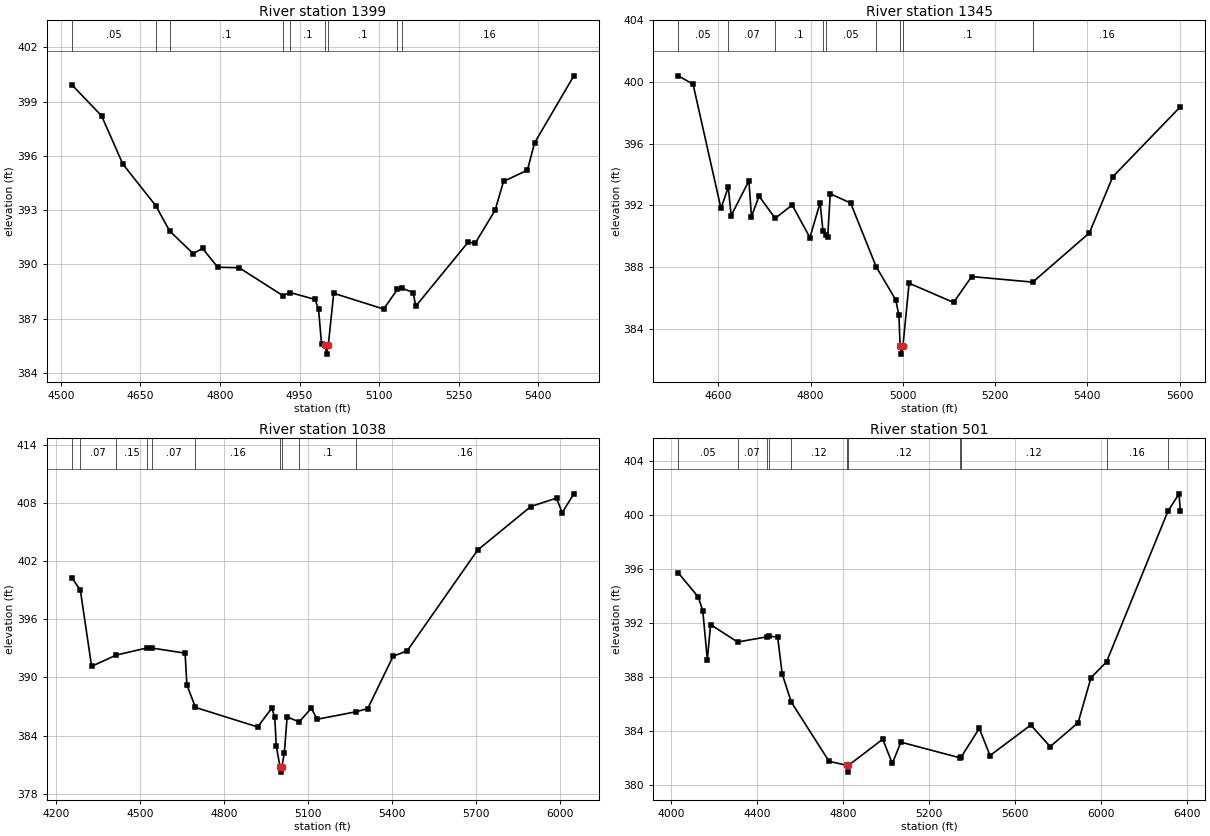
Type RM Length L Ch R = 1,1399,54,54,54
BEGIN DESCRIPTION:
Mapping XS a56c89cc
END DESCRIPTION:
XS GIS Cut Line= 5
      3588607.25     10587247.70      3588142.83     10587037.19
      3588090.75     10587035.02      3588049.51     10587074.08
      3587991.12     10587396.31
#Sta/Elev= 30
  4520.7  399.93  4576.9  398.21  4616.9  395.55  4679.2  393.24  4705.2  391.85
  4749.5  390.60  4767.1  390.89  4795.7  389.85  4836.3  389.82  4918.6  388.28
  4932.4  388.45  4979.2  388.07  4985.9  387.52  4991.4  385.62  4998.2  385.55
  5000.9  385.05  5004.2  385.55  5014.4  388.41  5108.5  387.54  5134.6  388.63
  5142.5  388.70  5164.0  388.45  5169.1  387.70  5267.7  391.23  5281.1  391.18
  5318.5  392.99  5334.5  394.59  5379.5  395.21  5393.0  396.72  5467.0  400.42
#Mann=9,-1,0
  4520.7    0.05       0  4679.2    0.07       0  4705.2     0.1       0
  4918.6    0.12       0  4932.4     0.1       0  4998.2    0.07       0
  5004.2     0.1       0  5134.6    0.12       0  5142.5    0.16       0
Bank Sta=4998.2,5004.2
Exp/Cntr=0.3,0.1

Type RM Length L Ch R = 1,1345,307,307,307
BEGIN DESCRIPTION:
Mapping XS 6c353503
END DESCRIPTION:
XS GIS Cut Line= 5
      3588626.75     10587228.15      3588155.85     10586980.77
      3588079.90     10586937.36      3588034.32     10586995.96
      3587967.04     10587384.44
#Sta/Elev= 30
  4513.4  400.41  4545.5  399.87  4606.0  391.81  4621.9  393.20  4628.0  391.34
  4666.5  393.60  4672.1  391.28  4688.5  392.61  4723.4  391.17  4760.3  392.03
  4798.7  389.92  4820.8  392.18  4827.0  390.36  4832.9  390.11  4837.2  389.93
  4842.8  392.76  4886.9  392.16  4942.3  388.03  4984.6  385.88  4991.5  384.90
  4994.2  382.86  4996.9  382.36  5000.2  382.86  5013.6  386.96  5110.1  385.71
  5149.1  387.39  5281.6  387.03  5404.2  390.22  5454.9  393.86  5601.3  398.40
#Mann=9,-1,0
  4513.4    0.05       0  4621.9    0.07       0  4723.4     0.1       0
  4827.0    0.07       0  4832.9    0.05       0  4942.3     0.1       0
  4994.2    0.07       0  5000.2     0.1       0  5281.6    0.16       0
Bank Sta=4994.2,5000.2
Exp/Cntr=0.3,0.1

Type RM Length L Ch R = 1,1038,537,537,537
BEGIN DESCRIPTION:
Mapping XS 79544f88
END DESCRIPTION:
XS GIS Cut Line= 5
      3588632.88     10587195.77      3588346.41     10586846.80
      3588164.12     10586794.72      3588002.66     10586878.05
      3587898.50     10587841.57
#Sta/Elev= 30
  4257.4  400.29  4288.0  399.00  4328.2  391.15  4415.8  392.31  4525.3  393.04
  4542.5  393.04  4661.8  392.51  4668.3  389.23  4698.9  386.91  4920.9  384.90
  4971.1  386.83  4981.7  385.95  4987.3  382.94  5000.9  380.74  5003.6  380.24
  5006.9  380.74  5016.1  382.25  5026.0  385.93  5069.0  385.42  5112.5  386.84
  5132.6  385.69  5271.1  386.46  5313.7  386.79  5404.2  392.19  5454.5  392.75
  5705.9  403.14  5895.7  407.63  5987.5  408.50  6007.7  406.99  6049.3  408.94
#Mann=10,-1,0
  4257.4    0.05       0  4288.0    0.07       0  4415.8    0.15       0
  4525.3     0.1       0  4542.5    0.07       0  4698.9    0.16       0
  5000.9    0.07       0  5006.9    0.16       0  5069.0     0.1       0
  5271.1    0.16       0
Bank Sta=5000.9,5006.9
Exp/Cntr=0.3,0.1

Type RM Length L Ch R = 1,501,0,0,0
BEGIN DESCRIPTION:
UNT 021 IN UKCR 1.0
END DESCRIPTION:
XS GIS Cut Line= 5
      3588903.74     10586924.95      3588299.54     10586539.51
      3587955.79     10586518.68      3587783.91     10586695.76
      3587752.69     10587726.15
#Sta/Elev= 30
  4032.0  395.73  4125.2  393.94  4146.4  392.91  4167.5  389.30  4182.7  391.89
  4308.6  390.60  4443.8  390.98  4454.4  391.02  4495.0  390.98  4516.1  388.24
  4558.3  386.16  4734.5  381.76  4818.9  381.46  4821.7  380.96  4824.9  381.46
  4984.7  383.40  5029.1  381.60  5069.2  383.18  5344.5  382.02  5348.7  382.05
  5434.3  384.20  5484.3  382.19  5674.4  384.45  5764.5  382.85  5894.5  384.62
  5954.5  387.95  6027.0  389.13  6312.7  400.28  6364.7  401.58  6370.7  400.31
#Mann=11,-1,0
  4032.0    0.05       0  4308.6    0.07       0  4443.8    0.12       0
  4454.4    0.16       0  4558.3    0.12       0  4818.9    0.07       0
  4824.9    0.12       0  5344.5    0.07       0  5348.7    0.12       0
  6027.0    0.16       0  6312.7    0.12       0
Bank Sta=4818.9,4824.9
Exp/Cntr=0.3,0.1

Chan Stop Cuts=-1