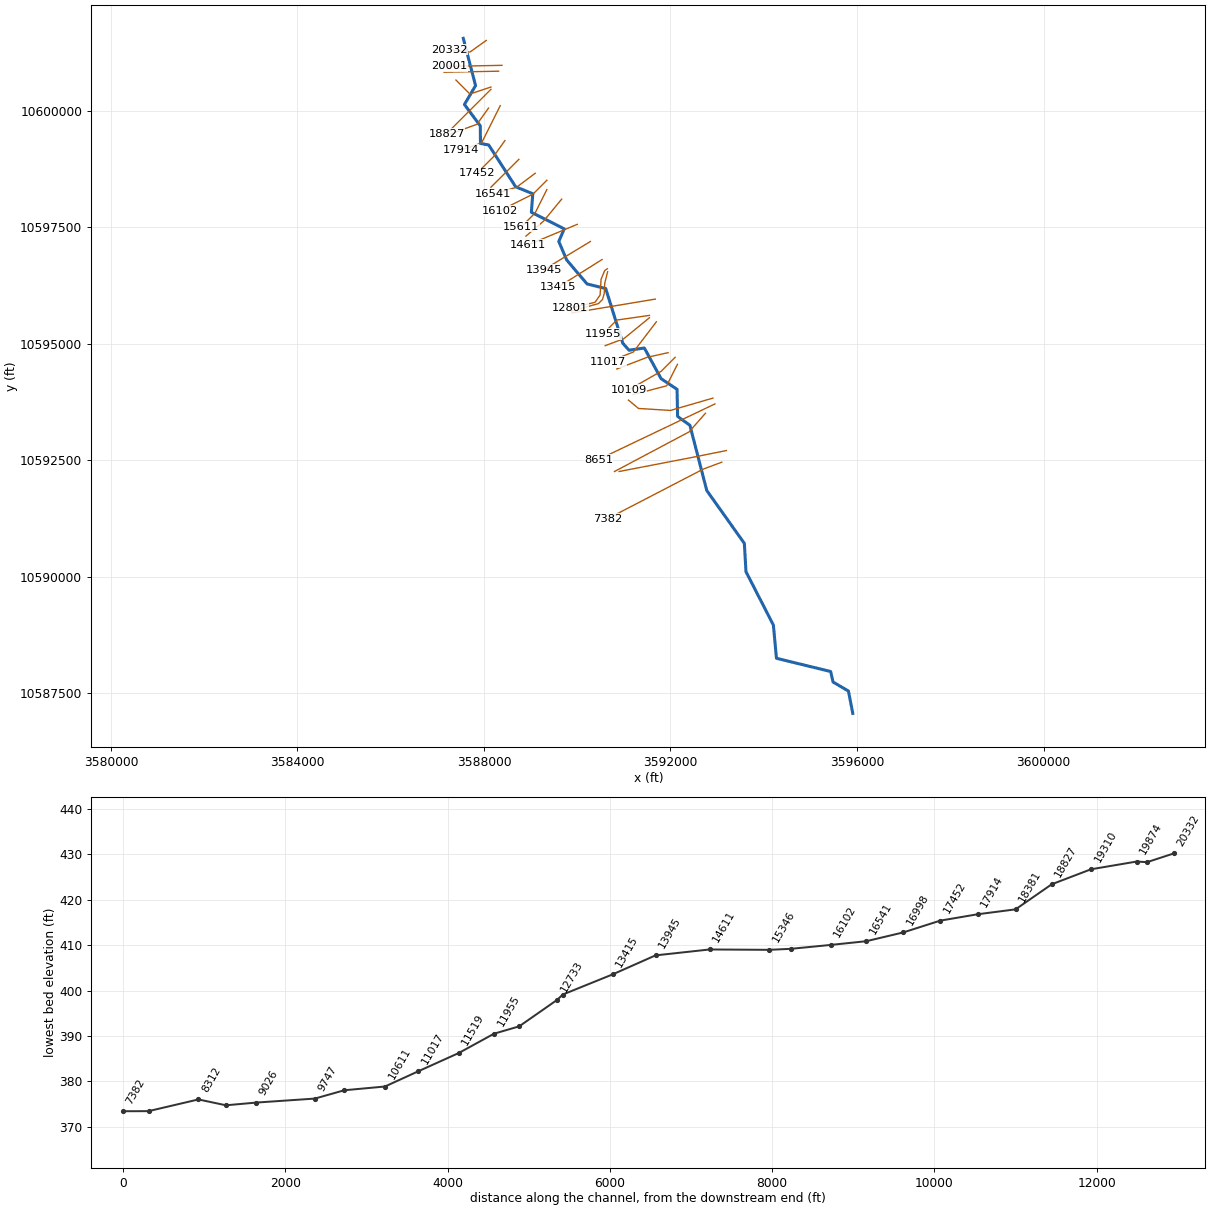
--- UNT 022 IN UKCR.prj (project) ---

Proj Title=UNT 022 IN UKCR Base Level Engineering
Current Plan=p01
Default Exp/Contr=0.3,0.1
English Units
Geom File=g01
Flow File=f01
Plan File=p01
Y Axis Title=Elevation
X Axis Title(PF)=Main Channel Distance
X Axis Title(XS)=Station
BEGIN DESCRIPTION:
UNT 022 IN UKCR
END DESCRIPTION:
DSS Export Rating Curves= 0
DSS Export Rating Curve Sorted= 0
DSS Export Volume Flow Curves= 0
DXF OffsetX= 0
DXF OffsetY= 0
DXF ScaleX= 1
DXF ScaleY= 10

--- UNT 022 IN UKCR.p01 (plan) ---

Plan Title=Multiple Run
Short Identifier=Multiple
Geom File=g01
Flow File=f01
Subcritical Flow
K Sum by GR= 0
Std Step Tol= 0.01
Critical Tol= 0.01
Num of Std Step Trials= 20
Max Error Tol= 0.3
Flow Tol Ratio= 0.001
Split Flow NTrial= 30
Split Flow Tol= 0.02
Split Flow Ratio= 0.02
Log Output Level= 0
Friction Slope Method= 1
Unsteady Friction Slope Method= 2
Unsteady Bridges Friction Slope Method= 1
Parabolic Critical Depth
Global Vel Dist=  1 , 1 , 1
Global Log Level= 0
CheckData=True
Encroach Param= -1, 0, 0, 0
BEGIN DESCRIPTION:
Multiple Run
END DESCRIPTION:

--- UNT 022 IN UKCR.f01 (steady flow) ---

Flow Title=Multiple
Program Version=4.10
Number of Profiles= 7
Profile Names=10-year,25-year,50-year,1pct_min,100-year,1pct_plu,500-year
River Rch & RM=UNT 022 IN UKCR,Reach-1         ,20332
     965    1307    1585    1403    1898    2567    2709
River Rch & RM=UNT 022 IN UKCR,Reach-1         ,19874
    1182    1616    1973    1756    2374    3211    3427
River Rch & RM=UNT 022 IN UKCR,Reach-1         ,12265
    2240    3165    3948    3583    4846    6553    7278
River Rch & RM=UNT 022 IN UKCR,Reach-1         ,8651
    3362    4834    6102    5595    7567   10233   11607
River Rch & RM=UNT 022 IN UKCR,Reach-1         ,6466
    3362    4834    6102    5595    7567   10233   11607
River Rch & RM=UNT 022 IN UKCR,Reach-1         ,4215
    3362    4834    6102    5595    7567   10233   11607
Boundary for River Rch & Prof#=UNT 022 IN UKCR,Reach-1         , 1
Up Type= 0
Dn Type= 3
Dn Slope=0.005
Boundary for River Rch & Prof#=UNT 022 IN UKCR,Reach-1         , 2
Up Type= 0
Dn Type= 3
Dn Slope=0.005
Boundary for River Rch & Prof#=UNT 022 IN UKCR,Reach-1         , 3
Up Type= 0
Dn Type= 3
Dn Slope=0.005
Boundary for River Rch & Prof#=UNT 022 IN UKCR,Reach-1         , 4
Up Type= 0
Dn Type= 3
Dn Slope=0.005
Boundary for River Rch & Prof#=UNT 022 IN UKCR,Reach-1         , 5
Up Type= 0
Dn Type= 3
Dn Slope=0.005
Boundary for River Rch & Prof#=UNT 022 IN UKCR,Reach-1         , 6
Up Type= 0
Dn Type= 3
Dn Slope=0.005
Boundary for River Rch & Prof#=UNT 022 IN UKCR,Reach-1         , 7
Up Type= 0
Dn Type= 3
Dn Slope=0.005
DSS Import GetInterval= 0
DSS Import GetPeak= 0
DSS Import FillOption= 0

--- UNT 022 IN UKCR.g01 (geometry) ---

Geom Title=Existing Conditions
Program Version=4.10

River Reach=UNT 022 IN UKCR ,Reach-1
Reach XY= 30
      3587557.25       10601555.        3587820.       10600540.
      3587581.25       10600135.      3587921.75       10599678.
       3587925.5       10599299.      3588101.75       10599267.
       3588679.5       10598370.      3589047.75       10598220.
      3589016.75       10597823.        3589722.       10597467.
      3589605.25       10597196.       3589772.5       10596801.
      3590211.75       10596284.        3590611.       10596186.
        3590977.       10595014.        3591111.       10594863.
       3591439.5       10594910.       3591798.5       10594252.
        3592141.       10594024.        3592153.       10593442.
      3592417.25       10593251.      3592777.75       10591853.
      3593584.25       10590718.        3593619.       10590111.
      3594206.75       10588964.      3594272.75       10588252.
      3595435.25       10587968.        3595486.       10587743.
      3595816.25       10587549.       3595909.5       10587070.

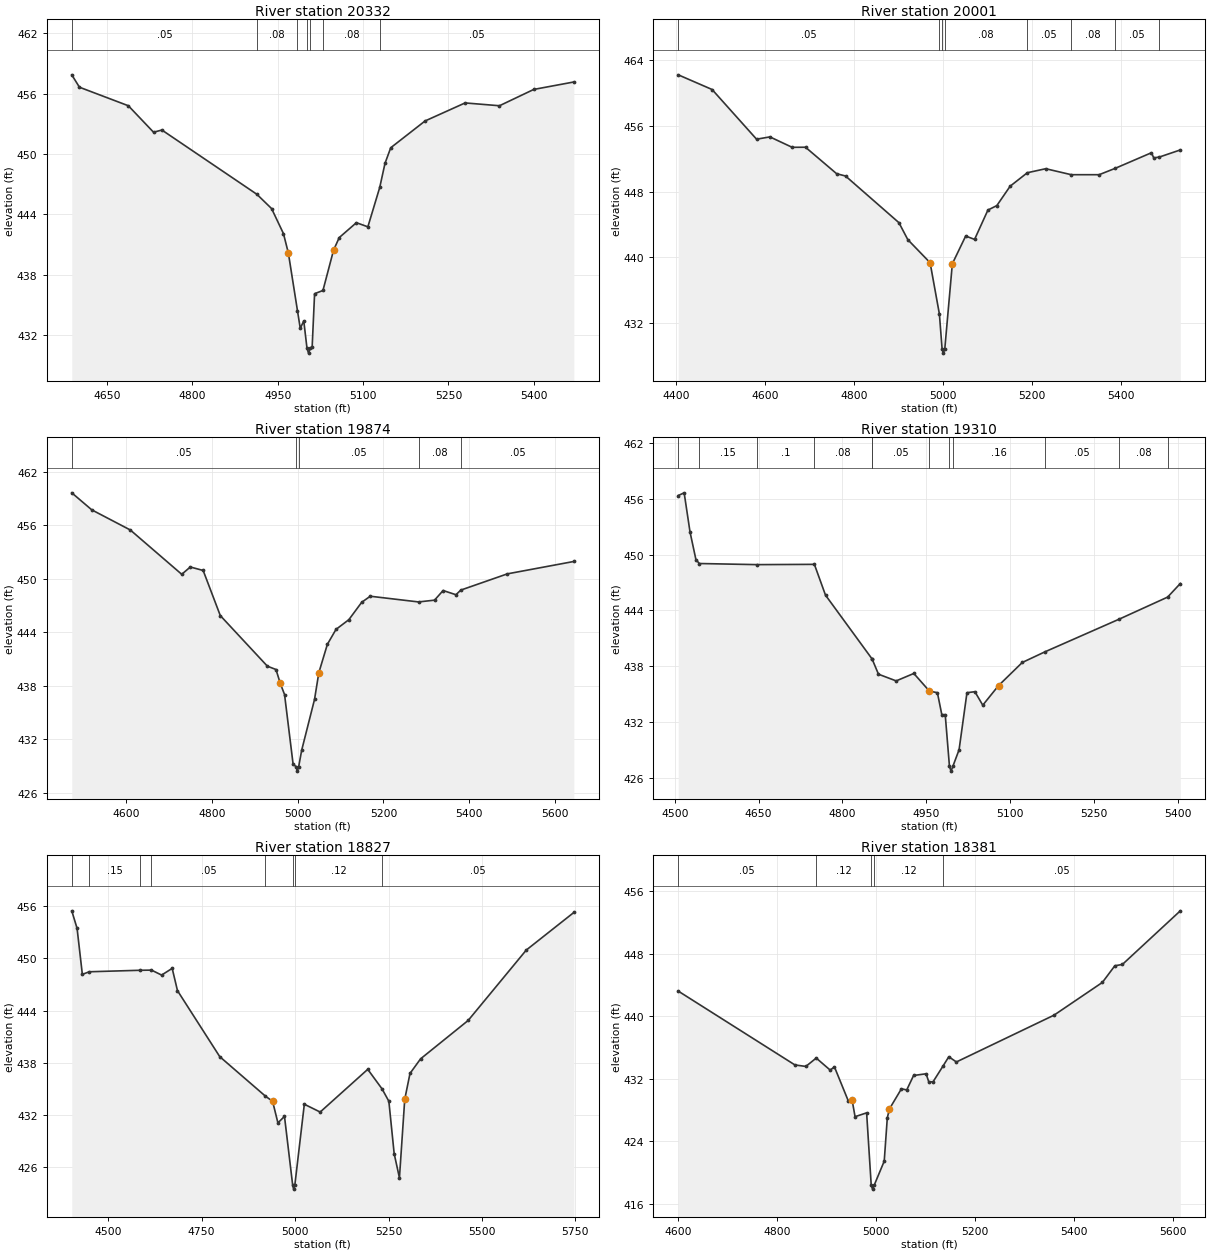
Type RM Length L Ch R = 1 ,20332   ,331,331,331
BEGIN DESCRIPTION:
UNT 022 IN UKCR 38.0
END DESCRIPTION:
XS GIS Cut Line= 3
       3588049.6     10601510.18      3587699.61     10601260.19
      3587249.58     10601310.19
#Sta/Elev= 30
  4587.7  457.86  4601.2  456.63  4687.2  454.79  4731.5  452.16  4746.2  452.38
  4913.2     446  4939.1  444.58    4960  442.09  4968.6  440.16  4984.6  434.44
  4989.5  432.69  4995.7  433.43  5001.3  430.73    5004  430.23  5007.3  430.73
  5010.4  430.81  5014.7  436.13  5029.4  436.45    5048  440.44    5058   441.7
  5088.2  443.18  5108.4  442.77  5129.3  446.69  5138.5  449.07  5148.6  450.62
    5209  453.28  5279.4  455.07  5339.8  454.79  5400.1  456.41  5470.6  457.15
#Mann= 7 ,-1 , 0
  4587.7     .05       0  4913.2     .08       0  4984.6     .05       0
  5001.3     .03       0  5007.3     .05       0  5029.4     .08       0
  5129.3     .05       0
Bank Sta=4968.6,5048
XS Rating Curve= 0 ,0
Exp/Cntr=0.3,0.1

Type RM Length L Ch R = 1 ,20001   ,127,127,127
BEGIN DESCRIPTION:
Mapping XS 5511f969
END DESCRIPTION:
XS GIS Cut Line= 2
      3588385.66      10600975.7      3587257.16     10600953.99
#Sta/Elev= 30
  4404.2  462.24  4480.3  460.45  4580.3  454.39  4610.3  454.67  4660.3   453.4
  4690.3  453.41  4760.3  450.18  4780.3   449.9  4900.3  444.21  4920.3  442.14
  4970.4  439.33  4991.3  433.07  4997.4   428.8  5000.1   428.3  5003.4   428.8
  5020.4   439.2  5050.4  442.58  5070.4  442.17  5100.4  445.75  5120.4  446.29
  5150.4  448.66    5189   450.3  5230.4  450.79  5287.8  450.06  5350.4  450.06
  5386.7  450.84  5468.1  452.74  5473.1  452.11  5485.6  452.21  5532.9  453.08
#Mann= 8 ,-1 , 0
  4404.2     .05       0  4991.3     .08       0  4997.4     .07       0
  5003.4     .08       0    5189     .05       0  5287.8     .08       0
  5386.7     .05       0  5485.6     .08       0
Bank Sta=4970.4,5020.4
XS Rating Curve= 0 ,0
Exp/Cntr=0.3,0.1

Type RM Length L Ch R = 1 ,19874   ,564,564,564
BEGIN DESCRIPTION:
UNT 022 IN UKCR 37.0
END DESCRIPTION:
XS GIS Cut Line= 2
      3588316.26     10600849.83      3587144.46     10600828.13
#Sta/Elev= 30
  4472.4  459.66  4519.1  457.75  4609.1  455.49  4729.1  450.52  4749.1  451.34
  4779.1  450.95  4819.1  445.89  4929.1  440.21  4949.1  439.84  4959.1  438.29
  4969.1  437.03  4989.1  429.21  4996.1  428.94  4998.9  428.44  5002.1  428.94
  5009.1  430.79  5039.1  436.49  5049.1  439.48  5069.1  442.67  5089.2  444.34
  5119.2  445.43  5149.2  447.38  5169.2  448.06  5281.8  447.42  5319.2  447.62
  5339.2   448.7  5369.2  448.23  5380.6  448.75  5489.2  450.57  5644.4  451.96
#Mann= 5 ,-1 , 0
  4472.4     .05       0  4996.1     .03       0  5002.1     .05       0
  5281.8     .08       0  5380.6     .05       0
Bank Sta=4959.1,5049.1
XS Rating Curve= 0 ,0
Exp/Cntr=0.3,0.1

Type RM Length L Ch R = 1 ,19310   ,483,483,483
BEGIN DESCRIPTION:
UNT 022 IN UKCR 36.0
END DESCRIPTION:
XS GIS Cut Line= 3
      3588149.66      10600510.2      3587699.61     10600360.19
      3587399.58     10600660.22
#Sta/Elev= 30
    4506  456.36  4516.6  456.65  4527.1  452.44  4537.7  449.46  4543.8  449.05
  4646.8  448.93  4749.7  448.96  4769.6  445.65  4852.6  438.82    4853  438.79
  4864.4  437.15  4896.1  436.43  4927.7  437.23  4955.5  435.34  4969.9  435.16
  4977.8   432.8  4983.9   432.8  4991.5  427.23  4994.3  426.73  4997.5  427.23
  5008.7  429.03  5022.8  435.16    5037  435.27  5051.1  433.82  5079.4  435.93
  5121.8  438.41  5162.2  439.55  5295.7  443.08    5382  445.44  5404.7   446.9
#Mann= 12 ,-1 , 0
    4506     .05       0  4543.8     .15       0  4646.8      .1       0
  4749.7     .08       0  4852.6     .16       0    4853     .05       0
  4955.5     .16       0  4991.5     .07       0  4997.5     .16       0
  5162.2     .05       0  5295.7     .08       0    5382     .05       0
Bank Sta=4955.5,5079.4
XS Rating Curve= 0 ,0
Exp/Cntr=0.3,0.1

Type RM Length L Ch R = 1 ,18827   ,446,446,446
BEGIN DESCRIPTION:
UNT 022 IN UKCR 35.0
END DESCRIPTION:
XS GIS Cut Line= 3
      3588149.62     10600460.19      3587749.61     10600060.19
      3587199.62      10599510.2
#Sta/Elev= 30
  4402.4  455.49  4416.6  453.47  4430.7  448.17  4449.2  448.47  4583.8  448.64
  4615.7  448.66  4642.8  448.09  4671.1  448.86  4685.3  446.29  4798.4  438.69
  4920.6  434.14  4939.8  433.55    4954  431.06  4971.6  431.81  4993.4  423.93
  4996.1  423.43  4999.4  423.93  5024.7  433.21  5067.1  432.31  5194.4  437.23
  5232.8  434.97  5250.9  433.55  5265.1  427.52  5279.2  424.73  5293.4  433.78
  5307.5  436.76  5335.8  438.44  5463.1  442.86  5618.6  450.97  5745.9   455.3
#Mann= 8 ,-1 , 0
  4402.4     .05       0  4449.2     .15       0  4583.8      .1       0
  4615.7     .05       0  4920.6     .12       0  4993.4     .07       0
  4999.4     .12       0  5232.8     .05       0
Bank Sta=4939.8,5293.4
XS Rating Curve= 0 ,0
Exp/Cntr=0.3,0.1

Type RM Length L Ch R = 1 ,18381   ,467,467,467
BEGIN DESCRIPTION:
UNT 022 IN UKCR 34.0
END DESCRIPTION:
XS GIS Cut Line= 3
      3588099.63     10600060.22      3587849.61     10599710.19
      3587299.59     10599510.18
#Sta/Elev= 30
  4599.5  443.24  4835.5  433.79  4857.6   433.6  4878.6  434.67  4906.8  433.13
  4915.4  433.54  4943.6  429.16    4951  429.35  4957.1  427.17  4980.5  427.66
  4989.8   418.4  4992.5   417.9  4995.8   418.4  5016.1  421.48  5022.3  427.01
  5026.6  428.16  5050.9  430.74  5061.6  430.59  5075.5  432.44  5100.8  432.66
  5106.1  431.64  5114.8  431.63  5135.5   433.7  5146.7  434.84    5162  434.17
  5359.5  440.16  5457.3  444.35  5482.5  446.48  5497.8  446.65  5614.9  453.51
#Mann= 5 ,-1 , 0
  4599.5     .05       0  4878.6     .12       0  4989.8     .07       0
  4995.8     .12       0  5135.5     .05       0
Bank Sta=4951,5026.6
XS Rating Curve= 0 ,0
Exp/Cntr=0.3,0.1

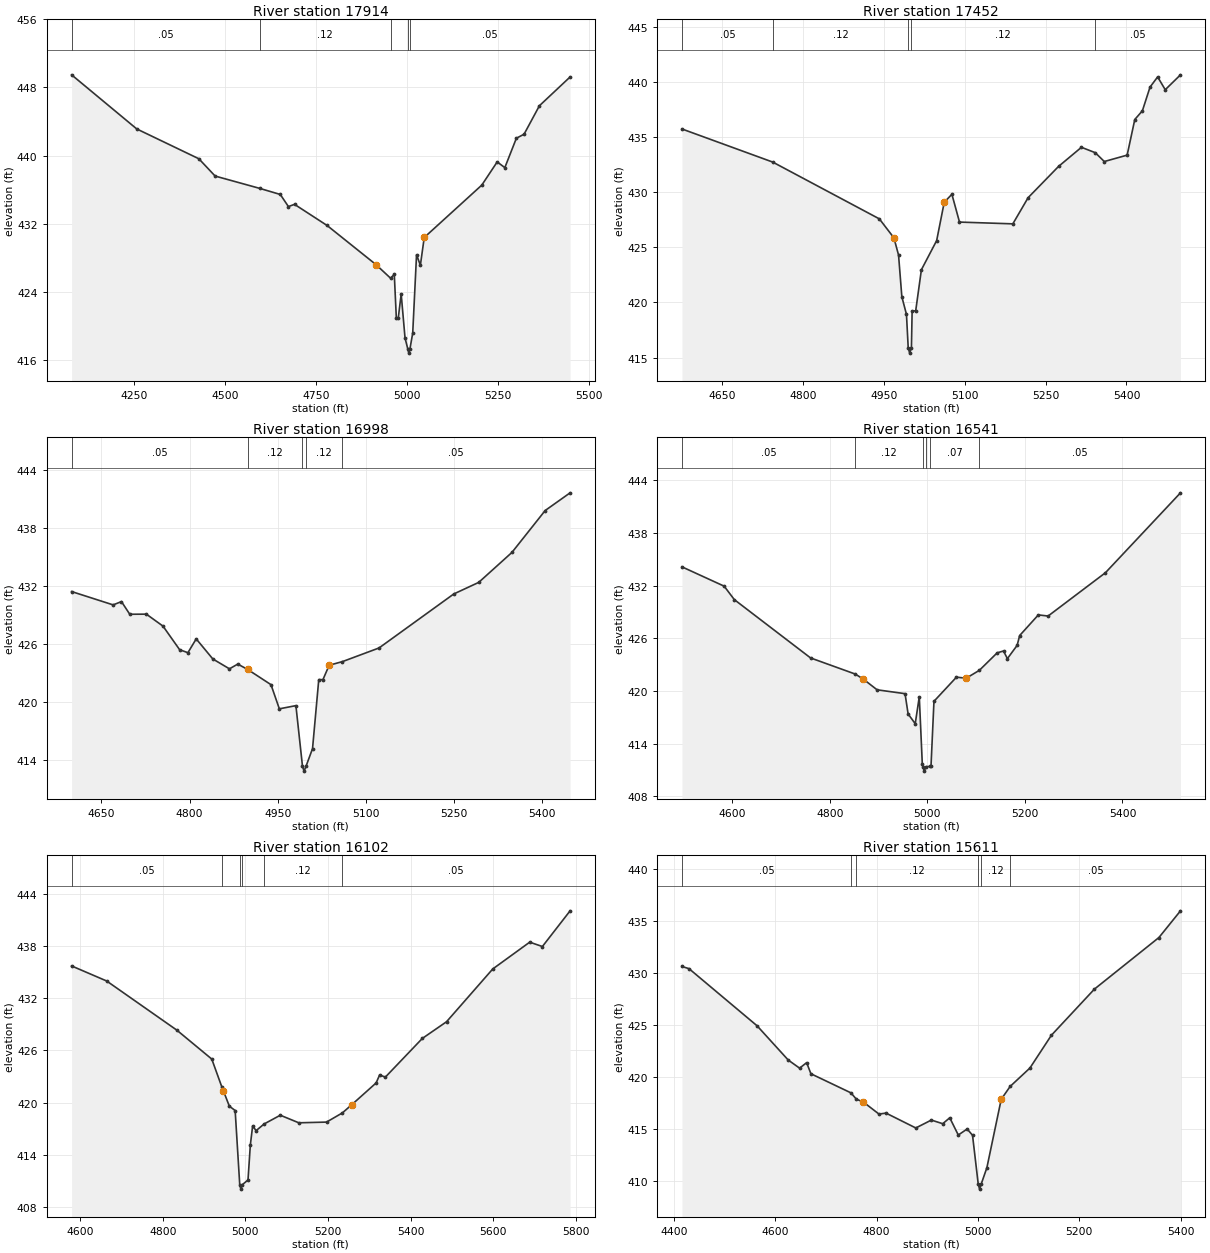
Type RM Length L Ch R = 1 ,17914   ,462,462,462
BEGIN DESCRIPTION:
UNT 022 IN UKCR 33.0
END DESCRIPTION:
XS GIS Cut Line= 3
       3588349.6     10600110.17      3587949.61     10599310.19
      3587499.65      10599160.2
#Sta/Elev= 30
  4079.1  449.48    4258  443.13  4428.5  439.63  4473.2   437.6  4595.1  436.16
  4652.1  435.44  4674.4  434.02  4691.2  434.28  4780.6   431.8  4914.8  427.21
  4954.7  425.62  4965.1  426.06  4970.7  420.96  4976.1  420.96    4984  423.76
  4994.6   418.6  5002.1  417.32  5004.9  416.82  5008.1  417.32  5015.7  419.18
  5026.2  428.37  5036.7  427.13  5047.3  430.39  5205.4  436.54  5247.6  439.26
  5268.6  438.59  5300.3  442.04  5321.4  442.51  5363.5  445.85  5447.8  449.23
#Mann= 5 ,-1 , 0
  4079.1     .05       0  4595.1     .12       0  4954.7     .05       0
  5002.1    .035       0  5008.1     .05       0
Bank Sta=4914.8,5047.3
XS Rating Curve= 0 ,0
Exp/Cntr=0.3,0.1

Type RM Length L Ch R = 1 ,17452   ,454,454,454
BEGIN DESCRIPTION:
UNT 022 IN UKCR 32.0
END DESCRIPTION:
XS GIS Cut Line= 3
      3588449.63     10599360.22      3588199.61     10599010.19
      3587849.63     10598660.21
#Sta/Elev= 30
  4575.2  435.73  4743.6  432.73  4941.5  427.58  4968.5  425.86  4977.1   424.3
  4983.2  420.52  4991.8  418.92    4995  415.91  4997.7  415.41    5001  415.91
  5002.3  419.24  5008.9  419.24  5019.5  422.97  5047.8  425.61  5061.9  429.09
  5076.1  429.81  5090.2  427.29  5189.2  427.13  5217.5   429.5  5274.1  432.34
  5316.5  434.07  5342.2  433.58  5358.9  432.78  5401.3  433.36  5415.5  436.59
  5429.6  437.38  5443.8  439.53  5457.9  440.45    5472  439.29  5500.3  440.64
#Mann= 5 ,-1 , 0
  4575.2     .05       0  4743.6     .12       0    4995     .07       0
    5001     .12       0  5342.2     .05       0
Bank Sta=4968.5,5061.9
XS Rating Curve= 0 ,0
Exp/Cntr=0.3,0.1

Type RM Length L Ch R = 1 ,16998   ,457,457,457
BEGIN DESCRIPTION:
UNT 022 IN UKCR 31.0
END DESCRIPTION:
XS GIS Cut Line= 3
      3588749.61     10598960.19      3588449.61     10598660.19
      3588149.63     10598360.21
#Sta/Elev= 30
  4599.3  431.41    4670  430.03  4684.2  430.37  4698.3  429.06  4726.6  429.07
  4754.9  427.83  4783.2  425.39  4797.3  425.08  4811.4  426.51  4839.7  424.43
    4868  423.41  4882.1   423.9  4898.9  423.35  4938.7  421.77  4952.9  419.27
  4981.1   419.6  4992.3  413.32    4995  412.82  4998.3  413.32  5009.4  415.15
    5020  422.29  5027.1  422.29  5037.7  423.78  5060.4  424.16  5122.6  425.57
  5249.8  431.16  5292.3  432.36  5348.8  435.46  5405.4   439.8  5447.8  441.63
#Mann= 5 ,-1 , 0
  4599.3     .05       0  4898.9     .12       0  4992.3     .07       0
  4998.3     .12       0  5060.4     .05       0
Bank Sta=4898.9,5037.7
XS Rating Curve= 0 ,0
Exp/Cntr=0.3,0.1

Type RM Length L Ch R = 1 ,16541   ,439,439,439
BEGIN DESCRIPTION:
UNT 022 IN UKCR 30.0
END DESCRIPTION:
XS GIS Cut Line= 3
      3589099.63     10598660.21      3588699.61     10598360.19
      3588199.65      10598210.2
#Sta/Elev= 30
  4496.9  434.14  4583.4  431.94  4604.2  430.41  4760.5  423.77  4852.3  421.93
  4868.8  421.35  4896.9  420.14  4954.2   419.7  4960.5  417.39  4975.1  416.28
  4983.4  419.35  4989.6  411.68  4990.8  411.38  4993.6  410.88  4996.8  411.38
  5004.5  411.41  5007.4  411.42  5013.5  418.83  5059.6  421.58  5079.6  421.46
  5106.6  422.36  5143.1  424.35  5156.1  424.56    5164  423.69    5184   425.2
  5189.2  426.32  5227.5  428.67  5247.5  428.54    5365  433.47  5518.9  442.57
#Mann= 6 ,-1 , 0
  4496.9     .05       0  4852.3     .12       0  4990.8     .07       0
  4996.8     .12       0  5004.5     .07       0  5106.6     .05       0
Bank Sta=4868.8,5079.6
XS Rating Curve= 0 ,0
Exp/Cntr=0.3,0.1

Type RM Length L Ch R = 1 ,16102   ,491,491,491
BEGIN DESCRIPTION:
UNT 022 IN UKCR 29.0
END DESCRIPTION:
XS GIS Cut Line= 3
      3589349.63     10598510.21      3589049.61     10598210.19
      3588349.62      10597860.2
#Sta/Elev= 30
  4579.3   435.7  4664.2  433.97  4833.9  428.33  4918.7     425  4943.4  421.75
    4947  421.33  4961.2  419.59  4975.3  419.09  4986.4  410.56  4989.2  410.06
  4992.4  410.56  5006.4  411.11    5012   415.1  5017.6  417.32    5026  416.78
  5045.6  417.55  5084.6  418.55  5129.4  417.68  5196.5  417.76    5235  418.82
  5257.9  419.77  5316.6  422.26    5325  423.17    5339  422.93  5428.4  427.37
  5487.1  429.29  5598.9  435.35  5688.4  438.43  5719.1  437.93  5786.2  442.03
#Mann= 6 ,-1 , 0
  4579.3     .05       0  4943.4     .16       0  4986.4     .07       0
  4992.4     .16       0  5045.6     .12       0    5235     .05       0
Bank Sta=4947,5257.9
XS Rating Curve= 0 ,0
Exp/Cntr=0.3,0.1

Type RM Length L Ch R = 1 ,15611   ,265,265,265
BEGIN DESCRIPTION:
UNT 022 IN UKCR 28.0
END DESCRIPTION:
XS GIS Cut Line= 3
       3589349.6     10598310.16      3589099.61     10597810.19
      3588799.58     10597510.16
#Sta/Elev= 30
  4416.3  430.64  4430.2  430.43  4564.4  424.93  4625.9  421.63  4648.3  420.85
  4662.2  421.38  4670.6  420.31  4749.6  418.47  4760.3  417.86    4774  417.59
  4804.8  416.43  4818.8  416.52  4877.5  415.09  4908.2  415.85  4930.6   415.5
  4944.5  416.07  4961.3  414.41  4978.8  414.99  4989.4  414.39  5000.6   409.7
  5003.3   409.2  5006.6   409.7  5017.7  411.26    5046  417.85  5063.6  419.09
  5102.6  420.86    5145  424.02  5229.8  428.46  5357.1  433.43  5399.6     436
#Mann= 6 ,-1 , 0
  4416.3     .05       0  4749.6     .07       0  4760.3     .12       0
  5000.6     .07       0  5006.6     .12       0  5063.6     .05       0
Bank Sta=4774,5046
XS Rating Curve= 0 ,0
Exp/Cntr=0.3,0.1

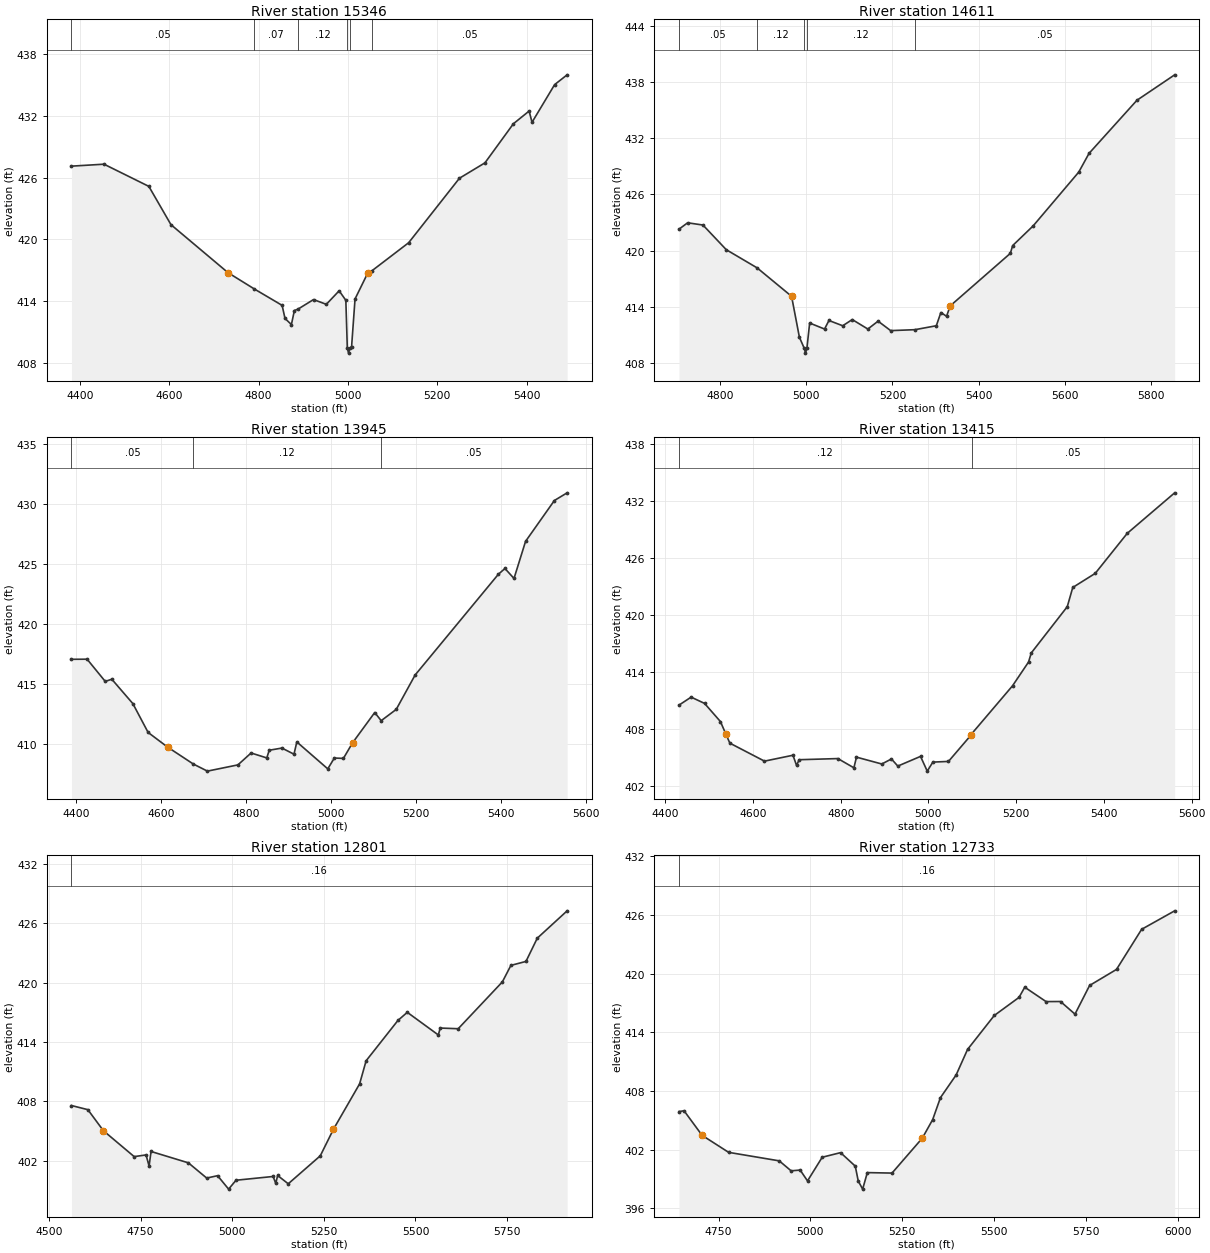
Type RM Length L Ch R = 1 ,15346   ,735,735,735
BEGIN DESCRIPTION:
UNT 022 IN UKCR 27.0
END DESCRIPTION:
XS GIS Cut Line= 3
       3589667.6     10598105.51      3589278.74     10597633.32
      3588899.57     10597310.16
#Sta/Elev= 30
  4380.8   427.1  4453.7  427.29  4554.1  425.14  4603.6  421.43  4731.3  416.78
  4790.6  415.19  4852.5  413.61    4859  412.34  4873.3  411.75    4880  413.11
  4887.9  413.24  4922.8  414.17  4951.5  413.71  4980.2  415.02  4995.2   414.1
  4998.5  409.48  5001.2  408.98  5004.5  409.48  5008.1  409.62  5015.8  414.23
  5043.9  416.71    5053  416.94  5135.9  419.68  5249.6  425.93  5306.7  427.42
  5370.4  431.21  5405.6  432.44  5412.1  431.35  5462.7     435  5490.7  435.95
#Mann= 6 ,-1 , 0
  4380.8     .05       0  4790.6     .07       0  4887.9     .12       0
  4998.5     .07       0  5004.5     .12       0    5053     .05       0
Bank Sta=4731.3,5043.9
XS Rating Curve= 0 ,0
Exp/Cntr=0.3,0.1

Type RM Length L Ch R = 1 ,14611   ,666,666,666
BEGIN DESCRIPTION:
UNT 022 IN UKCR 26.0
END DESCRIPTION:
XS GIS Cut Line= 2
      3590000.98     10597563.88      3588938.49     10597119.44
#Sta/Elev= 30
    4704  422.28  4724.1  422.96  4759.7  422.72  4813.9  420.09  4885.6  418.15
  4965.6  415.12  4983.8  410.75  4995.2  409.56  4997.9  409.06  5001.2  409.56
  5007.6  412.27  5042.2  411.63  5052.4  412.54  5084.4  411.98  5106.6  412.64
  5142.8  411.63  5166.6  412.47  5195.8  411.46  5252.1  411.56  5301.9  411.98
  5312.5  413.39  5325.7  412.99  5334.2   414.1  5473.9   419.7  5479.3  420.53
  5526.9  422.63  5632.9  428.37  5656.7  430.36  5768.1  436.03  5855.7  438.74
#Mann= 5 ,-1 , 0
    4704     .05       0  4885.6     .12       0  4995.2     .07       0
  5001.2     .12       0  5252.1     .05       0
Bank Sta=4965.6,5334.2
XS Rating Curve= 0 ,0
Exp/Cntr=0.3,0.1

Type RM Length L Ch R = 1 ,13945   ,530,530,530
BEGIN DESCRIPTION:
UNT 022 IN UKCR 25.0
END DESCRIPTION:
XS GIS Cut Line= 2
     3590282.004     10597195.37       3589285.7     10596591.66
#Sta/Elev= 30
  4388.7  417.07  4425.5  417.08  4468.2  415.23  4483.7  415.41  4533.2  413.38
  4569.1  410.98    4615  409.76  4675.5  408.35  4708.6  407.76  4780.4  408.28
  4811.4  409.27  4848.3  408.86  4854.1   409.5  4883.9  409.68  4912.3  409.17
    4919  410.19  4991.8  407.95  5007.3  408.85  5028.6  408.82    5050  410.11
  5102.3  412.64  5117.5  411.96  5152.9   412.9  5197.3  415.76  5393.2  424.15
  5408.7  424.63    5430   423.8  5457.2  426.89    5525  430.29    5555  430.93
#Mann= 3 ,-1 , 0
  4388.7     .05       0  4675.5     .12       0  5117.5     .05       0
Bank Sta=4615,5050
XS Rating Curve= 0 ,0
Exp/Cntr=0.3,0.1

Type RM Length L Ch R = 1 ,13415   ,614,614,614
BEGIN DESCRIPTION:
UNT 022 IN UKCR 24.0
END DESCRIPTION:
XS GIS Cut Line= 2
     3590532.181    10596807.994      3589592.95     10596217.73
#Sta/Elev= 30
  4431.4   410.5  4459.1  411.34  4489.7  410.68  4525.9  408.77    4538  407.48
  4547.4   406.5  4626.3  404.61  4691.2  405.23  4699.4  404.16  4705.3  404.76
  4793.6  404.88  4830.1  403.91    4836  405.03  4893.7  404.31  4915.7  404.84
  4930.2  404.09    4982  405.11  4997.3  403.56  5010.1  404.51  5045.7  404.58
  5097.5  407.37  5098.7  407.49  5191.7  412.53  5228.2  415.03  5234.5  415.99
  5316.5  420.85    5329  422.87  5380.2  424.35  5453.2  428.56  5561.3  432.82
#Mann= 2 ,-1 , 0
  4431.4     .12       0  5098.7     .05       0
Bank Sta=4538,5097.5
XS Rating Curve= 0 ,0
Exp/Cntr=0.3,0.1

Type RM Length L Ch R = 1 ,12801   ,68,68,68
BEGIN DESCRIPTION:
UNT 022 IN UKCR 23.0
END DESCRIPTION:
XS GIS Cut Line= 6
     3590646.095    10596610.685      3590589.86     10596572.53
      3590511.74     10596385.03       3590490.9     10596046.49
      3590381.53     10595890.24      3589850.32     10595765.24
#Sta/Elev= 30
  4561.4  407.58  4606.2  407.16  4648.6  405.03  4732.5  402.41    4765  402.58
  4773.2  401.45  4778.6  402.93  4880.4  401.78  4930.4  400.24  4960.1  400.48
  4990.2  399.12  5010.4  400.02  5111.7   400.4  5118.8   399.7    5124   400.5
  5152.9  399.66  5240.3  402.49  5276.1  405.17  5347.6  409.77  5365.4  412.11
  5452.2  416.19  5477.7  417.01  5562.4  414.72  5567.6  415.42  5616.6  415.35
  5737.1  420.09  5760.4  421.76  5801.5  422.16  5832.3  424.51  5913.8  427.28
#Mann= 1 ,-1 , 0
  4561.4     .16       0
Bank Sta=4648.6,5276.1
XS Rating Curve= 0 ,0
Exp/Cntr=0.3,0.1

Type RM Length L Ch R = 1 ,12733   ,468,468,468
BEGIN DESCRIPTION:
Mapping XS ba90bb4a
END DESCRIPTION:
XS GIS Cut Line= 6
     3590652.362    10596546.485      3590589.86     10596296.49
      3590579.71     10596079.04      3590543.25     10595952.74
      3590456.01     10595862.89      3589876.62     10595701.45
#Sta/Elev= 30
  4642.3  405.89  4656.1  405.97  4705.2  403.46  4777.4  401.72  4915.2  400.85
  4947.5  399.83  4972.1  399.91  4992.1   398.8  5032.1  401.22  5082.1  401.69
  5122.1  400.31  5130.2  398.79  5142.2  397.96  5154.9  399.65  5222.1   399.6
  5304.5  403.17  5332.8  405.07  5353.9  407.31  5396.6  409.63  5427.7  412.24
  5500.4  415.71  5567.8  417.56  5583.4   418.6  5641.4  417.13  5680.7  417.14
  5720.1  415.85  5759.9  418.78  5833.1  420.42  5901.5  424.52  5991.4  426.41
#Mann= 1 ,-1 , 0
  4642.3     .16       0
Bank Sta=4705.2,5304.5
XS Rating Curve= 0 ,0
Exp/Cntr=0.3,0.1

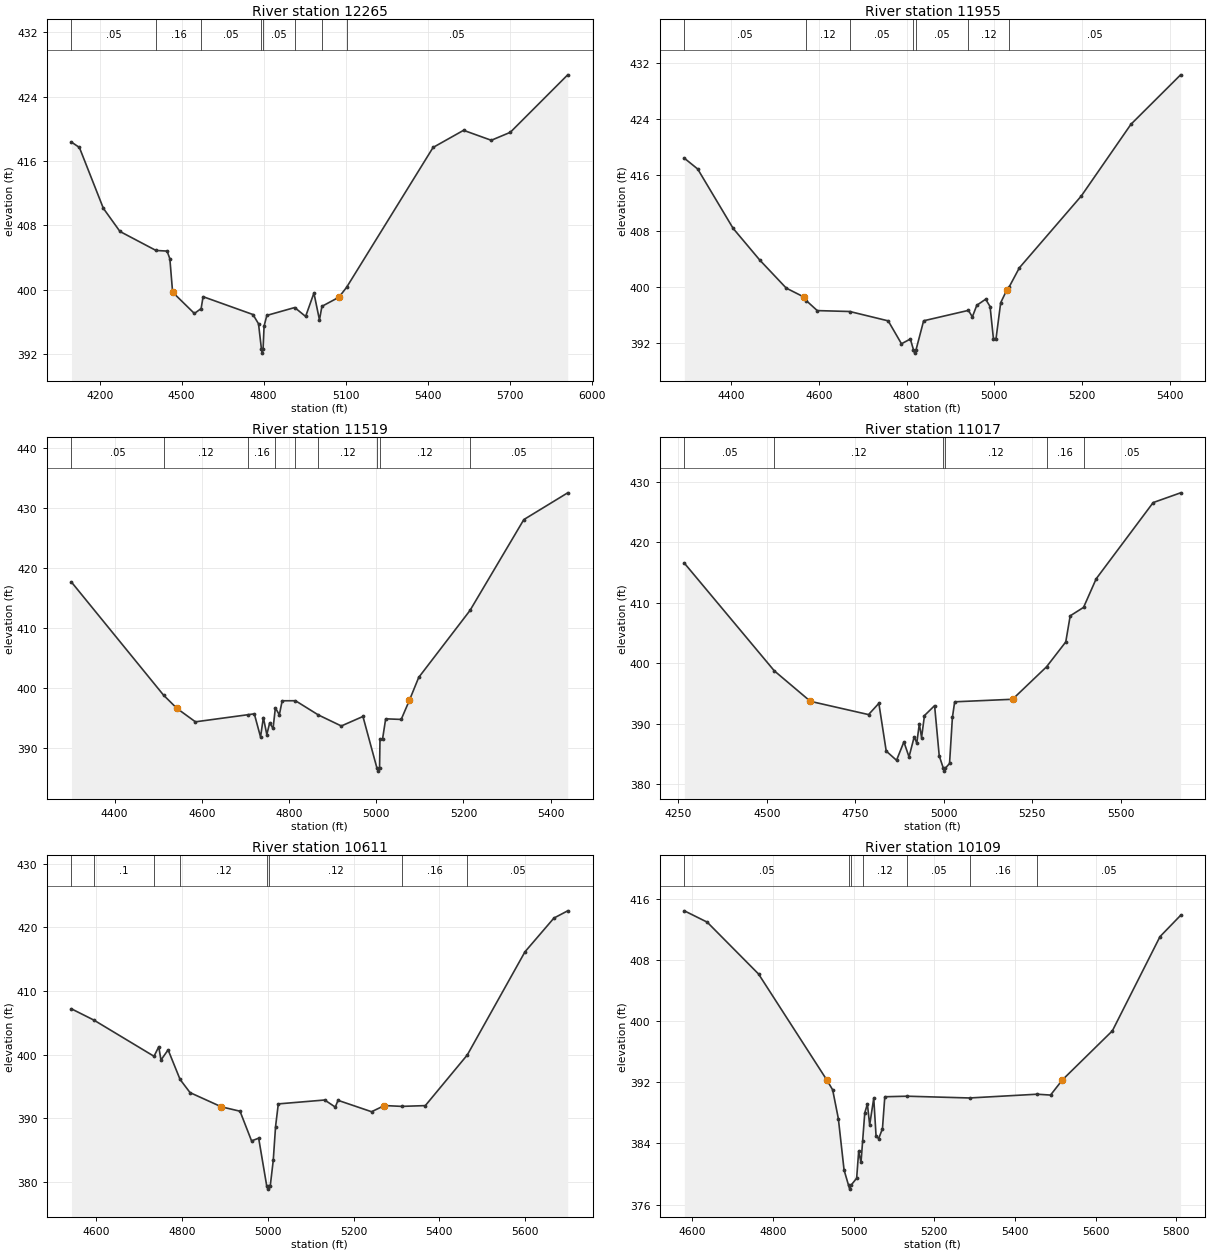
Type RM Length L Ch R = 1 ,12265   ,310,310,310
BEGIN DESCRIPTION:
UNT 022 IN UKCR 22.0
END DESCRIPTION:
XS GIS Cut Line= 2
      3591674.58     10595959.71      3589883.78     10595661.24
#Sta/Elev= 30
    4097  418.36  4125.9   417.7  4213.6  410.13  4274.4  407.25  4406.1  404.89
  4446.7  404.81  4456.9  403.86    4467   399.7  4546.7  397.05  4571.3  397.66
  4578.5  399.14    4761  396.92  4781.3  395.77    4792  392.62  4794.8  392.12
    4798  392.62  4801.6  395.47  4811.7  396.81  4913.7  397.79  4953.6  396.68
    4984  399.59  5004.3  396.25  5013.3  397.94  5075.3  399.07  5103.3  400.29
    5420   417.7  5531.5  419.83  5632.9  418.59  5702.4  419.58  5912.5  426.73
#Mann= 8 ,-1 , 0
    4097     .05       0  4406.1     .16       0  4571.3     .05       0
    4792     .07       0    4798     .05       0  4913.7     .16       0
  5013.3     .12       0  5103.3     .05       0
Bank Sta=4467,5075.3
XS Rating Curve= 0 ,0
Exp/Cntr=0.3,0.1

Type RM Length L Ch R = 1 ,11955   ,436,436,436
BEGIN DESCRIPTION:
UNT 022 IN UKCR 21.0
END DESCRIPTION:
XS GIS Cut Line= 3
      3591549.61     10595610.19      3590849.61     10595510.19
      3590549.59     10595210.17
#Sta/Elev= 30
  4293.5  418.41  4323.8  416.87  4404.6  408.37  4465.2  403.84  4525.8  399.81
  4566.2  398.53  4571.2  398.03  4596.5  396.59  4670.6  396.46  4758.2  395.12
  4788.5  391.84  4808.7  392.52  4815.8     391  4818.5   390.5  4821.8     391
    4839  395.13  4941.1  396.62  4950.1  395.69  4960.2  397.35  4980.4  398.22
  4990.5  397.17  4998.1  392.59  5004.1  392.59  5014.7  397.72  5028.9  399.57
  5034.3  400.01  5057.2  402.71  5198.6  413.01  5311.7  423.27  5424.9  430.35
#Mann= 7 ,-1 , 0
  4293.5     .05       0  4571.2     .12       0  4670.6     .05       0
  4815.8     .07       0  4821.8     .05       0  4941.1     .12       0
  5034.3     .05       0
Bank Sta=4566.2,5028.9
XS Rating Curve= 0 ,0
Exp/Cntr=0.3,0.1

Type RM Length L Ch R = 1 ,11519   ,502,502,502
BEGIN DESCRIPTION:
UNT 022 IN UKCR 20.0
END DESCRIPTION:
XS GIS Cut Line= 3
      3591549.59     10595560.17      3590999.61     10595110.19
      3590599.62     10594960.19
#Sta/Elev= 30
  4301.2  417.67  4512.3  398.87  4543.1  396.66  4585.4  394.43  4705.4  395.61
  4720.4  395.76  4734.7  391.91  4741.2  395.14  4749.1   392.3  4755.6  394.25
  4763.4  393.33  4768.7  396.74  4777.8   395.6  4784.3  397.93  4814.8  397.94
  4867.1  395.58  4919.9  393.74  4969.5  395.32  5001.6  386.73  5004.4  386.23
  5007.6  386.73  5008.6  391.58  5014.5  391.58  5021.6  394.93  5057.2  394.83
  5075.9  397.99  5097.3  401.81  5214.9  412.95  5338.4  428.07    5439  432.52
#Mann= 9 ,-1 , 0
  4301.2     .05       0  4512.3     .12       0  4705.4     .16       0
  4768.7     .05       0  4814.8     .16       0  4867.1     .12       0
  5001.6     .07       0  5007.6     .12       0  5214.9     .05       0
Bank Sta=4543.1,5075.9
XS Rating Curve= 0 ,0
Exp/Cntr=0.3,0.1

Type RM Length L Ch R = 1 ,11017   ,406,406,406
BEGIN DESCRIPTION:
UNT 022 IN UKCR 19.0
END DESCRIPTION:
XS GIS Cut Line= 3
      3591697.29     10595472.23      3591202.49     10594822.77
      3590657.35     10594610.97
#Sta/Elev= 30
  4267.5  416.53  4521.4  398.75  4623.4  393.71  4787.6  391.52  4816.7  393.38
  4837.5  385.49  4866.6  383.97  4887.4  387.01  4901.9  384.53  4916.5  387.84
  4923.8  386.82    4931  390.01  4937.3  387.73  4945.5  391.36  4974.1     393
  4987.2   384.7  4998.7  382.68  5001.5  382.18  5004.7  382.68  5016.3  383.44
  5024.4  391.05  5030.8  393.63  5194.3  394.05  5290.2  399.41  5344.5  403.52
    5357  407.83  5394.8  409.23  5430.4  413.95  5591.3  426.54  5668.8  428.15
#Mann= 6 ,-1 , 0
  4267.5     .05       0  4521.4     .12       0  4998.7     .07       0
  5004.7     .12       0  5290.2     .16       0  5394.8     .05       0
Bank Sta=4623.4,5194.3
XS Rating Curve= 0 ,0
Exp/Cntr=0.3,0.1

Type RM Length L Ch R = 1 ,10611   ,502,502,502
BEGIN DESCRIPTION:
UNT 022 IN UKCR 18.0
END DESCRIPTION:
XS GIS Cut Line= 3
       3591949.6     10594810.19      3591499.61     10594710.19
       3590849.6     10594460.19
#Sta/Elev= 30
  4542.1  407.18  4594.5  405.41  4734.6  399.73  4745.7  401.23  4750.8  399.14
  4767.5  400.74  4795.4  396.09  4818.7  394.02  4891.7  391.79  4935.2   391.1
  4962.1  386.44  4978.7  386.86  4997.5  379.36  5000.3  378.86  5003.5  379.36
  5005.7  379.36  5012.7  383.36  5018.1  388.69  5024.5  392.25  5132.7  392.86
  5157.4  391.75  5163.8  392.81    5242  391.02    5272  391.99  5312.4  391.86
  5367.4  391.98  5465.3  399.94  5599.8  416.14  5667.3  421.44  5699.5  422.58
#Mann= 8 ,-1 , 0
  4542.1     .08       0  4594.5      .1       0  4734.6     .08       0
  4795.4     .12       0  4997.5     .07       0  5003.5     .12       0
  5312.4     .16       0  5465.3     .05       0
Bank Sta=4891.7,5272
XS Rating Curve= 0 ,0
Exp/Cntr=0.3,0.1

Type RM Length L Ch R = 1 ,10109   ,362,362,362
BEGIN DESCRIPTION:
UNT 022 IN UKCR 17.0
END DESCRIPTION:
XS GIS Cut Line= 3
      3592099.62      10594710.2      3591799.61     10594410.19
      3591099.61     10594010.19
#Sta/Elev= 30
  4580.1  414.39  4636.7  412.91    4764  406.14  4933.7  392.26  4947.8     391
  4961.9  387.25  4976.1  380.53  4987.2  378.53    4990  378.03  4993.2  378.53
  5007.3  379.45  5012.3  382.97  5018.1  381.51  5022.1  384.29  5027.4  387.97
  5033.9  389.16  5039.6  386.42  5049.7  389.91  5055.5  384.91    5062  384.64
  5071.3  385.93  5077.1   390.1  5132.5  390.17  5287.2  389.94  5454.6  390.43
  5488.1  390.32  5517.6  392.31  5641.4  398.71  5759.5  411.02  5810.6   413.8
#Mann= 7 ,-1 , 0
  4580.1     .05       0  4987.2     .03       0  4993.2     .05       0
  5022.1     .12       0  5132.5     .05       0  5287.2     .16       0
  5454.6     .05       0
Bank Sta=4933.7,5517.6
XS Rating Curve= 0 ,0
Exp/Cntr=0.3,0.1

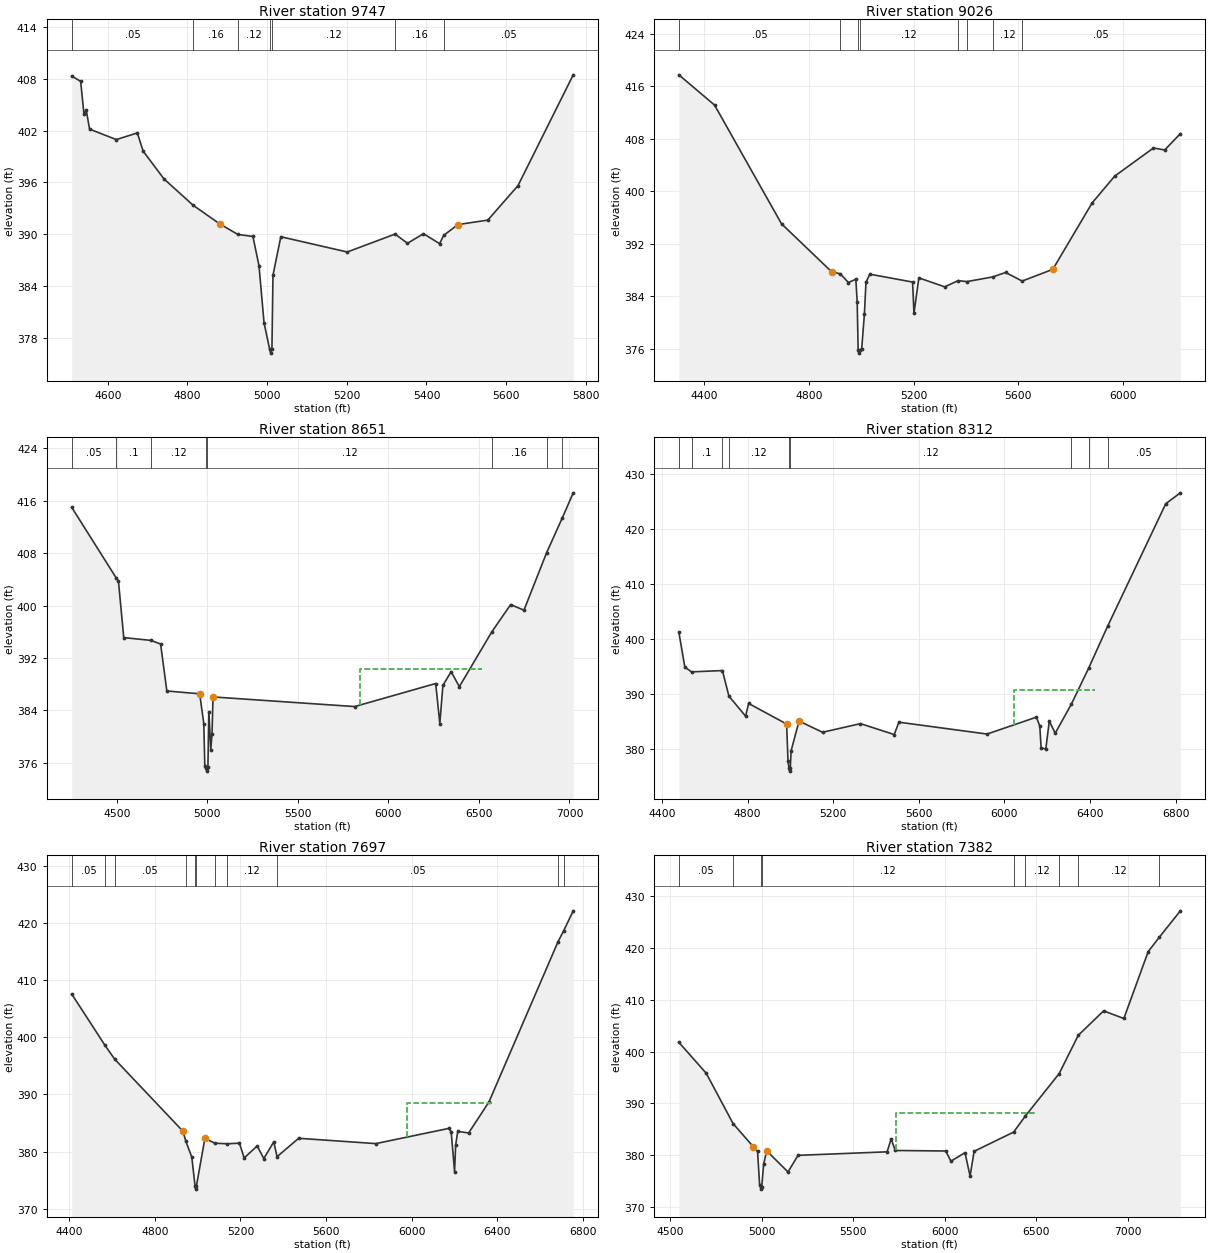
Type RM Length L Ch R = 1 ,9747    ,721,721,721
BEGIN DESCRIPTION:
UNT 022 IN UKCR 16.0
END DESCRIPTION:
XS GIS Cut Line= 3
      3592149.62     10594560.21      3591917.63      10594098.6
      3591199.57     10593910.18
#Sta/Elev= 30
  4509.4  408.34  4531.8  407.72  4540.1  403.93  4545.7  404.42  4554.2  402.18
  4621.3  400.97  4674.1  401.74  4688.5  399.64  4741.1   396.4  4814.2  393.35
  4880.6   391.2  4926.2  389.97  4964.3  389.73  4979.5  386.33  4992.2  379.71
    5006   376.7  5008.7   376.2    5012   376.7  5014.6  385.23  5034.3   389.7
    5201  387.93  5321.2  390.01  5352.2  388.94  5392.5  390.05  5432.9   388.9
  5443.2  389.86  5478.9  391.11    5554  391.63  5629.6  395.62  5768.4  408.48
#Mann= 7 ,-1 , 0
  4509.4     .05       0  4814.2     .16       0  4926.2     .12       0
    5006     .07       0    5012     .12       0  5321.2     .16       0
  5443.2     .05       0
Bank Sta=4880.6,5478.9
XS Rating Curve= 0 ,0
Exp/Cntr=0.3,0.1

Type RM Length L Ch R = 1 ,9026    ,375,375,375
BEGIN DESCRIPTION:
UNT 022 IN UKCR 15.0
END DESCRIPTION:
XS GIS Cut Line= 4
      3592910.71     10593834.72      3592000.97     10593570.82
      3591313.47     10593612.49      3591098.17     10593793.06
#Sta/Elev= 30
  4302.1  417.73  4438.6  413.12  4694.5  395.03  4886.3  387.71  4919.1  387.41
  4950.3  386.08  4978.6  386.58  4983.8  383.16  4987.5  375.82  4990.2  375.32
  4993.5  375.82  5000.9  375.93  5011.3  381.22  5017.4  386.11  5032.1  387.35
  5195.6  386.15  5200.8  381.38  5219.5  386.79  5318.7  385.42  5369.6  386.37
  5403.2  386.22  5502.6  386.94  5551.3  387.61  5614.4   386.3  5731.6  388.09
  5881.9  398.21  5968.1  402.29  6116.4  406.58  6159.3  406.28  6219.1  408.76
#Mann= 8 ,-1 , 0
  4302.1     .05       0  4919.1     .12       0  4987.5     .07       0
  4993.5     .12       0  5369.6     .05       0  5403.2     .07       0
  5502.6     .12       0  5614.4     .05       0
Bank Sta=4886.3,5731.6
XS Rating Curve= 0 ,0
Exp/Cntr=0.3,0.1

Type RM Length L Ch R = 1 ,8651    ,339,339,339
BEGIN DESCRIPTION:
UNT 022 IN UKCR 14.0
END DESCRIPTION:
XS GIS Cut Line= 2
      3592952.39     10593709.73      3590453.46     10592515.79
#Sta/Elev= 30
  4251.5     415    4496  404.27  4509.5   403.7  4538.8  395.11  4686.8  394.69
  4742.2  394.14  4776.7  386.96  4958.1  386.53  4980.8  381.97  4986.4  375.46
  4994.1  375.22  4996.9  374.72  5000.1  375.22  5003.5  375.31    5009  383.76
  5019.3     378  5026.2   380.4  5031.7  386.05  5813.9  384.58  6261.5   388.1
  6284.2  381.98  6301.3  387.82  6346.7   389.9  6392.1  387.62  6570.9  395.97
  6675.3  400.15  6748.9   399.3  6874.2  408.09    6960  413.35    7021  417.22
#Mann= 8 ,-1 , 0
  4251.5     .05       0    4496      .1       0  4686.8     .12       0
  4994.1     .07       0  5000.1     .12       0  6570.9     .16       0
  6874.2     .05       0    6960     .16       0
#XS Ineff= 1 ,-1
 5841.48  6519.6  390.28
Permanent Ineff=
       F
Bank Sta=4958.1,5031.7
XS Rating Curve= 0 ,0
Exp/Cntr=0.3,0.1

Type RM Length L Ch R = 1 ,8312    ,615,615,615
BEGIN DESCRIPTION:
UNT 022 IN UKCR 13.0
END DESCRIPTION:
XS GIS Cut Line= 3
       3592749.6     10593510.18      3592399.61     10593110.19
      3590799.58     10592260.17
#Sta/Elev= 30
  4478.9  401.23  4506.9  394.88    4538  394.02  4682.4  394.26  4712.8  389.63
  4790.7  385.98  4804.9  388.29  4982.4  384.56    4989  377.86  4993.6  376.51
  4996.4  376.01  4999.6  376.51  5003.3  379.68  5040.5  385.09  5150.4  383.06
  5327.5  384.63  5485.2  382.65  5507.1  384.89  5919.1  382.74  6149.6   385.8
  6165.4  384.21  6171.6  380.25  6193.5  380.01  6209.9   385.1  6237.5  382.89
  6312.6  388.14  6394.4  394.75  6482.6  402.32  6754.2  424.54  6822.2  426.51
#Mann= 9 ,-1 , 0
  4478.9     .05       0    4538      .1       0  4682.4     .05       0
  4712.8     .12       0  4993.6     .07       0  4999.6     .12       0
  6312.6     .05       0  6394.4     .16       0  6482.6     .05       0
#XS Ineff= 1 ,-1
 6047.16 6423.86  390.68
Permanent Ineff=
       F
Bank Sta=4982.4,5040.5
XS Rating Curve= 0 ,0
Exp/Cntr=0.3,0.1

Type RM Length L Ch R = 1 ,7697    ,315,315,315
BEGIN DESCRIPTION:
UNT 022 IN UKCR 12.0
END DESCRIPTION:
XS GIS Cut Line= 3
      3593199.62     10592710.19      3592473.19     10592563.88
      3590899.64     10592260.19
#Sta/Elev= 30
  4411.4  407.58    4567  398.59  4611.9  396.19  4931.7  383.54  4944.6   381.8
  4972.5  379.03  4987.8  373.93  4990.5  373.43  4993.8  373.93  5033.7  382.31
  5080.3  381.47  5138.3  381.37    5195  381.48  5217.2   378.9  5278.3  380.99
  5308.9  378.78  5355.6  381.71  5370.9  379.11  5471.8  382.33  5832.4   381.4
  6174.5  384.07  6184.7  383.44  6200.5  376.49  6205.5  381.13  6215.3  383.54
  6266.2  383.26  6361.1  388.69  6683.8  416.73  6710.9   418.7    6755  422.15
#Mann= 11 ,-1 , 0
  4411.4     .05       0    4567     .16       0  4611.9     .05       0
  4944.6     .12       0  4987.8     .07       0  4993.8     .12       0
  5080.3     .05       0  5138.3     .12       0  5370.9     .05       0
  6683.8     .16       0  6710.9     .05       0
#XS Ineff= 1 ,-1
 5977.27 6382.95  388.56
Permanent Ineff=
       F
Bank Sta=4931.7,5033.7
XS Rating Curve= 0 ,0
Exp/Cntr=0.3,0.1

Type RM Length L Ch R = 1 ,7382    ,427,427,427
BEGIN DESCRIPTION:
UNT 022 IN UKCR 11.0
END DESCRIPTION:
XS GIS Cut Line= 3
      3593099.62     10592460.19      3592699.61     10592310.19
       3590647.5      10591244.8
#Sta/Elev= 30
  4548.2  401.79  4697.7  395.81  4844.6  386.07  4954.1  381.64  4978.2   380.7
  4989.3  374.28    4995  373.91  4997.7  373.41    5001  373.91  5011.4  378.23
  5027.9  380.82  5144.4  376.73  5199.2  379.94  5685.8  380.62  5707.9  383.11
  5730.3  380.88  6006.3  380.78  6034.5  378.81  6111.3  380.46    6139  375.94
  6161.2  380.72  6376.7  384.43  6441.2  387.55  6625.6  395.74  6730.2  403.15
  6868.3  407.86  6979.1  406.39  7111.9  419.31  7172.1  422.07  7287.6   427.2
#Mann= 9 ,-1 , 0
  4548.2     .05       0  4844.6     .12       0    4995     .07       0
    5001     .12       0  6376.7     .05       0  6441.2     .12       0
  6625.6     .07       0  6730.2     .12       0  7172.1     .07       0
#XS Ineff= 1 ,-1
 5732.39 6499.43  388.17
Permanent Ineff=
       F
Bank Sta=4954.1,5027.9
XS Rating Curve= 0 ,0
Exp/Cntr=0.3,0.1