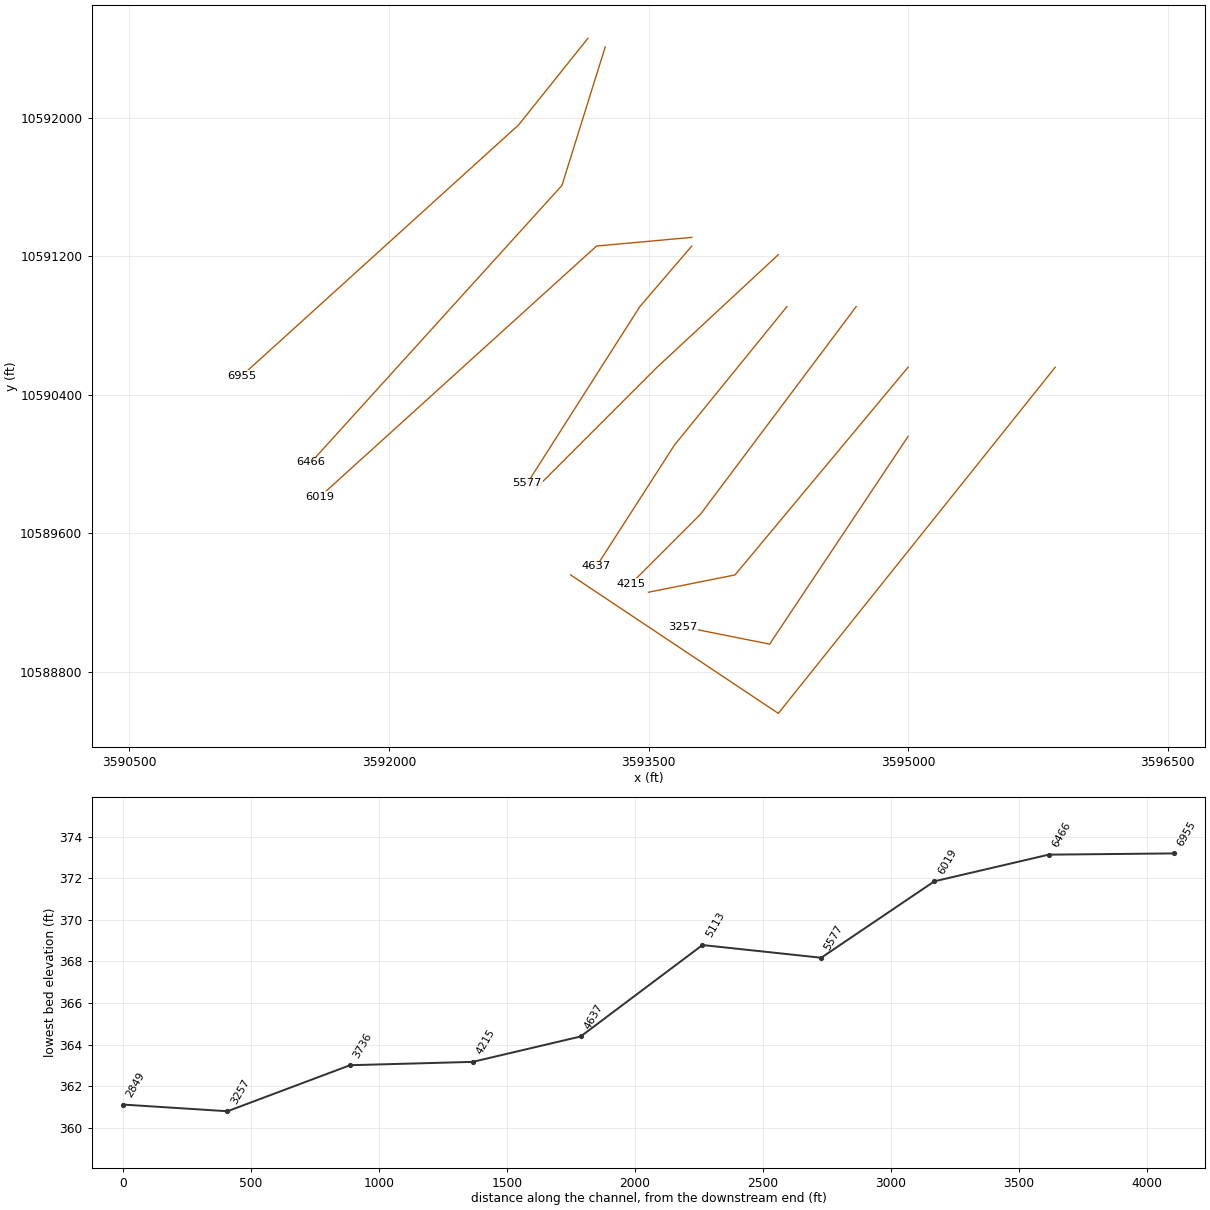
HEC-RAS study UNT 022 IN UKCR.prj: UNT 022 IN UKCR Base Level Engineering

--- UNT 022 IN UKCR.g01 (geometry) --- (continued)

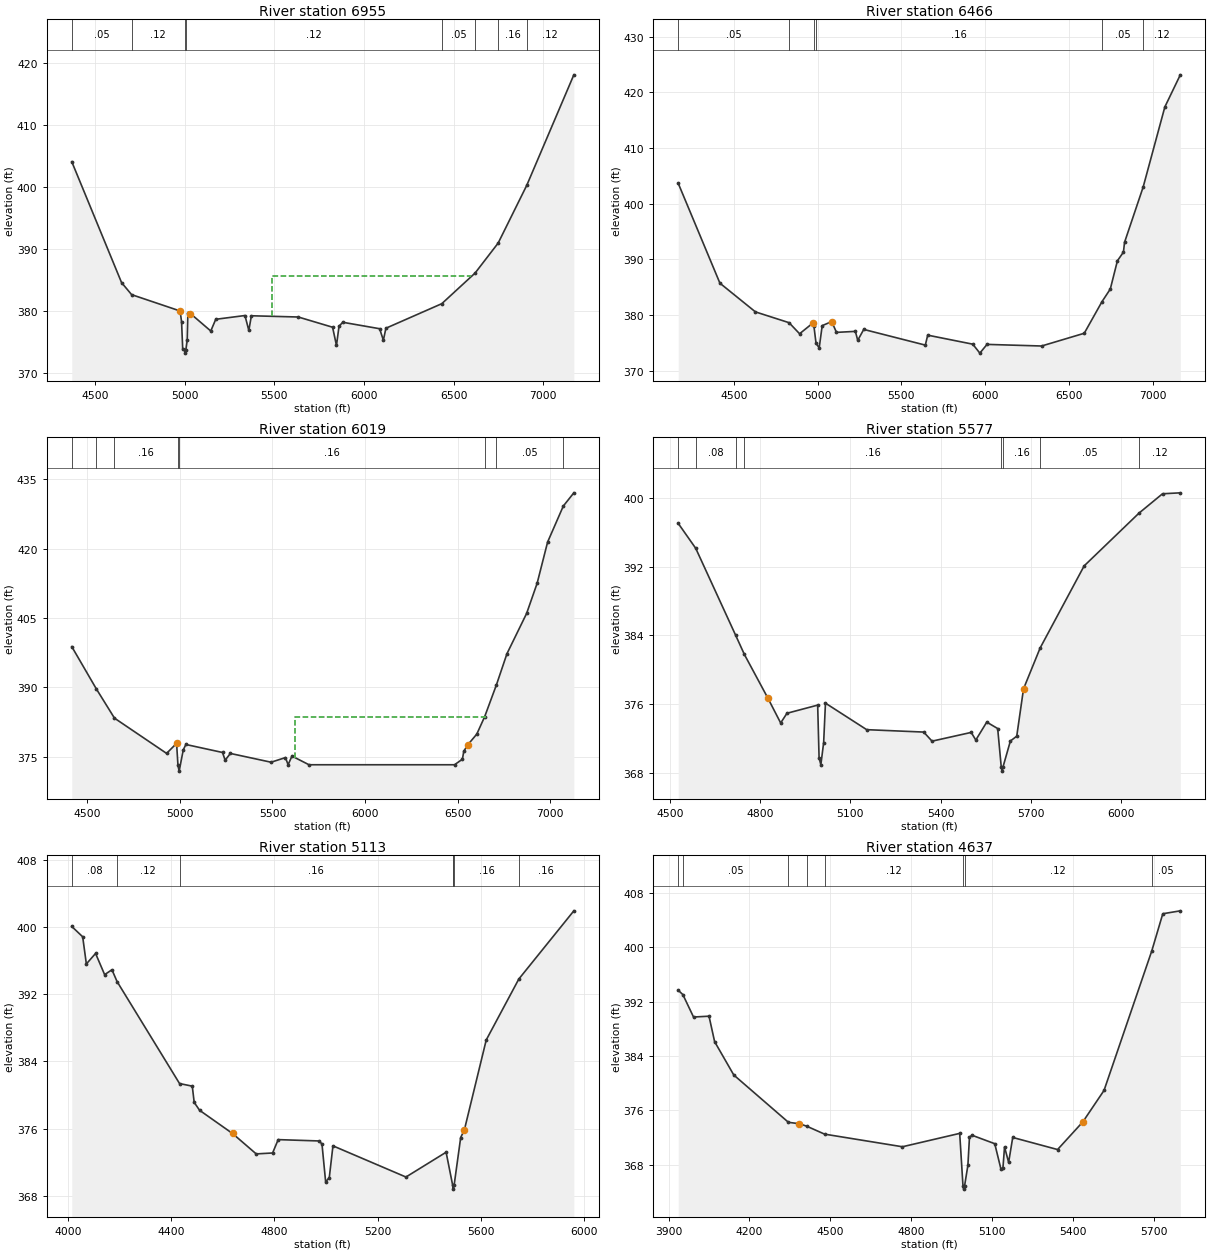
Type RM Length L Ch R = 1 ,6955    ,489,489,489
BEGIN DESCRIPTION:
UNT 022 IN UKCR 10.0
END DESCRIPTION:
XS GIS Cut Line= 3
      3593149.59     10592460.17      3592749.61     10591960.19
      3591149.59     10590510.17
#Sta/Elev= 30
  4370.7  404.09  4648.4  384.57  4704.4  382.63    4975  379.99    4983  378.22
  4989.4  373.79  5000.8  373.69  5003.5  373.19  5006.8  373.69  5014.4  375.26
  5018.1  379.74  5032.3  379.58  5145.8  376.76  5173.5  378.65  5336.4  379.26
    5358  376.85  5372.2  379.22  5633.8  379.02    5825  377.37  5846.7  374.43
  5860.9  377.53  5881.8  378.17  6087.3  377.13  6108.2  375.27  6122.4  377.21
  6433.9  381.17  6619.5  386.11  6748.4  390.96  6907.7  400.27  7170.3  418.11
#Mann= 8 ,-1 , 0
  4370.7     .05       0  4704.4     .12       0  5000.8     .07       0
  5006.8     .12       0  6433.9     .05       0  6619.5     .12       0
  6748.4     .16       0  6907.7     .12       0
#XS Ineff= 1 ,-1
 5485.51 6599.15385.6483
Permanent Ineff=
       F
Bank Sta=4975,5032.3
XS Rating Curve= 0 ,0
Exp/Cntr=0.3,0.1

Type RM Length L Ch R = 1 ,6466    ,447,447,447
BEGIN DESCRIPTION:
UNT 022 IN UKCR 9.0
END DESCRIPTION:
XS GIS Cut Line= 3
      3593249.62     10592410.23      3592999.61     10591610.19
       3591549.6     10590010.17
#Sta/Elev= 30
  4167.5  403.65  4416.4   385.7  4628.5  380.54  4829.3   378.6    4892  376.61
  4974.3  378.61  4977.2  378.07  4990.3  374.88  5009.1  374.08    5027  378.07
  5083.8   378.8  5112.2  376.86    5225  377.04  5239.2  375.43    5275  377.39
  5642.7  374.57  5656.9  376.36  5925.8  374.74  5968.2  373.13    6011   374.7
  6336.8  374.41  6591.5   376.7  6697.6  382.39    6747  384.65  6789.5  389.73
  6825.4  391.28  6832.1  393.05  6943.1  402.97  7072.7  417.38    7165  423.15
#Mann= 6 ,-1 , 0
  4167.5     .05       0  4829.3     .16       0  4977.2     .07       0
  4990.3     .16       0  6697.6     .05       0  6943.1     .12       0
Bank Sta=4974.3,5083.8
XS Rating Curve= 0 ,0
Exp/Cntr=0.3,0.1

Type RM Length L Ch R = 1 ,6019    ,442,442,442
BEGIN DESCRIPTION:
UNT 022 IN UKCR 8.0
END DESCRIPTION:
XS GIS Cut Line= 3
      3593749.57     10591310.18      3593199.61     10591260.19
      3591599.62     10589810.19
#Sta/Elev= 30
  4416.2  398.81  4547.9  389.72  4646.9  383.32  4928.3  375.69  4982.3  377.87
  4989.7  373.08  4996.2  371.85  5018.1  376.42  5032.3  377.62  5230.3  375.89
  5244.5  374.22  5272.9  375.68  5492.5  373.78  5570.3  374.78  5584.5  373.23
  5605.4  375.11  5697.3  373.23  6483.3  373.23  6525.9  374.43  6533.3  376.15
  6554.3  377.52  6603.6  379.87  6646.2  383.65  6709.7  390.54  6766.5  397.28
  6872.6  405.99  6929.3  412.51  6986.1  421.46    7071  429.26  7127.7  432.11
#Mann= 8 ,-1 , 0
  4416.2     .05       0  4547.9     .07       0  4646.9     .16       0
  4989.7     .05       0  4996.2     .16       0  6646.2     .16       0
  6709.7     .05       0    7071     .12       0
#XS Ineff= 1 ,-1
 5622.73 6662.78  383.67
Permanent Ineff=
       F
Bank Sta=4982.3,6554.3
XS Rating Curve= 0 ,0
Exp/Cntr=0.3,0.1

Type RM Length L Ch R = 1 ,5577    ,464,464,464
BEGIN DESCRIPTION:
UNT 022 IN UKCR 7.0
END DESCRIPTION:
XS GIS Cut Line= 3
      3593749.61     10591260.19      3593449.61     10590910.19
       3592799.6      10589890.3
#Sta/Elev= 30
  4527.1  397.04  4585.4  394.13  4717.7  384.04  4747.2  381.77  4825.1   376.7
  4867.9  373.79  4888.8  374.92    4991  375.87  4995.7  369.72  5001.6  368.92
  5010.9  371.51  5016.9   376.1  5154.1  373.01  5343.8  372.73  5371.5  371.67
  5501.8  372.69  5517.1   371.8  5553.5  373.89  5589.9  373.14  5601.7  368.68
  5604.5  368.18  5607.7  368.68  5632.2  371.69  5653.3  372.25  5675.9  377.77
  5731.2  382.53  5877.6  392.09  6060.2  398.24  6138.3  400.49  6197.5   400.6
#Mann= 8 ,-1 , 0
  4527.1     .05       0  4585.4     .08       0  4717.7     .05       0
  4747.2     .16       0  5601.7     .07       0  5607.7     .16       0
  5731.2     .05       0  6060.2     .12       0
Bank Sta=4825.1,5675.9
XS Rating Curve= 0 ,0
Exp/Cntr=0.3,0.1

Type RM Length L Ch R = 1 ,5113    ,476,476,476
BEGIN DESCRIPTION:
UNT 022 IN UKCR 6.0
END DESCRIPTION:
XS GIS Cut Line= 3
      3594249.64     10591210.22      3593549.61     10590560.19
      3592849.64     10589860.21
#Sta/Elev= 30
    4015  400.04  4057.3  398.81  4071.5  395.58  4107.2  396.83  4142.3  394.31
  4170.7  394.89  4190.4  393.49  4432.6  381.35  4481.9  381.04  4489.3  379.11
  4510.2  378.17  4637.8  375.41  4729.6  372.98  4793.1  373.09  4814.7  374.68
  4973.8  374.52  4984.4  374.15  4998.6  369.65  5012.7  370.16  5026.9  373.94
  5309.7  370.23  5465.3  373.18  5490.5  369.29  5493.3  368.79  5496.5  369.29
  5521.8  374.93    5536  375.83  5620.8  386.54  5746.9  393.78  5960.2   401.9
#Mann= 7 ,-1 , 0
    4015     .08       0  4190.4     .12       0  4432.6     .16       0
  5490.5     .05       0  5490.5     .07       0  5496.5     .16       0
  5746.9     .16       0
Bank Sta=4637.8,5536
XS Rating Curve= 0 ,0
Exp/Cntr=0.3,0.1

Type RM Length L Ch R = 1 ,4637    ,422,422,422
BEGIN DESCRIPTION:
UNT 022 IN UKCR 5.0
END DESCRIPTION:
XS GIS Cut Line= 3
      3594299.59     10590910.17      3593649.61     10590110.19
      3593199.62      10589410.2
#Sta/Elev= 30
    3936  393.69  3953.2  393.05  3992.7  389.75  4050.2  389.87    4071  386.12
  4142.1  381.21  4344.9  374.24  4384.2  374.04  4412.1  373.68    4479   372.5
  4767.8  370.64  4980.3  372.61  4992.5   364.9  4995.2   364.4  4998.5   364.9
  5010.7  367.89  5016.6  372.03  5025.9  372.34  5110.4  371.09  5133.2  367.38
  5140.8  367.51  5146.7  370.62  5161.9  368.34  5177.1  372.01  5343.5  370.23
  5437.3  374.31  5515.9  378.94  5692.9  399.47  5733.9  404.96  5798.9  405.39
#Mann= 8 ,-1 , 0
    3936     .08       0  3953.2     .05       0  4344.9     .07       0
  4412.1     .05       0    4479     .12       0  4992.5     .07       0
  4998.5     .12       0  5692.9     .05       0
Bank Sta=4384.2,5437.3
XS Rating Curve= 0 ,0
Exp/Cntr=0.3,0.1

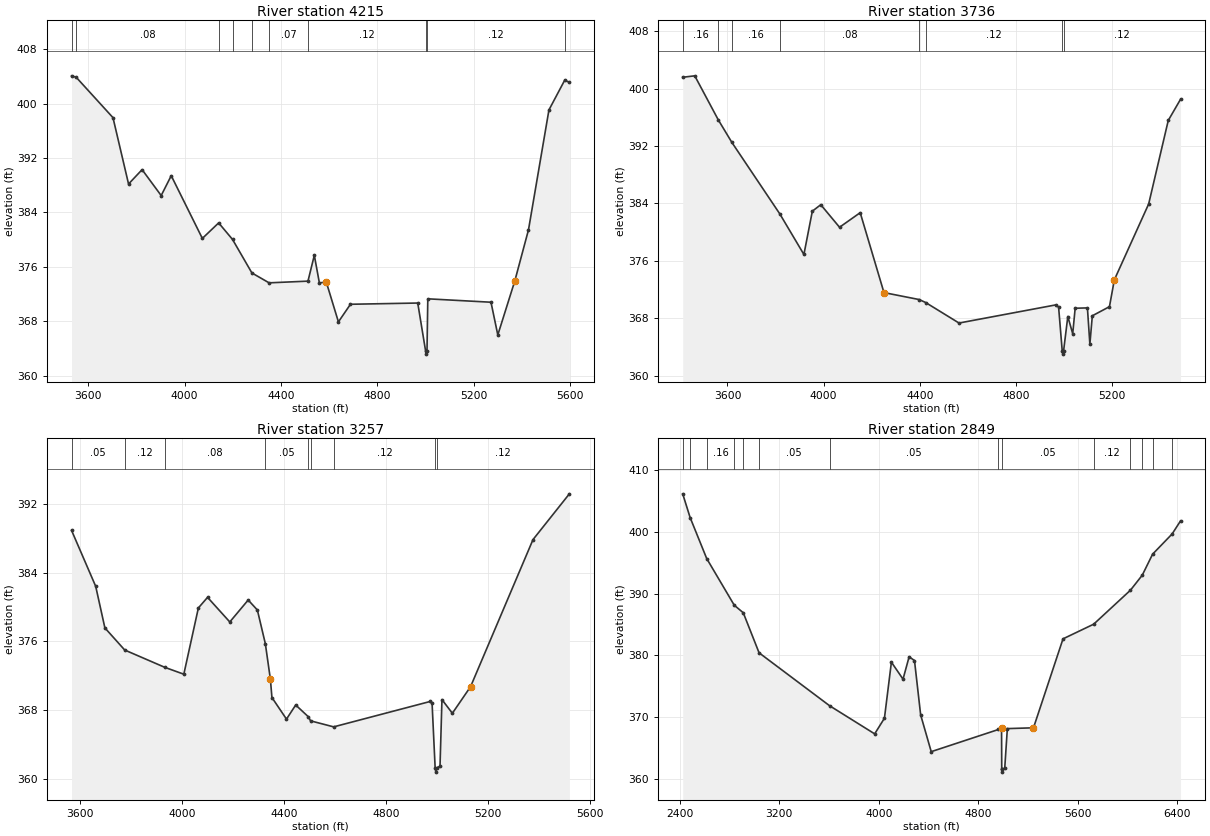
Type RM Length L Ch R = 1 ,4215    ,479,479,479
BEGIN DESCRIPTION:
UNT 022 IN UKCR 4.0
END DESCRIPTION:
XS GIS Cut Line= 3
      3594699.63     10590910.21      3593799.61     10589710.19
      3593399.62      10589310.2
#Sta/Elev= 30
  3531.3  404.09  3550.5  403.88  3703.2  397.94  3767.8  388.19    3824   390.3
  3903.2  386.49  3944.9  389.41    4074  380.19  4141.7  382.47  4199.2  380.04
  4279.7  375.11  4350.9  373.66  4512.3  373.91  4538.6  377.71  4559.5  373.67
  4588.6  373.74  4638.6  367.92  4688.6  370.51  4967.8  370.69  5000.2  363.68
    5003  363.18  5006.2  363.68  5009.5  371.31  5271.7  370.81    5300     366
  5370.7  373.96  5427.3  381.45  5512.2  399.08  5577.3  403.43    5597  403.15
#Mann= 10 ,-1 , 0
  3531.3     .16       0  3550.5     .08       0  4141.7     .05       0
  4199.2     .08       0  4279.7     .05       0  4350.9     .07       0
  4512.3     .12       0  5000.2     .07       0  5006.2     .12       0
  5577.3     .05       0
Bank Sta=4588.6,5370.7
XS Rating Curve= 0 ,0
Exp/Cntr=0.3,0.1

Type RM Length L Ch R = 1 ,3736    ,479,479,479
BEGIN DESCRIPTION:
UNT 022 IN UKCR 3.0
END DESCRIPTION:
XS GIS Cut Line= 3
      3594999.64     10590560.22      3593999.61     10589360.19
       3593499.6     10589260.19
#Sta/Elev= 30
  3413.6  401.58  3463.8  401.78    3562  395.63  3618.4   392.5  3817.8  382.55
  3918.1   376.9  3953.2  382.93  3988.3  383.83  4066.4  380.69  4152.4  382.72
  4251.3  371.59    4398  370.62  4424.7  370.21  4563.7  367.35  4968.5  369.89
  4978.2  369.55  4993.1  363.52  4995.8  363.02  4999.1  363.52  5016.5  368.26
  5036.9  365.86  5047.1  369.41  5098.1  369.46  5108.3  364.41  5118.5  368.36
  5189.8  369.63  5210.2  373.37    5353  383.93  5434.6  395.57  5485.6  398.51
#Mann= 8 ,-1 , 0
  3413.6     .16       0    3562     .05       0  3618.4     .16       0
  3817.8     .08       0    4398     .07       0  4424.7     .12       0
  4993.1     .07       0  4999.1     .12       0
Bank Sta=4251.3,5210.2
XS Rating Curve= 0 ,0
Exp/Cntr=0.3,0.1

Type RM Length L Ch R = 1 ,3257    ,408,408,408
BEGIN DESCRIPTION:
UNT 022 IN UKCR 2.0
END DESCRIPTION:
XS GIS Cut Line= 3
      3594999.62     10590160.21      3594199.61     10588960.19
      3593699.65     10589060.18
#Sta/Elev= 30
  3567.6   388.9  3662.3   382.4  3698.3  377.57    3776     375  3933.8  372.98
  4007.8  372.19  4064.9  379.89  4100.9  381.12  4188.1  378.26  4260.2  380.81
  4296.2  379.65  4327.5  375.73  4347.3   371.6  4353.3  369.48  4410.4  366.97
  4446.5  368.61  4495.9  367.25  4504.7  366.77  4595.4  366.07  4973.8  369.02
  4981.3  368.81  4993.3  361.31  4996.1  360.81  4999.3  361.31  5012.4  361.48
    5020  369.24  5060.8  367.65  5132.2  370.74    5377  387.83  5519.7  393.15
#Mann= 9 ,-1 , 0
  3567.6     .05       0    3776     .12       0  3933.8     .08       0
  4327.5     .05       0  4495.9     .12       0  4504.7     .07       0
  4595.4     .12       0  4993.3     .07       0  4999.3     .12       0
Bank Sta=4347.3,5132.2
XS Rating Curve= 0 ,0
Exp/Cntr=0.3,0.1

Type RM Length L Ch R = 1 ,2849    ,0,0,0
BEGIN DESCRIPTION:
UNT 022 IN UKCR 1.0
END DESCRIPTION:
XS GIS Cut Line= 3
       3595849.6     10590560.18      3594249.61     10588560.19
      3593049.57     10589360.21
#Sta/Elev= 30
  2422.9  406.15  2482.5  402.32    2616  395.68  2837.6  388.13    2910  386.91
  3037.2  380.43  3603.5  371.88  3966.8  367.32  4045.3  369.85  4101.3  378.92
  4194.8  376.17  4243.8  379.79    4287  379.18  4336.6  370.38  4421.5  364.44
  4962.5  368.03  4987.1  368.22  4988.6  361.63  4991.4  361.13  4994.6  361.63
  5012.7  361.75  5033.7  368.17    5244   368.3  5481.4  382.69  5727.8  385.06
  6023.7  390.56  6118.8  392.99  6201.9  396.39  6358.9  399.66  6426.4  401.77
#Mann= 14 ,-1 , 0
  2422.9     .08       0  2482.5     .08       0    2616     .16       0
  2837.6     .05       0    2910     .16       0  3037.2     .05       0
  3603.5     .05       0  4962.5     .03       0  4994.6     .05       0
  5727.8     .12       0  6023.7     .05       0  6118.8     .08       0
  6201.9      .1       0  6358.9     .05       0
Bank Sta=4987.1,5244
XS Rating Curve= 0 ,0
Exp/Cntr=0.3,0.1

Chan Stop Cuts=-1
Use User Specified Reach Order=0
Composite Channel Slope=5