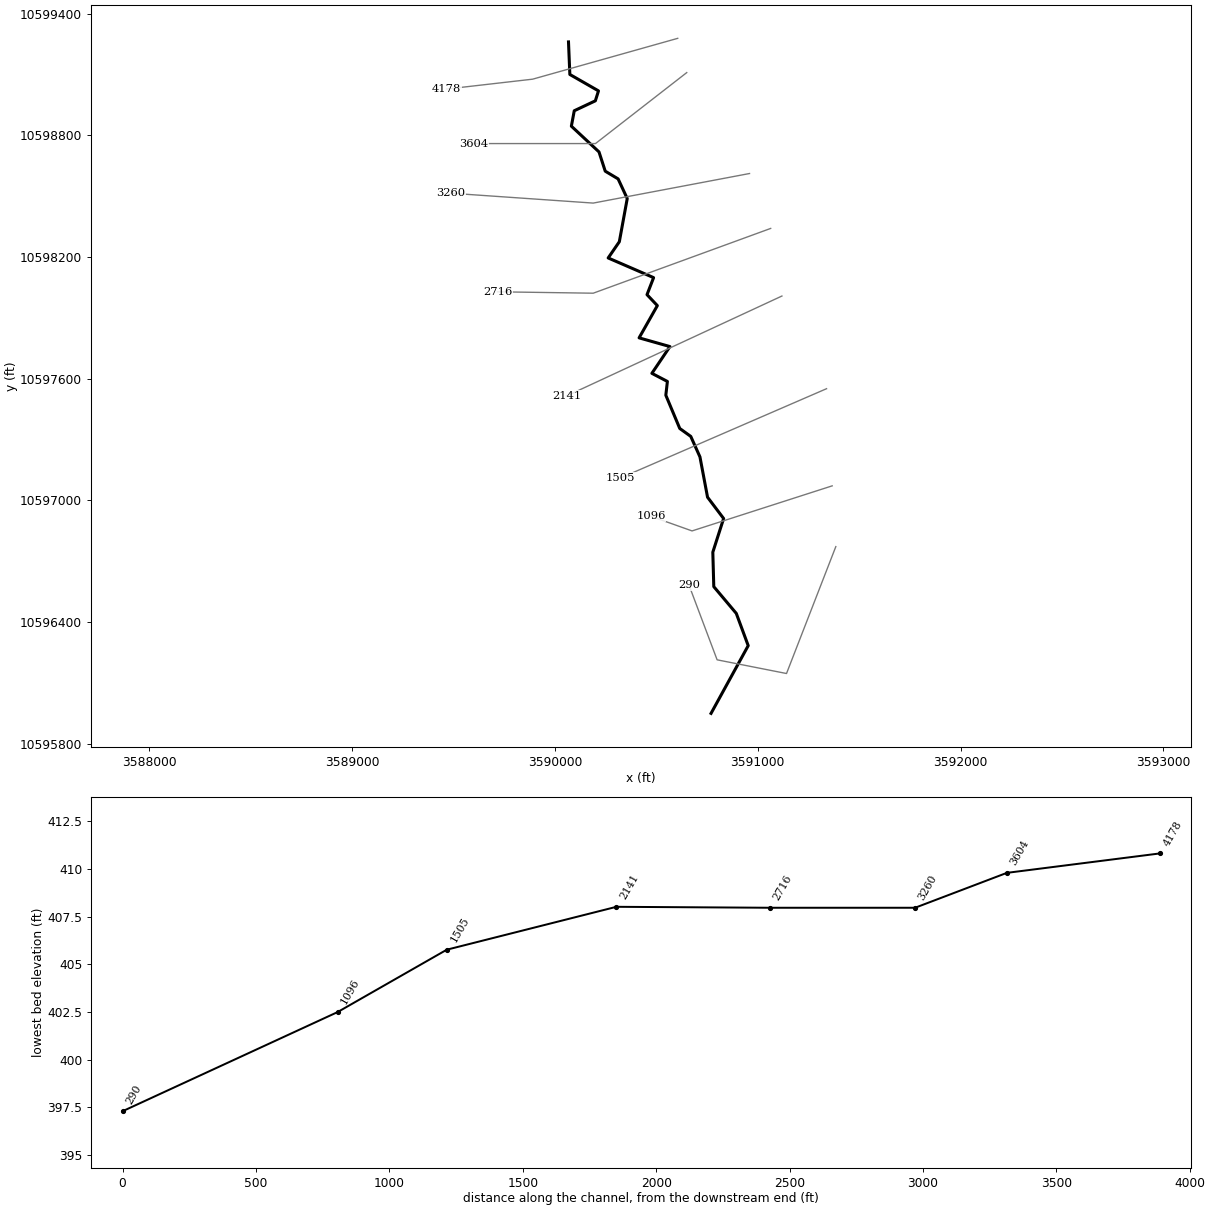
--- UNT 023 IN UKCR.prj (project) ---

Proj Title=UNT 023 IN UKCR Base Level Engineering
Current Plan=p01
Default Exp/Contr=0.3,0.1
English Units
Geom File=g01
Flow File=f01
Plan File=p01
Y Axis Title=Elevation
X Axis Title(PF)=Main Channel Distance
X Axis Title(XS)=Station
BEGIN DESCRIPTION:
UNT 023 IN UKCR
END DESCRIPTION:
DSS Export Rating Curves= 0
DSS Export Rating Curve Sorted= 0
DSS Export Volume Flow Curves= 0
DXF OffsetX= 0
DXF OffsetY= 0
DXF ScaleX= 1
DXF ScaleY= 10

--- UNT 023 IN UKCR.p01 (plan) ---

Plan Title=Multiple Run
Short Identifier=Multiple
Geom File=g01
Flow File=f01
Subcritical Flow
K Sum by GR= 0
Std Step Tol= 0.01
Critical Tol= 0.01
Num of Std Step Trials= 20
Max Error Tol= 0.3
Flow Tol Ratio= 0.001
Split Flow NTrial= 30
Split Flow Tol= 0.02
Split Flow Ratio= 0.02
Log Output Level= 0
Friction Slope Method= 1
Unsteady Friction Slope Method= 2
Unsteady Bridges Friction Slope Method= 1
Parabolic Critical Depth
Global Vel Dist=  1 , 1 , 1
Global Log Level= 0
CheckData=True
Encroach Param= -1, 0, 0, 0
BEGIN DESCRIPTION:
Multiple Run
END DESCRIPTION:

--- UNT 023 IN UKCR.f01 (steady flow) ---

Flow Title=Multiple
Number of Profiles=7
Profile Names=10-year,25-year,50-year,1pct_min,100-year,1pct_plu,500-year
River Rch & RM= UNT 023 IN UKCR,Reach-1,4178
     995    1352    1643    1457    1970    2664    2823
Boundary for River Rch & Prof#=UNT 023 IN UKCR,Reach-1,1
Up Type=0
Dn Type=3
Dn Slope=0.005
Boundary for River Rch & Prof#=UNT 023 IN UKCR,Reach-1,2
Up Type=0
Dn Type=3
Dn Slope=0.005
Boundary for River Rch & Prof#=UNT 023 IN UKCR,Reach-1,3
Up Type=0
Dn Type=3
Dn Slope=0.005
Boundary for River Rch & Prof#=UNT 023 IN UKCR,Reach-1,4
Up Type=0
Dn Type=3
Dn Slope=0.005
Boundary for River Rch & Prof#=UNT 023 IN UKCR,Reach-1,5
Up Type=0
Dn Type=3
Dn Slope=0.005
Boundary for River Rch & Prof#=UNT 023 IN UKCR,Reach-1,6
Up Type=0
Dn Type=3
Dn Slope=0.005
Boundary for River Rch & Prof#=UNT 023 IN UKCR,Reach-1,7
Up Type=0
Dn Type=3
Dn Slope=0.005

--- UNT 023 IN UKCR.g01 (geometry) ---

Geom Title=Existing Conditions

River Reach=UNT 023 IN UKCR,Reach-1
Reach XY= 30
      3590066.58     10599261.49      3590073.25     10599101.00
      3590214.50     10599020.00      3590199.00     10598971.00
      3590095.00     10598922.00      3590080.75     10598846.00
      3590217.00     10598719.00      3590247.75     10598624.00
      3590311.25     10598586.00      3590356.25     10598489.00
      3590317.25     10598276.00      3590262.25     10598196.00
      3590486.25     10598099.00      3590453.75     10598015.00
      3590504.75     10597961.00      3590414.75     10597802.00
      3590566.75     10597759.00      3590477.75     10597627.00
      3590554.25     10597587.00      3590546.50     10597519.00
      3590615.25     10597355.00      3590669.50     10597316.00
      3590714.75     10597215.00      3590752.25     10597016.00
      3590831.50     10596911.00      3590778.25     10596745.00
      3590783.00     10596575.00      3590894.00     10596443.00
      3590952.75     10596284.00      3590769.50     10595950.00

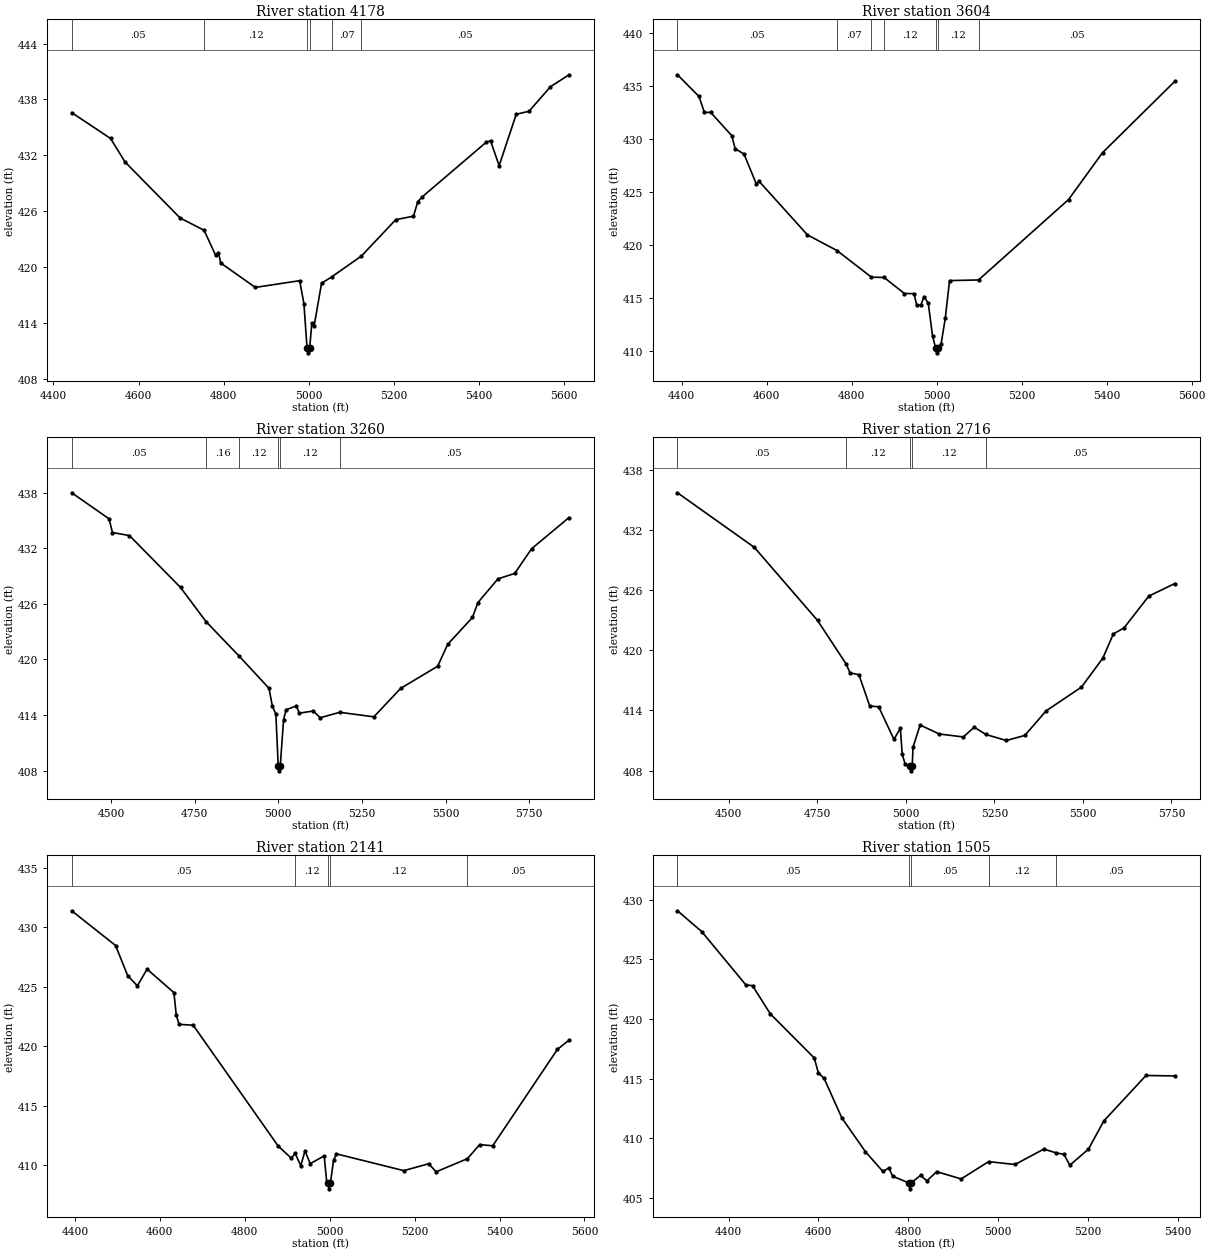
Type RM Length L Ch R = 1,4178,574,574,574
BEGIN DESCRIPTION:
UNT 023 IN UKCR 3.0
END DESCRIPTION:
XS GIS Cut Line= 3
      3590605.15     10599279.16      3589889.85     10599077.77
      3589466.24     10599029.15
#Sta/Elev= 30
  4442.9  436.59  4534.2  433.82  4568.2  431.30  4698.0  425.28  4754.2  423.97
  4781.1  421.30  4788.0  421.58  4793.2  420.46  4874.6  417.84  4978.9  418.56
  4988.9  416.11  4996.3  411.32  4999.0  410.82  5002.3  411.32  5007.7  414.04
  5012.9  413.69  5030.4  418.29  5054.0  418.96  5124.2  421.21  5205.0  425.11
  5246.6  425.48  5256.7  427.04  5266.8  427.54  5417.8  433.42  5427.8  433.57
  5448.0  430.90  5488.2  436.41  5518.4  436.74  5568.7  439.37  5612.4  440.65
#Mann=6,-1,0
  4442.9    0.05       0  4754.2    0.12       0  4996.3    0.07       0
  5002.3    0.12       0  5054.0    0.07       0  5124.2    0.05       0
Bank Sta=4996.3,5002.3
Exp/Cntr=0.3,0.1

Type RM Length L Ch R = 1,3604,344,344,344
BEGIN DESCRIPTION:
UNT 023 IN UKCR 2.0
END DESCRIPTION:
XS GIS Cut Line= 3
      3590649.62     10599110.19      3590199.61     10598760.19
      3589599.61     10598760.19
#Sta/Elev= 30
  4390.3  436.05  4441.0  434.00  4453.7  432.49  4468.1  432.51  4517.9  430.31
  4526.0  429.08  4546.9  428.56  4575.8  425.74  4582.1  426.00  4696.2  420.93
  4765.5  419.46  4846.7  416.94  4876.3  416.92  4924.2  415.40  4946.8  415.39
  4953.2  414.30  4962.9  414.30  4970.4  415.11  4980.4  414.48  4990.4  411.40
  4997.4  410.30  5000.1  409.80  5003.4  410.30  5010.4  410.60  5020.4  413.07
  5030.4  416.62  5098.6  416.68  5310.4  424.27  5390.4  428.70  5560.4  435.43
#Mann=7,-1,0
  4390.3    0.05       0  4765.5    0.07       0  4846.7    0.05       0
  4876.3    0.12       0  4997.4    0.07       0  5003.4    0.12       0
  5098.6    0.05       0
Bank Sta=4997.4,5003.4
Exp/Cntr=0.3,0.1

Type RM Length L Ch R = 1,3260,544,544,544
BEGIN DESCRIPTION:
Mapping XS f9bbb2b5
END DESCRIPTION:
XS GIS Cut Line= 3
      3590959.27     10598612.48      3590188.47     10598466.65
      3589487.63     10598515.23
#Sta/Elev= 30
  4382.2  437.99  4493.8  435.18  4504.0  433.70  4554.9  433.37  4707.5  427.77
  4783.8  424.08  4883.7  420.32  4972.1  416.88  4982.3  414.92  4992.5  414.12
  4999.7  408.47  5002.4  407.97  5005.7  408.47  5015.6  413.47  5023.0  414.56
  5053.6  414.98  5062.8  414.20  5104.5  414.43  5125.3  413.70  5183.4  414.29
  5285.5  413.80  5366.0  416.88  5476.3  419.26  5506.4  421.63  5580.5  424.53
  5596.6  426.13  5656.7  428.70  5706.8  429.28  5757.0  431.94  5869.2  435.32
#Mann=6,-1,0
  4382.2    0.05       0  4783.8    0.16       0  4883.7    0.12       0
  4999.7    0.07       0  5005.7    0.12       0  5183.4    0.05       0
Bank Sta=4999.7,5005.7
Exp/Cntr=0.3,0.1

Type RM Length L Ch R = 1,2716,575,575,575
BEGIN DESCRIPTION:
Mapping XS 968c30a5
END DESCRIPTION:
XS GIS Cut Line= 3
      3591063.49     10598341.66      3590188.47     10598022.21
      3589716.23     10598029.15
#Sta/Elev= 30
  4355.6  435.72  4572.6  430.27  4750.9  422.98  4830.9  418.68  4842.6  417.75
  4867.8  417.56  4898.3  414.44  4923.6  414.36  4966.5  411.11  4984.7  412.22
  4990.0  409.63  4998.5  408.61  5012.2  408.47  5015.0  407.97  5018.2  408.47
  5020.5  410.34  5040.4  412.54  5094.3  411.65  5162.6  411.35  5193.2  412.33
  5226.0  411.60  5283.8  411.00  5336.0  411.50  5396.0  413.95  5496.0  416.33
  5556.0  419.20  5586.0  421.64  5616.0  422.23  5686.0  425.41  5759.4  426.66
#Mann=5,-1,0
  4355.6    0.05       0  4830.9    0.12       0  5012.2    0.07       0
  5018.2    0.12       0  5226.0    0.05       0
Bank Sta=5012.2,5018.2
Exp/Cntr=0.3,0.1

Type RM Length L Ch R = 1,2141,636,636,636
BEGIN DESCRIPTION:
Mapping XS 5af878d3
END DESCRIPTION:
XS GIS Cut Line= 2
      3591119.00     10598008.31      3590056.53     10597515.27
#Sta/Elev= 30
  4392.4  431.40  4495.7  428.48  4524.1  425.95  4547.0  425.09  4569.9  426.49
  4633.1  424.52  4638.6  422.64  4645.3  421.85  4678.4  421.78  4878.6  411.62
  4909.9  410.59  4918.4  411.02  4931.9  409.96  4941.8  411.21  4954.0  410.14
  4987.0  410.79  4993.1  408.56  4995.7  408.52  4998.4  408.02  5001.7  408.52
  5009.1  410.42  5016.0  410.96  5174.5  409.55  5233.2  410.13  5250.6  409.45
  5324.5  410.56  5353.2  411.74  5383.9  411.64  5536.4  419.75  5563.7  420.52
#Mann=5,-1,0
  4392.4    0.05       0  4918.4    0.12       0  4995.7    0.07       0
  5001.7    0.12       0  5324.5    0.05       0
Bank Sta=4995.7,5001.7
Exp/Cntr=0.3,0.1

Type RM Length L Ch R = 1,1505,409,409,409
BEGIN DESCRIPTION:
Mapping XS ebce35a2
END DESCRIPTION:
XS GIS Cut Line= 2
      3591339.08     10597551.24      3590323.11     10597110.88
#Sta/Elev= 30
  4286.2  429.07  4340.1  427.33  4438.2  422.87  4453.4  422.79  4492.7  420.44
  4590.8  416.73  4599.7  415.50  4612.6  415.03  4652.1  411.72  4704.5  408.89
  4743.4  407.23  4756.9  407.52  4765.2  406.83  4800.8  406.27  4803.6  405.77
  4806.8  406.27  4827.3  406.90  4841.5  406.44  4863.3  407.21  4917.8  406.60
  4978.9  408.05  5037.7  407.81  5101.8  409.10  5128.9  408.79  5146.6  408.66
  5159.7  407.75  5201.1  409.09  5235.5  411.46  5329.4  415.27  5393.5  415.23
#Mann=5,-1,0
  4286.2    0.05       0  4800.8    0.07       0  4806.8    0.05       0
  4978.9    0.12       0  5128.9    0.05       0
Bank Sta=4800.8,4806.8
Exp/Cntr=0.3,0.1

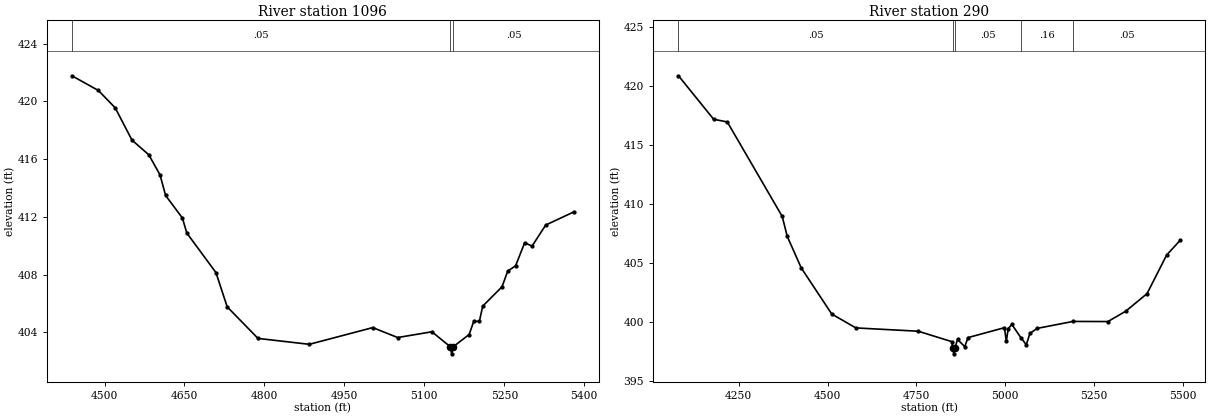
Type RM Length L Ch R = 1,1096,806,806,806
BEGIN DESCRIPTION:
Mapping XS 005c1942
END DESCRIPTION:
XS GIS Cut Line= 3
      3591366.85     10597072.07      3590675.85     10596849.84
      3590472.78     10596922.11
#Sta/Elev= 30
  4438.9  421.78  4488.5  420.76  4520.0  419.56  4551.5  417.32  4583.1  416.30
  4604.1  414.91  4614.6  413.48  4646.1  411.92  4654.3  410.88  4709.1  408.13
  4730.1  405.76  4787.9  403.57  4884.2  403.16  5003.2  404.32  5049.9  403.63
  5114.1  404.03  5148.4  403.00  5151.2  402.50  5154.4  403.00  5184.0  403.84
  5192.6  404.75  5203.2  404.76  5209.5  405.81  5245.7  407.15  5256.3  408.23
  5271.2  408.61  5288.1  410.20  5302.0  409.97  5327.6  411.43  5380.3  412.34
#Mann=3,-1,0
  4438.9    0.05       0  5148.4    0.03       0  5154.4    0.05       0
Bank Sta=5148.4,5154.4
Exp/Cntr=0.3,0.1

Type RM Length L Ch R = 1,290,0,0,0
BEGIN DESCRIPTION:
UNT 023 IN UKCR 1.0
END DESCRIPTION:
XS GIS Cut Line= 4
      3591384.78     10596772.45      3591141.63     10596146.57
      3590799.42     10596214.11      3590661.10     10596581.57
#Sta/Elev= 30
  4080.2  420.90  4179.2  417.21  4217.7  416.98  4372.3  408.96  4386.4  407.27
  4425.9  404.59  4511.7  400.68  4579.6  399.50  4755.2  399.22  4849.2  398.34
  4852.6  397.80  4855.4  397.30  4858.6  397.80  4865.8  398.52  4886.2  397.91
  4895.4  398.68  4998.0  399.52  5003.1  398.35  5008.5  399.43  5018.7  399.80
  5044.7  398.65  5059.5  398.07  5069.7  399.04  5090.1  399.46  5190.9  400.05
  5289.2  400.04  5339.0  400.91  5399.4  402.41  5454.5  405.68  5493.1  406.95
#Mann=5,-1,0
  4080.2    0.05       0  4852.6    0.03       0  4858.6    0.05       0
  5044.7    0.16       0  5190.9    0.05       0
Bank Sta=4852.6,4858.6
Exp/Cntr=0.3,0.1

Chan Stop Cuts=-1