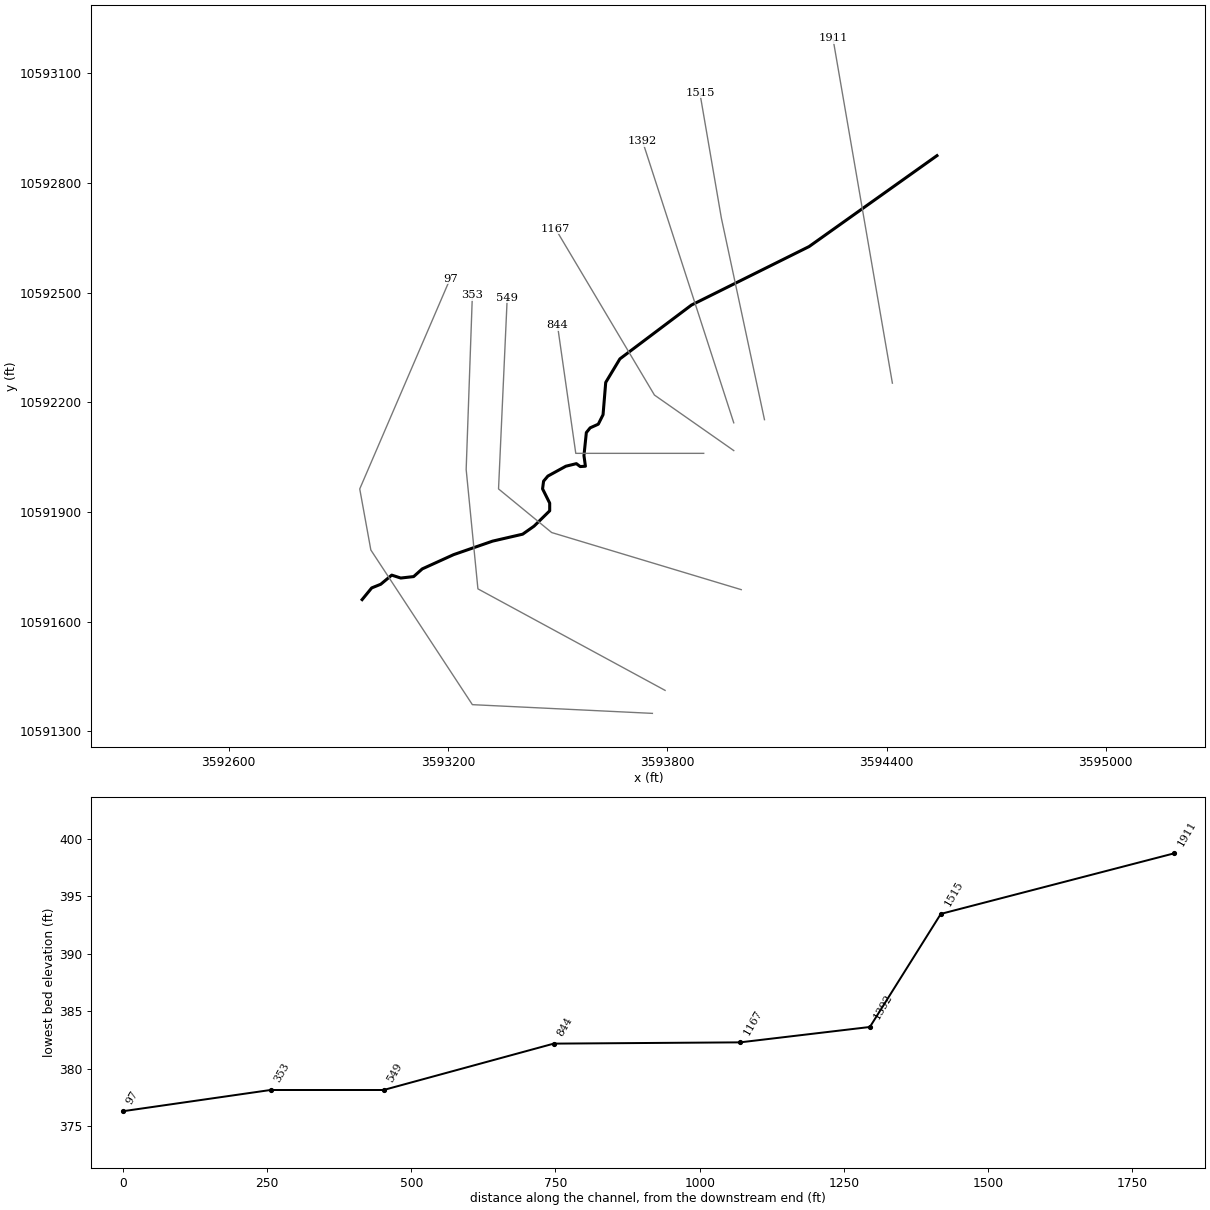
--- UNT 025 IN UKCR.prj (project) ---

Proj Title=UNT 025 IN UKCR Base Level Engineering
Current Plan=p01
Default Exp/Contr=0.3,0.1
English Units
Geom File=g01
Flow File=f01
Plan File=p01
Y Axis Title=Elevation
X Axis Title(PF)=Main Channel Distance
X Axis Title(XS)=Station
BEGIN DESCRIPTION:
UNT 025 IN UKCR
END DESCRIPTION:
DSS Export Rating Curves= 0
DSS Export Rating Curve Sorted= 0
DSS Export Volume Flow Curves= 0
DXF OffsetX= 0
DXF OffsetY= 0
DXF ScaleX= 1
DXF ScaleY= 10

--- UNT 025 IN UKCR.p01 (plan) ---

Plan Title=Multiple Run
Short Identifier=Multiple
Geom File=g01
Flow File=f01
Subcritical Flow
K Sum by GR= 0
Std Step Tol= 0.01
Critical Tol= 0.01
Num of Std Step Trials= 20
Max Error Tol= 0.3
Flow Tol Ratio= 0.001
Split Flow NTrial= 30
Split Flow Tol= 0.02
Split Flow Ratio= 0.02
Log Output Level= 0
Friction Slope Method= 1
Unsteady Friction Slope Method= 2
Unsteady Bridges Friction Slope Method= 1
Parabolic Critical Depth
Global Vel Dist=  1 , 1 , 1
Global Log Level= 0
CheckData=True
Encroach Param= -1, 0, 0, 0
BEGIN DESCRIPTION:
Multiple Run
END DESCRIPTION:

--- UNT 025 IN UKCR.f01 (steady flow) ---

Flow Title=Multiple
Program Version=4.10
Number of Profiles= 7
Profile Names=10-year,25-year,50-year,1pct_min,100-year,1pct_plu,500-year
River Rch & RM=UNT 025 IN UKCR,Reach-1         ,1911
     247     309     355     301     407     550     529
Boundary for River Rch & Prof#=UNT 025 IN UKCR,Reach-1         , 1
Up Type= 0
Dn Type= 3
Dn Slope=0.005
Boundary for River Rch & Prof#=UNT 025 IN UKCR,Reach-1         , 2
Up Type= 0
Dn Type= 3
Dn Slope=0.005
Boundary for River Rch & Prof#=UNT 025 IN UKCR,Reach-1         , 3
Up Type= 0
Dn Type= 3
Dn Slope=0.005
Boundary for River Rch & Prof#=UNT 025 IN UKCR,Reach-1         , 4
Up Type= 0
Dn Type= 3
Dn Slope=0.005
Boundary for River Rch & Prof#=UNT 025 IN UKCR,Reach-1         , 5
Up Type= 0
Dn Type= 3
Dn Slope=0.005
Boundary for River Rch & Prof#=UNT 025 IN UKCR,Reach-1         , 6
Up Type= 0
Dn Type= 3
Dn Slope=0.005
Boundary for River Rch & Prof#=UNT 025 IN UKCR,Reach-1         , 7
Up Type= 0
Dn Type= 3
Dn Slope=0.005
DSS Import GetInterval= 0
DSS Import GetPeak= 0
DSS Import FillOption= 0

--- UNT 025 IN UKCR.g01 (geometry) ---

Geom Title=Existing Conditions
Program Version=4.10

River Reach=UNT 025 IN UKCR ,Reach-1
Reach XY= 30
      3594537.89     10592874.74        3594188.       10592626.
      3593866.25       10592466.      3593670.32     10592318.66
      3593631.53     10592254.21      3593624.25       10592166.
      3593611.25       10592140.        3593589.       10592130.
       3593578.5       10592117.        3593572.       10592054.
        3593576.       10592025.      3593561.75       10592024.
      3593551.25       10592032.       3593522.5       10592025.
      3593473.25       10591998.       3593461.5       10591984.
      3593458.75       10591963.      3593478.25       10591924.
      3593478.25       10591903.       3593435.5       10591861.
      3593404.25       10591839.        3593322.       10591820.
      3593215.25       10591783.       3593129.5       10591744.
        3593106.       10591723.      3593070.75       10591719.
        3593046.       10591727.        3593016.       10591702.
      3592991.25       10591692.        3592965.       10591660.

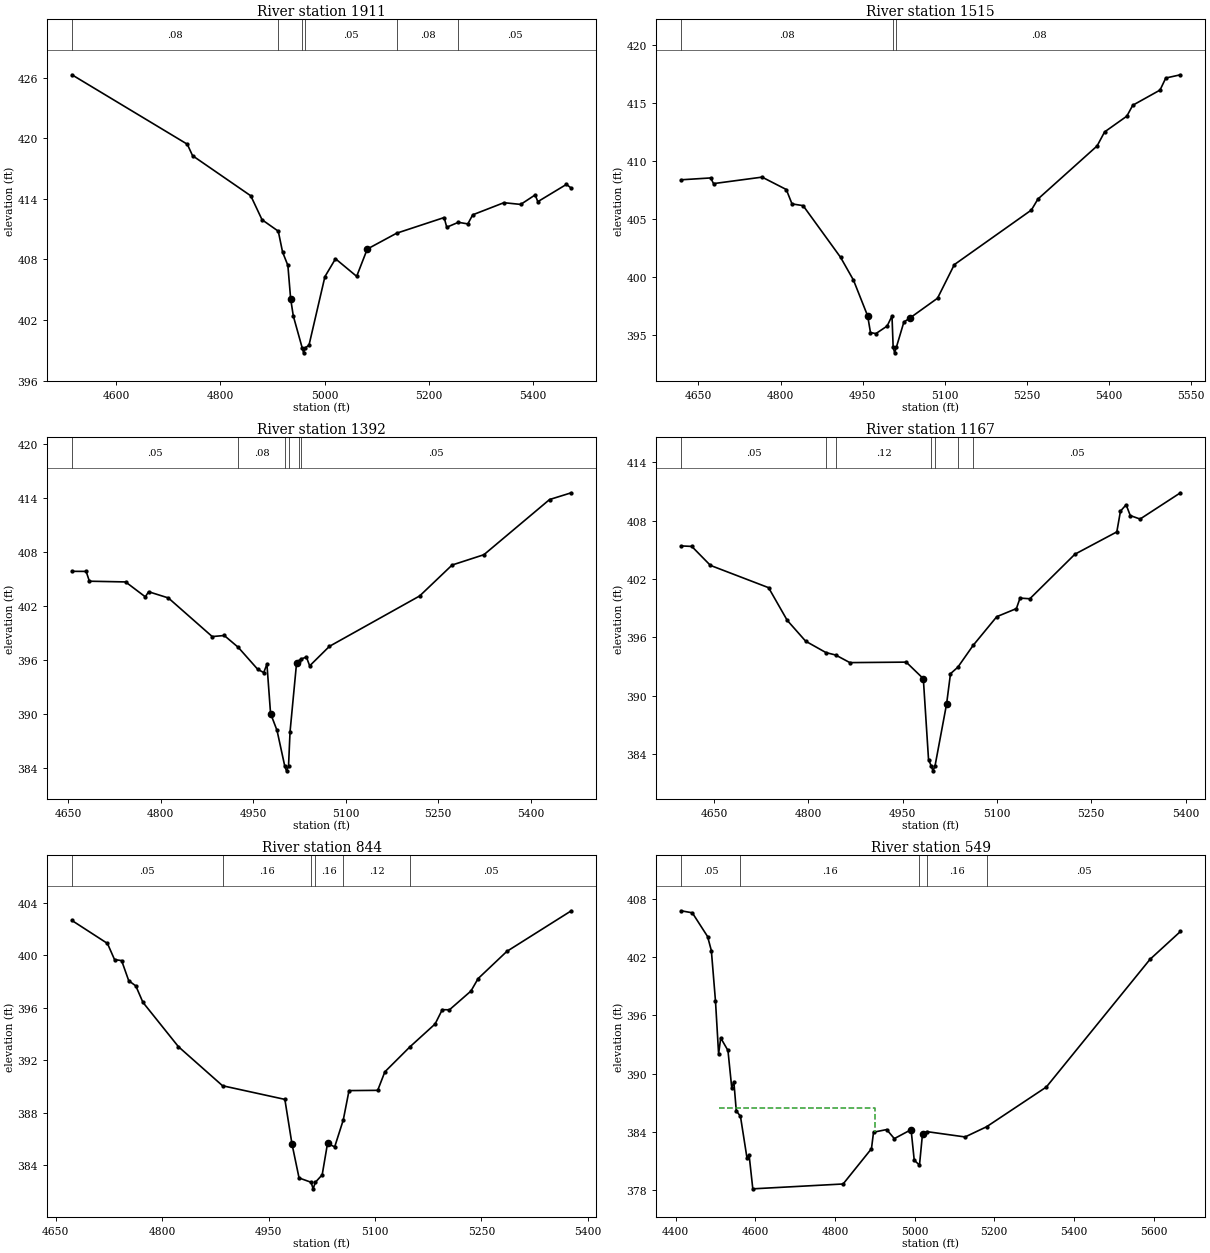
Type RM Length L Ch R = 1 ,1911    ,404,404,404
BEGIN DESCRIPTION:
UNT 025 IN UKCR 5.0
END DESCRIPTION:
XS GIS Cut Line= 2
      3594415.89     10592252.26      3594253.23     10593195.73
#Sta/Elev= 30
  4515.7  426.27  4736.8   419.4    4747  418.26  4858.6  414.29  4880.2  411.92
  4911.3  410.79  4919.5  408.73  4929.7   407.4    4935   404.1  4940.1   402.4
  4957.1  399.25  4959.8  398.75  4963.1  399.25  4970.2  399.51  5000.7  406.29
    5021  408.06  5061.6  406.32  5081.9  409.02  5138.2  410.59  5229.3  412.14
  5234.3  411.18  5256.6  411.67  5274.7  411.51  5284.1  412.41  5343.9  413.61
  5376.1  413.44  5403.8  414.38  5408.9  413.71  5463.7  415.42  5473.1  415.05
#Mann= 6 ,-1 , 0
  4515.7     .08       0  4911.3     .05       0  4957.1     .03       0
  4963.1     .05       0  5138.2     .08       0  5256.6     .05       0
Bank Sta=4935,5081.9
XS Rating Curve= 0 ,0
Exp/Cntr=0.3,0.1

Type RM Length L Ch R = 1 ,1515    ,123,123,123
BEGIN DESCRIPTION:
Mapping XS bd1034ac
END DESCRIPTION:
XS GIS Cut Line= 3
      3594065.92     10592152.34      3593947.88     10592704.38
       3593889.1     10593046.65
#Sta/Elev= 30
  4618.3  408.41  4672.4  408.57  4677.5  408.08  4766.2  408.64  4810.4  407.57
  4820.8  406.33  4841.1  406.18  4909.5  401.72  4933.1  399.75    4959  396.66
  4964.1  395.23    4974  395.14  4994.5  395.79  5003.4  396.66  5005.5  393.98
  5008.2  393.48  5011.5  393.98  5025.1  396.14  5035.4  396.46  5086.5  398.19
  5117.2  401.09  5257.9   405.8  5269.9  406.75  5377.9  411.33  5391.6  412.54
  5432.2   413.9    5443  414.84  5492.8  416.15  5503.3  417.19  5530.1  417.47
#Mann= 3 ,-1 , 0
  4618.3     .08       0  5005.5     .07       0  5011.5     .08       0
Bank Sta=4959,5035.4
XS Rating Curve= 0 ,0
Exp/Cntr=0.3,0.1

Type RM Length L Ch R = 1 ,1392    ,225,225,225
BEGIN DESCRIPTION:
UNT 025 IN UKCR 4.0
END DESCRIPTION:
XS GIS Cut Line= 2
      3593981.87     10592143.74      3593732.31     10592914.13
#Sta/Elev= 30
  4656.2  405.83  4679.2  405.82  4684.5  404.73  4743.2  404.65  4775.2  402.99
  4780.5  403.56  4812.5  402.87  4883.7  398.57  4903.2  398.69  4925.8  397.38
  4957.3  394.94  4967.2  394.56  4972.4   395.5  4978.3  390.01  4988.8  388.12
  5001.4  384.13  5004.2  383.63  5007.4  384.13  5009.9  387.99  5020.4  395.58
    5025  395.89  5027.6  396.06  5036.4   396.3  5041.7  395.31  5073.7  397.48
  5220.1  403.09  5272.7  406.53  5324.3  407.68  5430.8  413.82    5466  414.57
#Mann= 6 ,-1 , 0
  4656.2     .05       0  4925.8     .08       0  5001.4     .07       0
  5007.4     .08       0    5025     .16       0  5027.6     .05       0
Bank Sta=4978.3,5020.4
XS Rating Curve= 0 ,0
Exp/Cntr=0.3,0.1

Type RM Length L Ch R = 1 ,1167    ,323,323,323
BEGIN DESCRIPTION:
UNT 025 IN UKCR 3.0
END DESCRIPTION:
XS GIS Cut Line= 3
      3593981.88     10592067.77      3593764.85     10592219.69
      3593494.18     10592674.42
#Sta/Elev= 30
  4597.7   405.4  4614.7  405.35  4644.3   403.4  4736.8  401.11  4766.4  397.76
  4795.8  395.61  4828.1  394.44  4843.5  394.19  4866.1  393.41  4955.7  393.46
  4982.9  391.76  4991.2  383.45  4995.5  382.79  4998.2  382.29  5001.5  382.79
  5019.9  389.16  5026.1  392.27  5037.8  392.94    5062  395.17  5099.7  398.13
  5130.9  398.96  5136.7  400.04  5152.3  399.97    5224  404.55  5290.6  406.84
  5296.4  408.97  5305.4  409.63    5312  408.52  5327.6  408.16  5391.8  410.86
#Mann= 7 ,-1 , 0
  4597.7     .05       0  4828.1     .16       0  4843.5     .12       0
  4995.5     .07       0  5001.5     .12       0  5037.8     .16       0
    5062     .05       0
Bank Sta=4982.9,5019.9
XS Rating Curve= 0 ,0
Exp/Cntr=0.3,0.1

Type RM Length L Ch R = 1 ,844     ,295,295,295
BEGIN DESCRIPTION:
UNT 025 IN UKCR 2.0
END DESCRIPTION:
XS GIS Cut Line= 3
      3593899.64     10592060.19      3593549.61     10592060.19
      3593499.61     10592410.21
#Sta/Elev= 30
    4673  402.64    4723  400.89    4733  399.66    4743  399.58    4753  398.05
    4763  397.65    4773   396.4    4823  393.02  4885.2  390.04    4973     389
    4983  385.61    4993  383.01    5010  382.68  5012.8  382.18    5016  382.68
  5025.6  383.25  5033.1  385.64  5043.2  385.38  5055.3  387.43  5063.4  389.67
  5103.8  389.69  5113.9   391.1  5149.1     393  5184.7  394.75  5194.8  395.84
  5204.9  395.83  5235.2  397.26  5245.3  398.21  5285.7  400.28  5376.6  403.38
#Mann= 6 ,-1 , 0
    4673     .05       0  4885.2     .16       0    5010     .07       0
    5016     .16       0  5055.3     .12       0  5149.1     .05       0
Bank Sta=4983,5033.1
XS Rating Curve= 0 ,0
Exp/Cntr=0.3,0.1

Type RM Length L Ch R = 1 ,549     ,196,196,196
BEGIN DESCRIPTION:
Mapping XS 58d44000
END DESCRIPTION:
XS GIS Cut Line= 4
      3594002.34     10591687.25      3593483.67      10591843.5
      3593338.27     10591962.86      3593362.08     10592486.61
#Sta/Elev= 30
  4413.4  406.76  4441.6  406.55  4479.9  404.11  4489.4  402.66  4499.8  397.45
  4507.6  392.03  4512.9  393.67  4531.1  392.38  4540.6  388.54  4545.9  389.17
    4552  386.17  4562.5   385.6  4578.9  381.31  4584.1  381.66  4593.5  378.14
  4820.3  378.64  4891.5  382.27  4896.7  383.97  4929.7  384.24  4948.9  383.31
    4991  384.23  4998.9  381.09  5012.1  380.58  5019.7  383.81  5030.4  384.03
  5126.6  383.48  5180.6  384.53  5330.7  388.62    5591  401.76  5667.5  404.63
#Mann= 5 ,-1 , 0
  4413.4     .05       0  4562.5     .16       0  5012.1     .05       0
  5030.4     .16       0  5180.6     .05       0
#XS Ineff= 1 ,-1
 4507.39 4899.55  386.43
Permanent Ineff=
       F
Bank Sta=4991,5019.7
XS Rating Curve= 0 ,0
Exp/Cntr=0.3,0.1

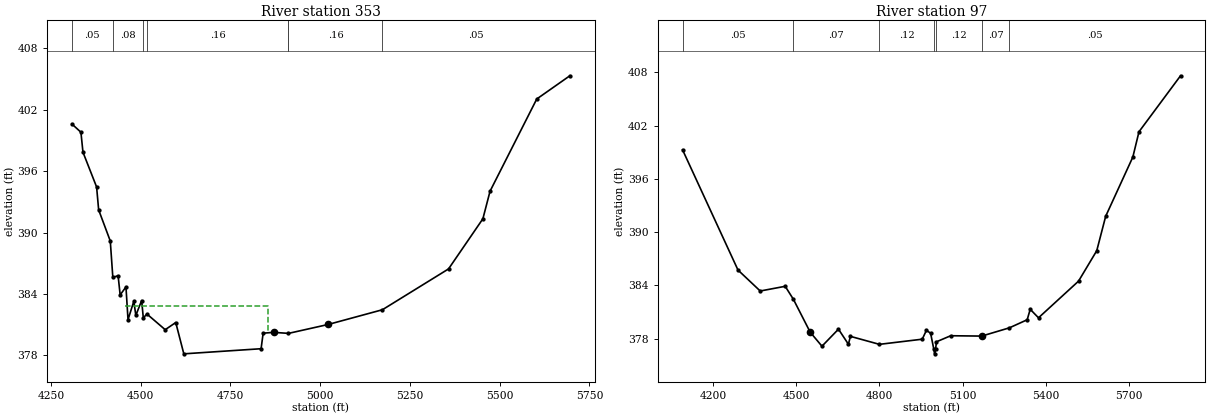
Type RM Length L Ch R = 1 ,353     ,256,256,256
BEGIN DESCRIPTION:
Mapping XS c8c1ff52
END DESCRIPTION:
XS GIS Cut Line= 4
      3593793.97     10591411.66      3593281.85     10591689.42
       3593249.7     10592016.06      3593266.65     10592492.35
#Sta/Elev= 30
  4308.1  400.61  4333.3   399.8    4339  397.85    4377  394.45  4382.7  392.21
  4415.1  389.17  4422.2  385.61  4436.9  385.78  4442.6   383.9  4458.8  384.68
  4464.5  381.48  4480.7  383.28  4486.3   381.9  4502.5  383.35  4507.1  381.66
  4517.3  382.03  4568.1   380.5  4597.5   381.2    4620  378.14  4835.3  378.64
    4841  380.16  4870.5  380.24  4911.6  380.14  5022.1  381.01  5173.3  382.45
  5357.5  386.44  5453.2  391.34  5473.2  394.04  5603.3  403.05  5695.5  405.32
#Mann= 7 ,-1 , 0
  4308.1     .05       0  4422.2     .08       0  4507.1     .05       0
  4517.3     .16       0  4911.6     .03       0  4911.6     .16       0
  5173.3     .05       0
#XS Ineff= 1 ,-1
 4456.36 4854.55382.8393
Permanent Ineff=
       F
Bank Sta=4870.5,5022.1
XS Rating Curve= 0 ,0
Exp/Cntr=0.3,0.1

Type RM Length L Ch R = 1 ,97      ,0,0,0
BEGIN DESCRIPTION:
UNT 025 IN UKCR 1.0
END DESCRIPTION:
XS GIS Cut Line= 5
      3593759.25     10591348.71      3593266.66     10591372.58
      3592988.88     10591795.76       3592958.5     10591962.86
      3593205.91     10592537.99
#Sta/Elev= 30
  4090.6  399.28  4290.5  385.73  4370.6  383.37  4460.7   383.9  4490.3  382.43
  4550.8  378.73  4593.2  377.15  4652.7  379.07  4688.6  377.37  4695.7  378.26
  4800.3  377.36  4954.8  377.94  4969.9  378.95    4985   378.6  4996.6  376.79
  4999.3  376.29  5002.6  376.79  5006.1  377.65  5057.4  378.33  5169.1  378.29
  5268.9  379.22  5333.1  380.13    5344  381.31  5373.9  380.35  5518.2  384.48
  5583.9  387.91  5616.1  391.79  5714.1  398.47  5736.1  401.31  5885.9  407.62
#Mann= 7 ,-1 , 0
  4090.6     .05       0  4490.3     .07       0  4800.3     .12       0
  4996.6     .07       0  5002.6     .12       0  5169.1     .07       0
  5268.9     .05       0
Bank Sta=4550.8,5169.1
XS Rating Curve= 0 ,0
Exp/Cntr=0.3,0.1

Chan Stop Cuts=-1
Use User Specified Reach Order=0
Composite Channel Slope=5