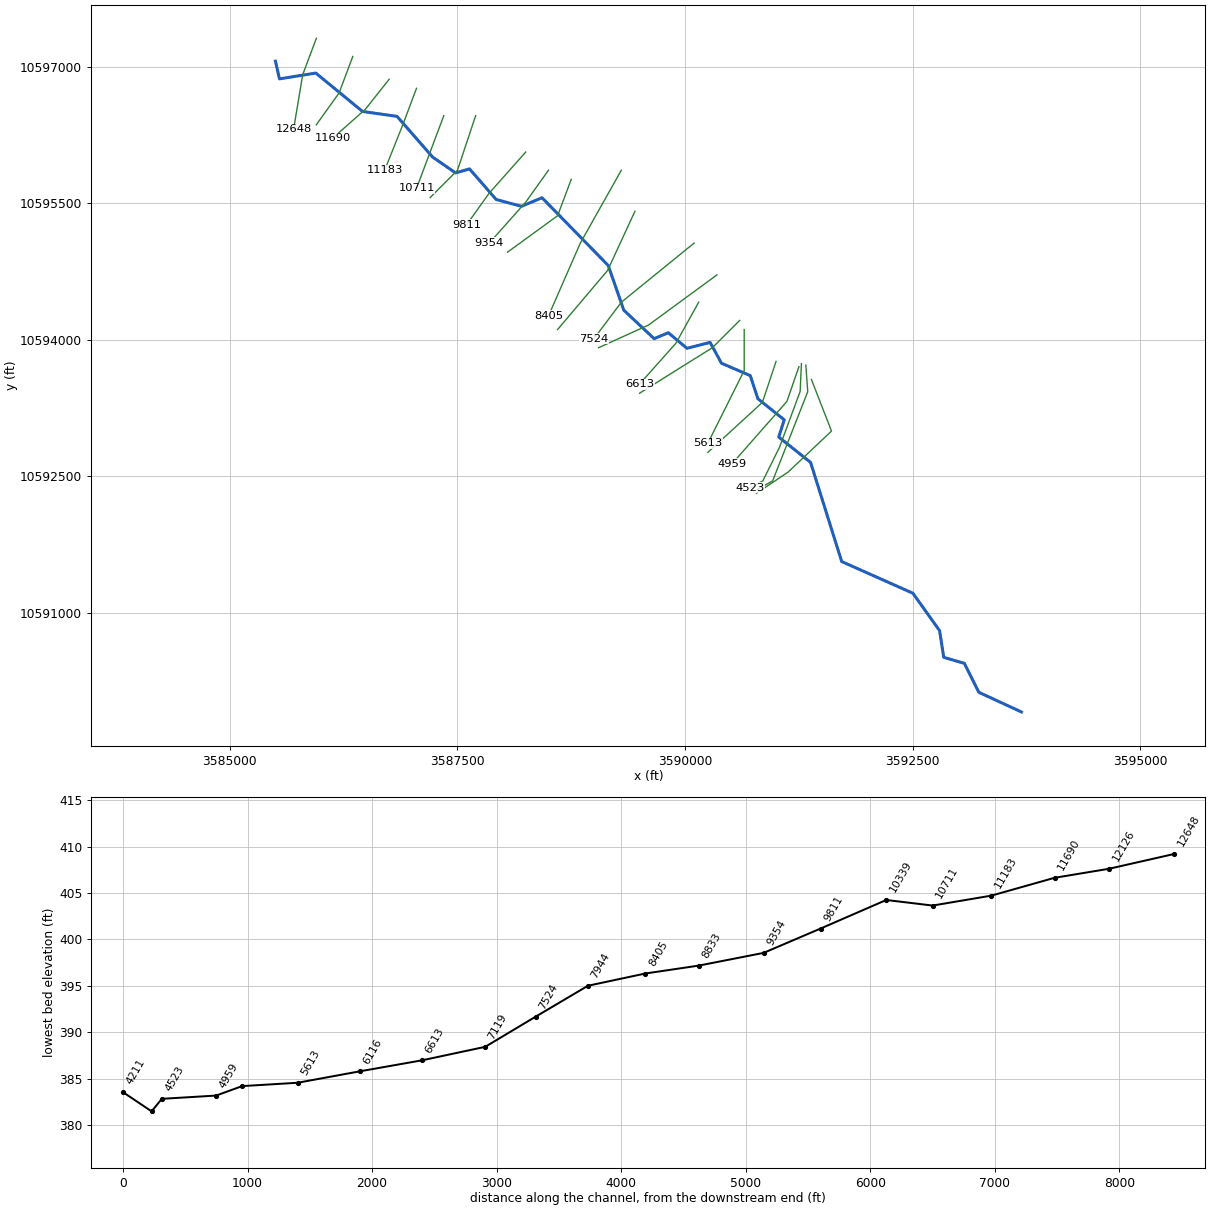
--- UNT 026 IN UKCR.prj (project) ---

Proj Title=UNT 026 IN UKCR Base Level Engineering
Current Plan=p01
Default Exp/Contr=0.3,0.1
English Units
Geom File=g01
Flow File=f01
Plan File=p01
Y Axis Title=Elevation
X Axis Title(PF)=Main Channel Distance
X Axis Title(XS)=Station
BEGIN DESCRIPTION:
UNT 026 IN UKCR
END DESCRIPTION:
DSS Export Rating Curves= 0
DSS Export Rating Curve Sorted= 0
DSS Export Volume Flow Curves= 0
DXF OffsetX= 0
DXF OffsetY= 0
DXF ScaleX= 1
DXF ScaleY= 10

--- UNT 026 IN UKCR.p01 (plan) ---

Plan Title=Multiple Run
Short Identifier=Multiple
Geom File=g01
Flow File=f01
Subcritical Flow
K Sum by GR= 0
Std Step Tol= 0.01
Critical Tol= 0.01
Num of Std Step Trials= 20
Max Error Tol= 0.3
Flow Tol Ratio= 0.001
Split Flow NTrial= 30
Split Flow Tol= 0.02
Split Flow Ratio= 0.02
Log Output Level= 0
Friction Slope Method= 1
Unsteady Friction Slope Method= 2
Unsteady Bridges Friction Slope Method= 1
Parabolic Critical Depth
Global Vel Dist=  1 , 1 , 1
Global Log Level= 0
CheckData=True
Encroach Param= -1, 0, 0, 0
BEGIN DESCRIPTION:
Multiple Run
END DESCRIPTION:

--- UNT 026 IN UKCR.f01 (steady flow) ---

Flow Title=Multiple
Program Version=4.10
Number of Profiles= 7
Profile Names=10-year,25-year,50-year,1pct_min,100-year,1pct_plu,500-year
River Rch & RM=UNT 026 IN UKCR,Reach-1         ,12648
    1591    2219    2744    2473    3344    4522    4950
River Rch & RM=UNT 026 IN UKCR,Reach-1         ,5613
    1785    2502    3104    2804    3792    5128    5642
River Rch & RM=UNT 026 IN UKCR,Reach-1         ,4523
    1785    2502    3104    2804    3792    5128    5642
Boundary for River Rch & Prof#=UNT 026 IN UKCR,Reach-1         , 1
Up Type= 0
Dn Type= 3
Dn Slope=0.005
Boundary for River Rch & Prof#=UNT 026 IN UKCR,Reach-1         , 2
Up Type= 0
Dn Type= 3
Dn Slope=0.005
Boundary for River Rch & Prof#=UNT 026 IN UKCR,Reach-1         , 3
Up Type= 0
Dn Type= 3
Dn Slope=0.005
Boundary for River Rch & Prof#=UNT 026 IN UKCR,Reach-1         , 4
Up Type= 0
Dn Type= 3
Dn Slope=0.005
Boundary for River Rch & Prof#=UNT 026 IN UKCR,Reach-1         , 5
Up Type= 0
Dn Type= 3
Dn Slope=0.005
Boundary for River Rch & Prof#=UNT 026 IN UKCR,Reach-1         , 6
Up Type= 0
Dn Type= 3
Dn Slope=0.005
Boundary for River Rch & Prof#=UNT 026 IN UKCR,Reach-1         , 7
Up Type= 0
Dn Type= 3
Dn Slope=0.005
DSS Import GetInterval= 0
DSS Import GetPeak= 0
DSS Import FillOption= 0

--- UNT 026 IN UKCR.g01 (geometry) ---

Geom Title=Existing Conditions
Program Version=4.10

River Reach=UNT 026 IN UKCR ,Reach-1
Reach XY= 30
      3585499.75       10597059.      3585544.25       10596864.
       3585943.5       10596928.        3586457.       10596506.
        3586836.       10596452.      3587226.75       10596005.
        3587479.       10595831.        3587632.       10595875.
      3587924.75       10595539.       3588202.5       10595464.
      3588428.75       10595558.      3589155.75       10594814.
      3589326.75       10594323.      3589659.75       10594010.
      3589816.25       10594075.       3590020.5       10593904.
      3590275.25       10593969.      3590399.75       10593740.
       3590716.5       10593604.      3590799.75       10593350.
       3591089.5       10593118.      3591028.75       10592929.
      3591378.84     10592650.32      3591720.75       10591561.
        3592503.       10591213.      3592795.75       10590802.
      3592841.75       10590509.      3593067.75       10590443.
        3593227.       10590125.      3593695.03     10589908.77

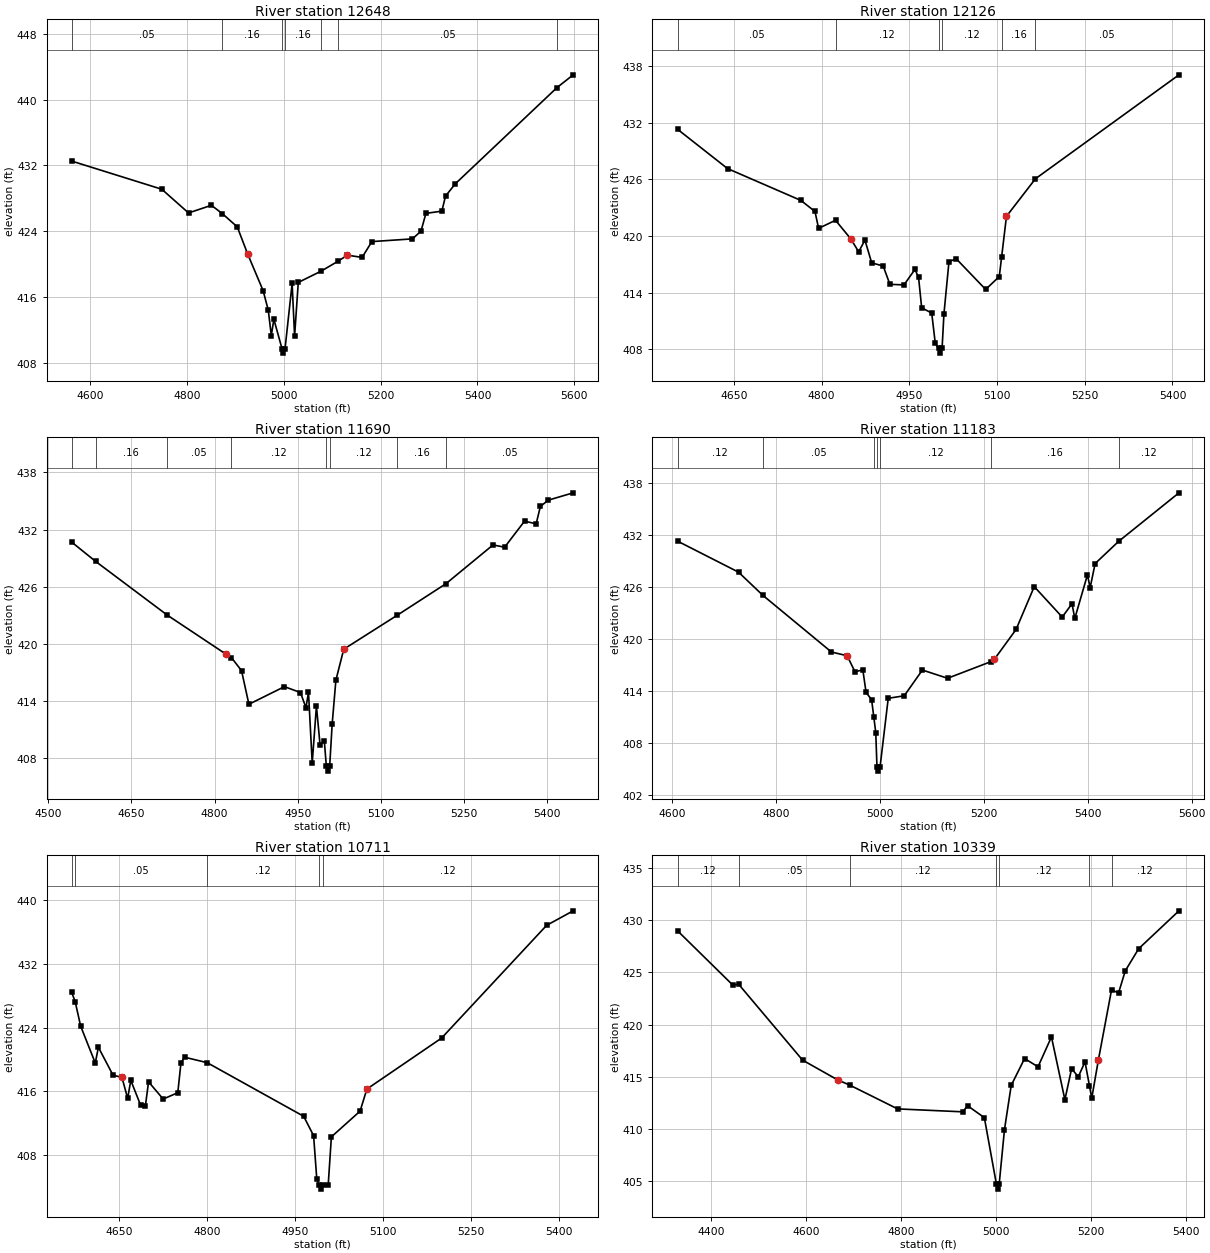
Type RM Length L Ch R = 1 ,12648   ,522,522,522
BEGIN DESCRIPTION:
UNT 026 IN UKCR 18.0
END DESCRIPTION:
XS GIS Cut Line= 3
      3585949.62     10597310.21      3585799.61     10596910.19
      3585699.61     10596310.19
#Sta/Elev= 30
  4562.1  432.53  4748.1  429.11  4803.3  426.23  4850.5  427.16    4873  426.15
  4903.9  424.54  4925.2  421.27  4957.3  416.79    4968   414.4  4974.2  411.34
  4979.5  413.31  4996.5   409.7  4999.2   409.2  5002.5   409.7  5017.2  417.66
  5022.3  411.27  5029.9  417.79  5077.1  419.16  5111.6  420.35  5131.3   421.1
  5161.7  420.83  5181.9  422.75  5265.6  423.08  5283.3  424.02  5293.5  426.18
  5326.4  426.45    5334  428.28  5354.3  429.78    5564  441.45  5597.6  443.01
#Mann= 7 ,-1 , 0
  4562.1     .05       0    4873     .16       0  4996.5     .07       0
  5002.5     .16       0  5077.1     .08       0  5111.6     .05       0
    5564     .08       0
Bank Sta=4925.2,5131.3
XS Rating Curve= 0 ,0
Exp/Cntr=0.3,0.1

Type RM Length L Ch R = 1 ,12126   ,436,436,436
BEGIN DESCRIPTION:
UNT 026 IN UKCR 17.0
END DESCRIPTION:
XS GIS Cut Line= 3
      3586349.61      10597110.2      3586199.61     10596710.19
      3585949.63     10596360.21
#Sta/Elev= 30
  4553.8   431.3  4639.3  427.14  4764.7  423.77  4788.8   422.6    4795  420.81
  4823.9  421.67  4850.2  419.69  4863.5  418.33  4874.2  419.57  4885.8  417.16
  4905.4  416.83  4916.9  414.89    4941  414.83  4959.7  416.47  4965.9  415.63
  4971.2  412.41  4988.4  411.85  4994.5  408.63  5000.1  408.11  5002.9  407.61
  5006.1  408.11  5009.3  411.77  5017.9  417.29  5030.2   417.6  5080.6  414.35
  5103.9  415.71  5107.8  417.73  5116.2  422.09  5165.7  426.06  5411.1  437.06
#Mann= 6 ,-1 , 0
  4553.8     .05       0  4823.9     .12       0  5000.1     .07       0
  5006.1     .12       0  5107.8     .16       0  5165.7     .05       0
Bank Sta=4850.2,5116.2
XS Rating Curve= 0 ,0
Exp/Cntr=0.3,0.1

Type RM Length L Ch R = 1 ,11690   ,507,507,507
BEGIN DESCRIPTION:
UNT 026 IN UKCR 16.0
END DESCRIPTION:
XS GIS Cut Line= 3
      3586749.61     10596860.18      3586487.08     10596529.15
      3586125.98     10596209.72
#Sta/Elev= 30
  4542.2  430.68  4585.1  428.67  4714.3  423.03  4820.2  418.93  4830.1  418.57
  4848.5  417.19  4861.8  413.66  4925.9  415.51  4954.8  414.89  4964.7   413.3
  4969.3  414.91    4976  407.49  4983.6  413.46  4990.2  409.37  4997.8  409.85
  5001.5  407.14  5004.2  406.64  5007.5  407.14    5012  411.58  5018.7  416.18
  5032.9  419.44  5129.2     423  5217.3  426.32  5302.2  430.39  5323.1  430.15
  5359.1  432.89    5380   432.6  5387.6  434.43  5401.8  435.09  5446.8  435.86
#Mann= 8 ,-1 , 0
  4542.2     .12       0  4585.1     .16       0  4714.3     .05       0
  4830.1     .12       0  5001.5     .07       0  5007.5     .12       0
  5129.2     .16       0  5217.3     .05       0
Bank Sta=4820.2,5032.9
XS Rating Curve= 0 ,0
Exp/Cntr=0.3,0.1

Type RM Length L Ch R = 1 ,11183   ,472,472,472
BEGIN DESCRIPTION:
UNT 026 IN UKCR 15.0
END DESCRIPTION:
XS GIS Cut Line= 3
      3587049.61     10596760.19      3586899.61     10596360.19
      3586699.62      10595860.2
#Sta/Elev= 30
  4609.9  431.25  4727.4  427.67  4774.2     425  4906.3  418.46  4936.5  418.03
  4951.7  416.18  4966.8   416.4    4973   413.8  4983.7  412.96    4988  410.92
  4991.7  409.16    4994  405.22  4996.8  404.72    5000  405.22  5015.7  413.12
  5046.5  413.41  5081.5  416.38    5130  415.43  5213.1  417.34  5220.2  417.63
  5261.9  421.06  5296.9     426  5350.8  422.49  5369.6  424.03    5375  422.33
  5399.3  427.35  5404.6  425.89  5414.1  428.66  5459.4  431.22  5575.6  436.82
#Mann= 7 ,-1 , 0
  4609.9     .12       0  4774.2     .05       0    4988     .12       0
    4994     .07       0    5000     .12       0  5213.1     .16       0
  5459.4     .12       0
Bank Sta=4936.5,5220.2
XS Rating Curve= 0 ,0
Exp/Cntr=0.3,0.1

Type RM Length L Ch R = 1 ,10711   ,372,372,372
BEGIN DESCRIPTION:
UNT 026 IN UKCR 14.0
END DESCRIPTION:
XS GIS Cut Line= 3
      3587349.63     10596460.23      3587199.61     10596060.19
      3587049.63     10595660.23
#Sta/Elev= 30
    4570  428.41  4575.8  427.27  4585.2  424.17  4610.1  419.53  4615.4  421.51
  4640.4  417.99  4655.5  417.73  4665.3  415.07  4670.6  417.35  4687.5  414.19
  4695.5  414.13  4700.9  417.16  4725.8  414.99  4750.7  415.79  4756.1  419.56
  4762.3  420.26  4800.8  419.57  4965.2  412.82  4982.1  410.38  4987.5  404.94
  4991.6  404.15  4994.3  403.65  4997.6  404.15    5007  404.19  5012.4  410.23
  5061.3  413.47  5072.9  416.25  5200.2  422.67  5379.1  436.86  5424.4  438.69
#Mann= 5 ,-1 , 0
    4570     .12       0  4575.8     .05       0  4800.8     .12       0
  4991.6     .07       0  4997.6     .12       0
Bank Sta=4655.5,5072.9
XS Rating Curve= 0 ,0
Exp/Cntr=0.3,0.1

Type RM Length L Ch R = 1 ,10339   ,528,528,528
BEGIN DESCRIPTION:
UNT 026 IN UKCR 13.0
END DESCRIPTION:
XS GIS Cut Line= 3
       3587699.6     10596460.17      3587499.61     10595860.19
      3587199.61     10595560.19
#Sta/Elev= 30
  4329.3  428.98  4445.2  423.81  4458.3  423.85  4592.8   416.6  4666.6  414.71
  4692.6   414.2  4793.1  411.93  4930.1  411.65  4940.7  412.23  4975.9  411.09
  5001.2  404.75  5003.9  404.25  5007.2  404.75  5018.3  409.95  5032.5  414.18
  5060.7  416.75    5089  415.96  5117.3  418.82  5145.6  412.81  5159.7  415.77
  5173.9  415.01    5188  416.44  5197.3  414.16  5202.2  412.96  5216.3  416.64
  5243.9  423.32  5258.7  423.03  5272.9  425.15  5301.2  427.27    5386  430.89
#Mann= 7 ,-1 , 0
  4329.3     .12       0  4458.3     .05       0  4692.6     .12       0
  5001.2     .07       0  5007.2     .12       0  5197.3     .05       0
  5243.9     .12       0
Bank Sta=4666.6,5216.3
XS Rating Curve= 0 ,0
Exp/Cntr=0.3,0.1

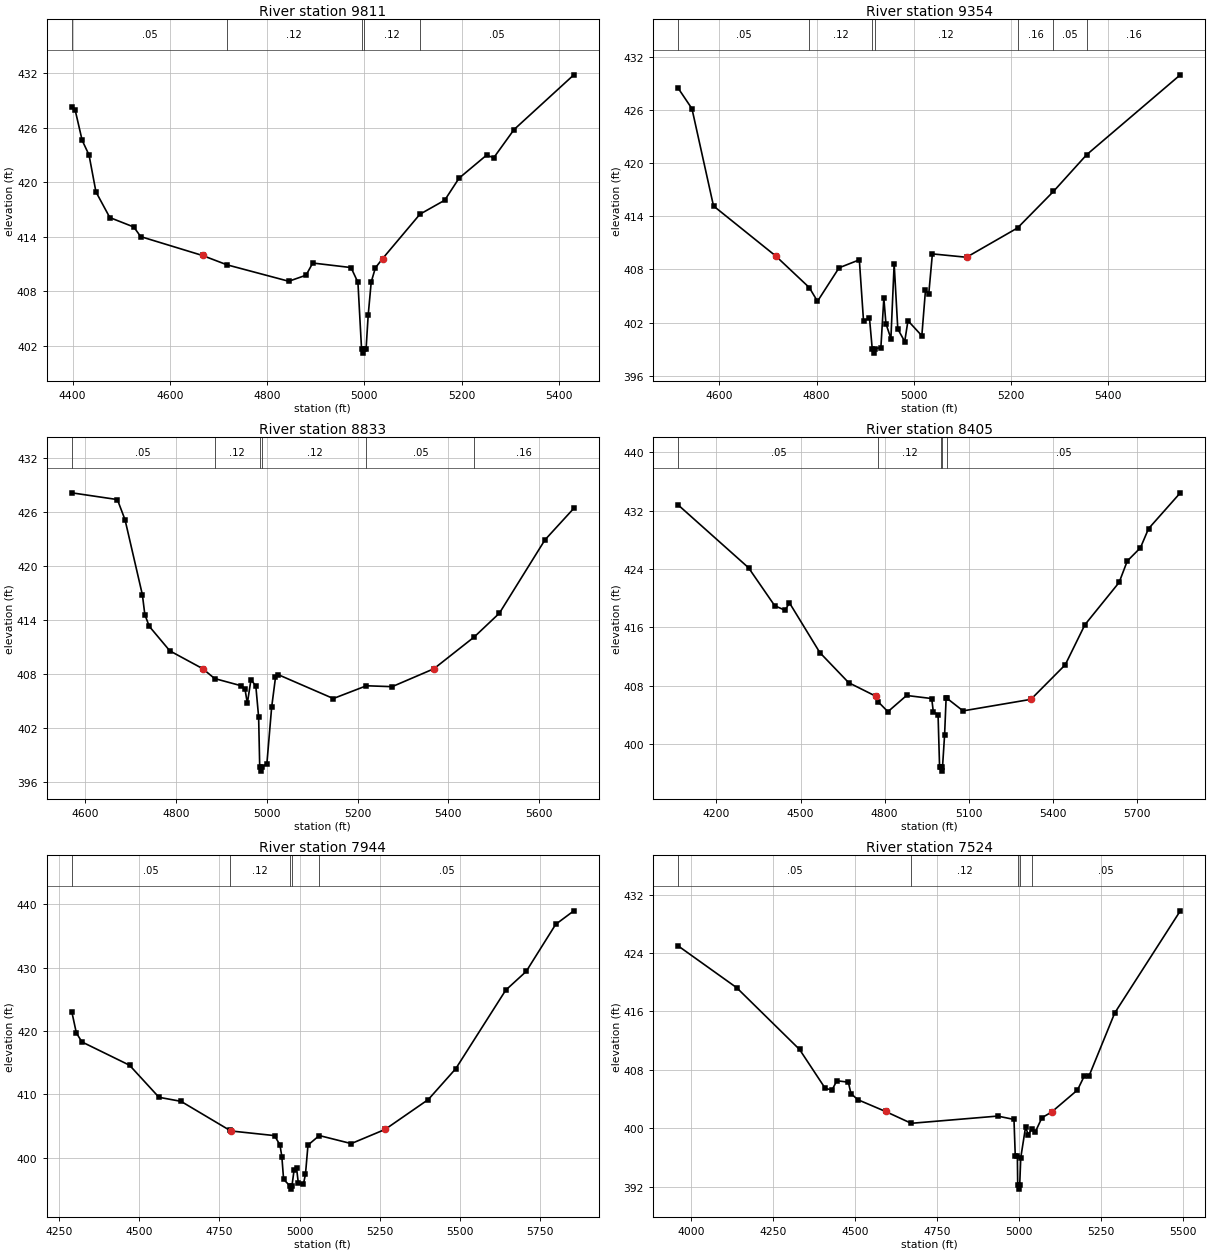
Type RM Length L Ch R = 1 ,9811    ,457,457,457
BEGIN DESCRIPTION:
UNT 026 IN UKCR 12.0
END DESCRIPTION:
XS GIS Cut Line= 3
       3588249.6     10596060.18      3587849.61     10595610.19
       3587599.6     10595260.17
#Sta/Elev= 30
  4398.4   428.3  4405.5  427.93  4419.7  424.63  4433.9     423  4448.1  418.94
  4476.6  416.11  4525.9  415.07  4540.1  414.01  4667.2  411.93  4717.6   410.9
  4844.5  409.09  4880.1  409.76  4893.8   411.1  4972.5   410.6  4986.7  408.97
  4994.1  401.67  4996.9  401.17  5000.1  401.67  5003.5  401.67  5007.8  405.35
    5014     409  5022.6  410.57  5037.3  411.58  5114.2  416.48  5165.1  418.02
  5194.6  420.45  5251.2  422.99  5265.9   422.7  5307.7  425.81  5430.6  431.84
#Mann= 5 ,-1 , 0
  4398.4     .05       0  4717.6     .12       0  4994.1     .07       0
  5000.1     .12       0  5114.2     .05       0
Bank Sta=4667.2,5037.3
XS Rating Curve= 0 ,0
Exp/Cntr=0.3,0.1

Type RM Length L Ch R = 1 ,9354    ,521,521,521
BEGIN DESCRIPTION:
UNT 026 IN UKCR 11.0
END DESCRIPTION:
XS GIS Cut Line= 3
       3588499.6     10595860.18      3588249.61     10595510.19
       3587849.6     10595060.17
#Sta/Elev= 30
  4515.6  428.44  4543.8  426.14  4588.1  415.16  4715.9  409.52    4785  405.95
  4801.9   404.4  4846.2  408.18  4887.9  409.08  4896.5   402.2  4908.8  402.48
  4914.4  399.05  4917.2  398.55  4920.4  399.05  4932.2  399.18  4938.3  404.76
  4942.6  401.88  4952.8  400.19  4959.5  408.64    4967  401.27  4981.2  399.86
  4987.9  402.21  5016.4  400.51  5023.9  405.66  5030.6  405.21  5038.1  409.75
  5108.3  409.37  5213.2  412.68    5287   416.8  5355.2  420.94  5547.8  429.96
#Mann= 7 ,-1 , 0
  4515.6     .05       0    4785     .12       0  4914.4     .07       0
  4920.4     .12       0  5213.2     .16       0    5287     .05       0
  5355.2     .16       0
Bank Sta=4715.9,5108.3
XS Rating Curve= 0 ,0
Exp/Cntr=0.3,0.1

Type RM Length L Ch R = 1 ,8833    ,428,428,428
BEGIN DESCRIPTION:
UNT 026 IN UKCR 10.0
END DESCRIPTION:
XS GIS Cut Line= 3
      3588749.63     10595760.23      3588599.61     10595360.19
      3588049.62      10594960.2
#Sta/Elev= 30
  4569.8  428.12  4670.4  427.37  4687.3  425.12  4725.6  416.77  4730.9  414.59
  4740.7  413.28  4786.1  410.55  4858.2  408.58    4885  407.47  4943.6  406.67
  4951.7  406.33    4957  404.72    4965  407.34  4975.7  406.65  4981.9   403.2
  4984.3  397.68    4987  397.18  4990.3  397.68  5000.1     398  5010.6  404.27
  5019.1   407.6  5025.3   407.9  5146.6  405.25  5219.7  406.67  5276.4  406.57
  5368.4  408.56  5457.5   412.1  5512.9  414.74  5613.4  422.89  5677.1   426.4
#Mann= 6 ,-1 , 0
  4569.8     .05       0    4885     .12       0  4984.3     .07       0
  4990.3     .12       0  5219.7     .05       0  5457.5     .16       0
Bank Sta=4858.2,5368.4
XS Rating Curve= 0 ,0
Exp/Cntr=0.3,0.1

Type RM Length L Ch R = 1 ,8405    ,461,461,461
BEGIN DESCRIPTION:
UNT 026 IN UKCR 9.0
END DESCRIPTION:
XS GIS Cut Line= 3
      3589299.61     10595860.19      3588849.61     10595060.19
      3588499.61     10594260.19
#Sta/Elev= 30
  4063.7  432.77  4314.5  424.18  4407.9  418.98  4444.6  418.36  4460.5  419.37
  4568.9  412.56  4671.8  408.44  4768.4  406.59  4777.8  405.79  4811.7  404.47
  4878.3  406.69  4967.9  406.27  4973.6  404.48  4990.6  404.04    4996   396.9
  5000.4  396.83  5003.2  396.33  5006.4  396.83  5013.9  401.28  5019.4  406.39
  5021.5  406.33  5079.8  404.58  5321.9  406.16  5444.3  410.89  5514.5  416.38
  5636.5  422.17  5665.7  425.11  5712.5  426.91  5741.4  429.53  5854.8  434.44
#Mann= 5 ,-1 , 0
  4063.7     .05       0  4777.8     .12       0  5000.4     .07       0
  5006.4     .12       0  5021.5     .05       0
Bank Sta=4768.4,5321.9
XS Rating Curve= 0 ,0
Exp/Cntr=0.3,0.1

Type RM Length L Ch R = 1 ,7944    ,420,420,420
BEGIN DESCRIPTION:
UNT 026 IN UKCR 8.0
END DESCRIPTION:
XS GIS Cut Line= 3
      3589449.63     10595410.23      3589149.61     10594760.19
      3588599.61     10594110.19
#Sta/Elev= 30
  4288.9  423.04  4303.2  419.67  4320.6  418.25  4469.3  414.57  4561.1  409.51
  4629.9  408.87  4782.6  404.28  4784.6   404.2  4921.8  403.46  4938.8  401.99
  4944.7  400.16  4950.2  396.55  4970.2  395.51  4972.9  395.01  4976.2  395.51
  4982.8  397.96  4990.6  398.33  4996.1  396.01    5012  395.79  5018.5  397.37
  5026.3  401.96  5061.6  403.47  5161.4   402.2  5266.8  404.43    5402  409.16
  5487.7  414.03  5643.7  426.43  5707.5  429.38  5799.7  436.82  5856.3  438.95
#Mann= 5 ,-1 , 0
  4288.9     .05       0  4782.6     .12       0  4970.2     .07       0
  4976.2     .12       0  5061.6     .05       0
Bank Sta=4784.6,5266.8
XS Rating Curve= 0 ,0
Exp/Cntr=0.3,0.1

Type RM Length L Ch R = 1 ,7524    ,405,405,405
BEGIN DESCRIPTION:
UNT 026 IN UKCR 7.0
END DESCRIPTION:
XS GIS Cut Line= 3
      3590099.58     10595060.16      3589299.61     10594410.19
      3588999.63     10594010.22
#Sta/Elev= 30
  3960.1  424.97  4138.2  419.26    4330   410.8  4408.3  405.47  4429.1  405.25
  4443.5  406.52  4478.7  406.32  4486.6  404.77  4507.4  403.93  4592.2  402.31
  4670.5  400.69  4934.1  401.68  4983.7  401.22  4987.6  396.23    4994  396.23
  4995.1  392.18  4997.9  391.68  5001.1  392.18  5004.4  395.99    5019  400.17
  5027.3  399.13  5038.4  399.93  5048.1  399.46    5069  401.46  5098.1  402.22
  5177.3  405.25  5198.1  407.17  5212.7  407.19  5290.8  415.79  5490.8  429.78
#Mann= 5 ,-1 , 0
  3960.1     .05       0  4670.5     .12       0  4995.1     .07       0
  5001.1     .12       0  5038.4     .05       0
Bank Sta=4592.2,5098.1
XS Rating Curve= 0 ,0
Exp/Cntr=0.3,0.1

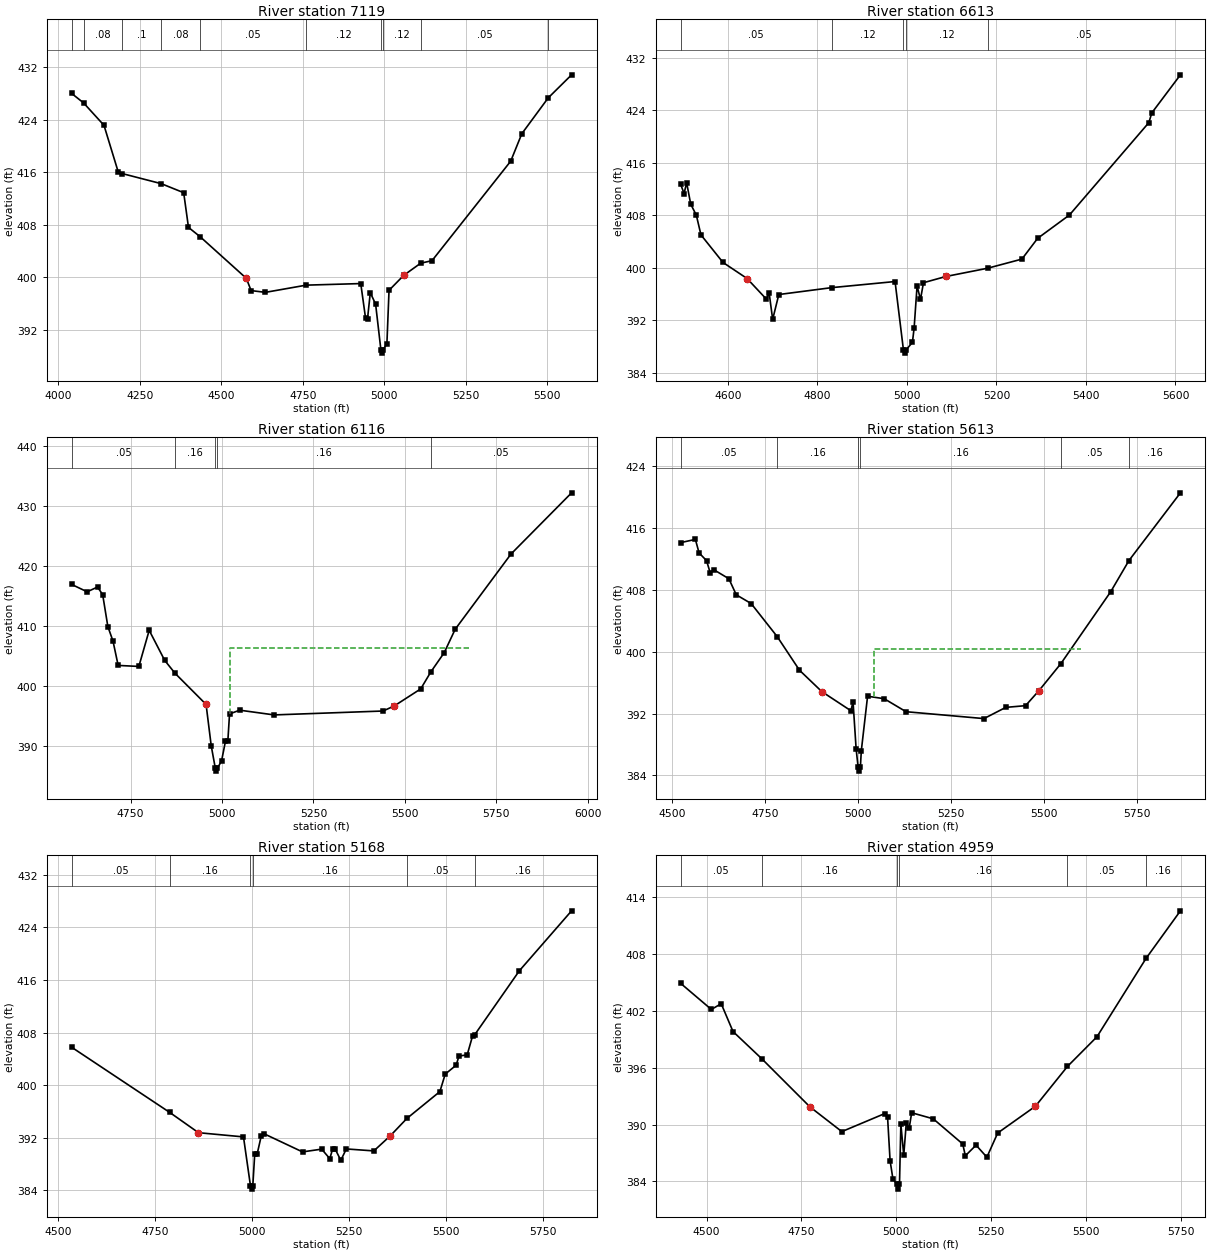
Type RM Length L Ch R = 1 ,7119    ,506,506,506
BEGIN DESCRIPTION:
UNT 026 IN UKCR 6.0
END DESCRIPTION:
XS GIS Cut Line= 3
      3590349.58     10594710.16      3589599.61     10594160.19
      3589049.58     10593910.17
#Sta/Elev= 30
  4040.8  428.04  4077.3   426.6    4140  423.18  4183.9  416.03  4196.5  415.81
  4315.7  414.28  4384.6   412.9  4399.3  407.61    4435  406.19  4576.8  399.84
  4591.5  397.97  4635.4   397.7  4760.6   398.8    4928  399.04  4942.6  393.82
  4948.8   393.7  4957.3  397.65  4973.6   395.9  4989.8  388.93  4992.5  388.43
  4995.8  388.93  5008.2  389.82  5014.8  398.01  5059.8  400.29    5112  402.15
  5146.6  402.53  5388.2  417.71  5422.3   421.9  5503.4  427.37    5575  430.88
#Mann= 10 ,-1 , 0
  4040.8     .05       0  4077.3     .08       0  4196.5      .1       0
  4315.7     .08       0    4435     .05       0  4760.6     .12       0
  4989.8     .07       0  4995.8     .12       0    5112     .05       0
  5503.4     .16       0
Bank Sta=4576.8,5059.8
XS Rating Curve= 0 ,0
Exp/Cntr=0.3,0.1

Type RM Length L Ch R = 1 ,6613    ,497,497,497
BEGIN DESCRIPTION:
UNT 026 IN UKCR 5.0
END DESCRIPTION:
XS GIS Cut Line= 3
      3590149.59     10594410.16      3589899.61     10593960.19
      3589499.63     10593510.21
#Sta/Elev= 30
  4494.2  412.77  4502.2   411.3  4507.9  412.95    4517  409.69  4529.6  407.99
  4539.9     405  4589.1   400.8  4642.9  398.35  4686.3  395.19  4692.1  396.21
  4700.1  392.12  4713.8  395.91    4832  396.96  4973.5  397.89  4992.2  387.48
    4995  386.98  4998.2  387.48  5012.3  388.62  5016.1  390.81  5022.7  397.22
  5030.3  395.17    5037  397.71  5087.1  398.66  5180.5  399.92  5256.9  401.31
    5292  404.47  5363.1  408.03  5540.4   422.1  5547.1  423.59    5611  429.39
#Mann= 5 ,-1 , 0
  4494.2     .05       0    4832     .12       0  4992.2     .07       0
  4998.2     .12       0  5180.5     .05       0
Bank Sta=4642.9,5087.1
XS Rating Curve= 0 ,0
Exp/Cntr=0.3,0.1

Type RM Length L Ch R = 1 ,6116    ,503,503,503
BEGIN DESCRIPTION:
UNT 026 IN UKCR 4.0
END DESCRIPTION:
XS GIS Cut Line= 3
      3590599.58     10594210.16      3590299.61     10593910.19
      3589499.62      10593410.2
#Sta/Elev= 30
  4588.7  416.92  4631.1  415.69  4659.4  416.49  4673.5  415.23  4687.7   409.9
  4701.8  407.47  4715.9  403.42  4772.5  403.25  4800.8  409.27  4843.2  404.26
  4871.5  402.11  4956.4  396.92  4970.5  390.02  4981.6   386.3  4984.4   385.8
  4987.6   386.3  4998.8  387.51  5009.4  390.77  5015.9  390.77  5020.6  395.33
  5048.3  395.96  5142.6  395.17  5440.4  395.82  5471.1  396.66  5543.6  399.51
  5571.3  402.34  5607.9  405.55  5637.9  409.45  5790.6  421.99  5956.3  432.19
#Mann= 5 ,-1 , 0
  4588.7     .05       0  4871.5     .16       0  4981.6     .07       0
  4987.6     .16       0  5571.3     .05       0
#XS Ineff= 2 ,-1
 4670.91 4806.36  406.46 5022.73 5676.36  406.36
Permanent Ineff=
       F       F
Bank Sta=4956.4,5471.1
XS Rating Curve= 0 ,0
Exp/Cntr=0.3,0.1

Type RM Length L Ch R = 1 ,5613    ,445,445,445
BEGIN DESCRIPTION:
UNT 026 IN UKCR 3.0
END DESCRIPTION:
XS GIS Cut Line= 3
      3590649.61     10594110.16      3590649.61     10593660.19
      3590249.61     10592860.19
#Sta/Elev= 30
  4522.9  414.09  4562.9  414.51  4572.9  412.76  4592.9  411.77  4602.9  410.17
  4612.9  410.58  4652.9  409.43  4672.9  407.35  4712.9  406.22  4782.9  401.95
  4842.9   397.6  4902.9  394.84  4981.3  392.36  4986.9  393.54  4995.2  387.43
  5000.6  385.06  5003.4  384.56  5006.6  385.06  5009.2  387.22    5026  394.24
  5070.7  393.92  5129.4  392.24    5339  391.35  5397.7   392.8  5450.8  393.02
  5487.2  394.98  5545.9  398.46    5680  407.76  5728.9  411.78  5867.3  420.53
#Mann= 6 ,-1 , 0
  4522.9     .05       0  4782.9     .16       0  5000.6     .07       0
  5006.6     .16       0  5545.9     .05       0  5728.9     .16       0
#XS Ineff= 1 ,-1
 5044.55    5600  400.36
Permanent Ineff=
       F
Bank Sta=4902.9,5487.2
XS Rating Curve= 0 ,0
Exp/Cntr=0.3,0.1

Type RM Length L Ch R = 1 ,5168    ,209,209,209
BEGIN DESCRIPTION:
UNT 026 IN UKCR 2.0
END DESCRIPTION:
XS GIS Cut Line= 3
      3590999.62     10593760.22      3590849.61     10593310.19
      3590249.62      10592760.2
#Sta/Elev= 30
  4534.4  405.77  4787.4  395.85  4861.2  392.78  4977.2  392.14  4995.2   384.7
    4998   384.2  5001.2   384.7  5006.1  389.48  5012.2  389.48  5022.7  392.22
  5030.1  392.62  5129.3  389.86  5178.7  390.28  5199.6  388.83    5207  390.32
  5213.8  390.25    5228  388.58  5242.2  390.31  5313.1  390.01  5355.6  392.31
  5398.2  394.94  5483.3  399.03  5497.1  401.69  5525.2  403.04  5532.6  404.44
  5553.6   404.6  5567.7  407.52  5573.3  407.69    5688  417.39  5822.7  426.51
#Mann= 6 ,-1 , 0
  4534.4     .05       0  4787.4     .16       0  4995.2     .07       0
  5001.2     .16       0  5398.2     .05       0  5573.3     .16       0
Bank Sta=4861.2,5355.6
XS Rating Curve= 0 ,0
Exp/Cntr=0.3,0.1

Type RM Length L Ch R = 1 ,4959    ,436,436,436
BEGIN DESCRIPTION:
Mapping XS dcc74b88
END DESCRIPTION:
XS GIS Cut Line= 3
      3591250.96     10593702.75      3591119.02     10593320.82
      3590515.66     10592634.24
#Sta/Elev= 30
  4431.4  404.91  4512.8  402.14  4538.7  402.75  4569.9  399.81  4645.7  396.94
  4772.7  391.86  4856.8  389.25  4969.7  391.15  4977.3  390.82    4984  386.18
  4991.5  384.25  5002.8  383.68  5005.5  383.18  5008.8  383.68  5012.4  390.05
    5020  386.75  5026.6  390.11  5034.2  389.59  5040.9  391.24  5097.8   390.6
  5175.6  387.94  5182.4   386.7  5210.7  387.82  5239.2  386.55  5267.7   389.1
  5367.3  391.93  5451.7  396.13  5529.5  399.26  5658.7  407.52  5749.5  412.55
#Mann= 6 ,-1 , 0
  4431.4     .05       0  4645.7     .16       0  5002.8     .07       0
  5008.8     .16       0  5451.7     .05       0  5658.7     .16       0
Bank Sta=4772.7,5367.3
XS Rating Curve= 0 ,0
Exp/Cntr=0.3,0.1

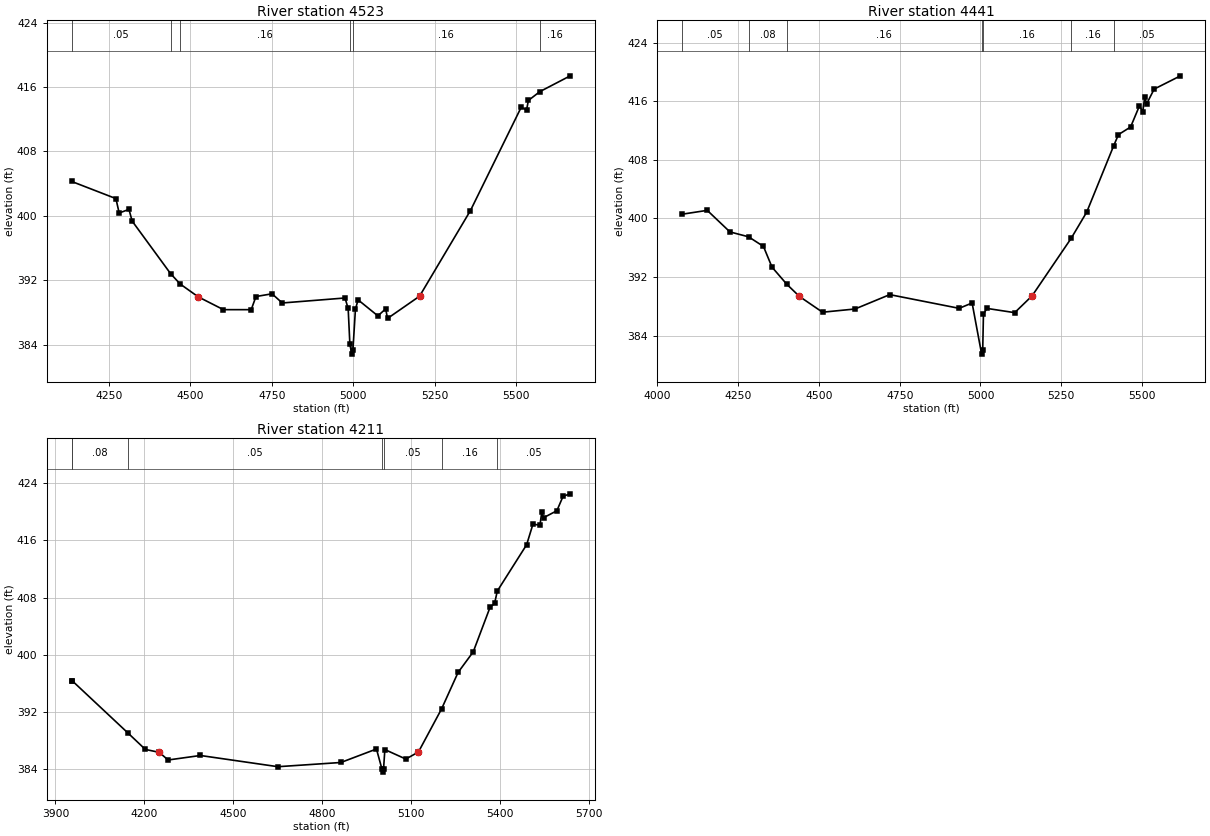
Type RM Length L Ch R = 1 ,4523    ,82,82,82
BEGIN DESCRIPTION:
Mapping XS 2ac99f41
END DESCRIPTION:
XS GIS Cut Line= 5
      3591278.11     10593736.02      3591264.22     10593430.42
      3591038.52     10592819.31      3590854.49     10592447.78
      3590715.59     10592371.39
#Sta/Elev= 30
  4135.5  404.27  4271.5  402.14  4281.5  400.35  4311.5   400.8  4321.5  399.34
  4439.2  392.83  4468.6  391.54  4524.2  389.94  4601.6  388.35  4686.8  388.35
  4701.4  389.98  4750.8  390.32  4782.1  389.18  4974.7   389.8  4984.4   388.5
  4989.7  384.03  4995.7  382.83    4999  383.33  5006.7   388.4  5014.8  389.57
  5075.6  387.58  5099.6  388.45  5105.2  387.26  5203.5  390.02  5359.7  400.65
  5515.8   413.5  5531.9  413.12  5537.6  414.32  5572.4  415.41    5666  417.38
#Mann= 6 ,-1 , 0
  4135.5     .05       0  4439.2     .08       0  4468.6     .16       0
  4989.7     .07       0    4999     .16       0  5572.4     .16       0
Bank Sta=4524.2,5203.5
XS Rating Curve= 0 ,0
Exp/Cntr=0.3,0.1

Type RM Length L Ch R = 1 ,4441    ,230,230,230
BEGIN DESCRIPTION:
Mapping XS ff5e277b
END DESCRIPTION:
XS GIS Cut Line= 4
      3591326.72     10593718.61      3591347.55     10593426.95
      3590962.13     10592447.78       3590788.5     10592350.55
#Sta/Elev= 30
  4075.5  400.57  4154.1   401.1  4224.3  398.16  4282.1  397.49  4328.1  396.18
  4354.6  393.35  4400.7     391  4439.6  389.35    4511   387.2  4611.6  387.64
  4719.1   389.6    4934  387.73  4974.1  388.46  5003.6  381.48  5006.9  381.98
  5009.2  386.95    5020  387.72  5105.9  387.14  5159.7  389.43  5280.7  397.28
  5328.9  400.86  5412.5  409.93  5427.2  411.44  5464.8  412.48  5492.2  415.37
  5502.5  414.54  5508.2  416.52  5514.8  415.67  5537.7  417.65  5619.2  419.46
#Mann= 7 ,-1 , 0
  4075.5     .05       0  4282.1     .08       0  4400.7     .16       0
  5003.6     .07       0  5006.9     .16       0  5280.7     .16       0
  5412.5     .05       0
Bank Sta=4439.6,5159.7
XS Rating Curve= 0 ,0
Exp/Cntr=0.3,0.1

Type RM Length L Ch R = 1 ,4211    ,0,0,0
BEGIN DESCRIPTION:
UNT 026 IN UKCR 1.0
END DESCRIPTION:
XS GIS Cut Line= 4
       3591387.9     10593562.06      3591608.55     10592994.68
      3591130.48     10592542.88      3590785.06     10592311.51
#Sta/Elev= 30
  3954.4  396.38  3955.5  396.38  4145.8  388.98  4203.2  386.73  4250.1  386.32
    4280  385.25  4388.9  385.88  4650.5  384.31  4862.9   384.9    4983  386.79
    5001  384.05  5003.8  383.55    5007  384.05  5011.3  386.71  5082.1  385.38
  5124.6  386.37  5202.7  392.41  5258.4  397.52  5309.5   400.4  5366.5  406.67
  5381.5  407.17  5390.6  408.91  5489.6   415.4  5510.9  418.28  5534.6  418.14
  5540.6  419.94    5547  419.19  5591.6  420.16  5612.6  422.19  5636.7  422.53
#Mann= 7 ,-1 , 0
  3954.4     .05       0  3955.5     .08       0  4145.8     .05       0
    5001     .03       0    5007     .05       0  5202.7     .16       0
  5390.6     .05       0
Bank Sta=4250.1,5124.6
XS Rating Curve= 0 ,0
Exp/Cntr=0.3,0.1

Chan Stop Cuts=-1
Use User Specified Reach Order=0
Composite Channel Slope=5