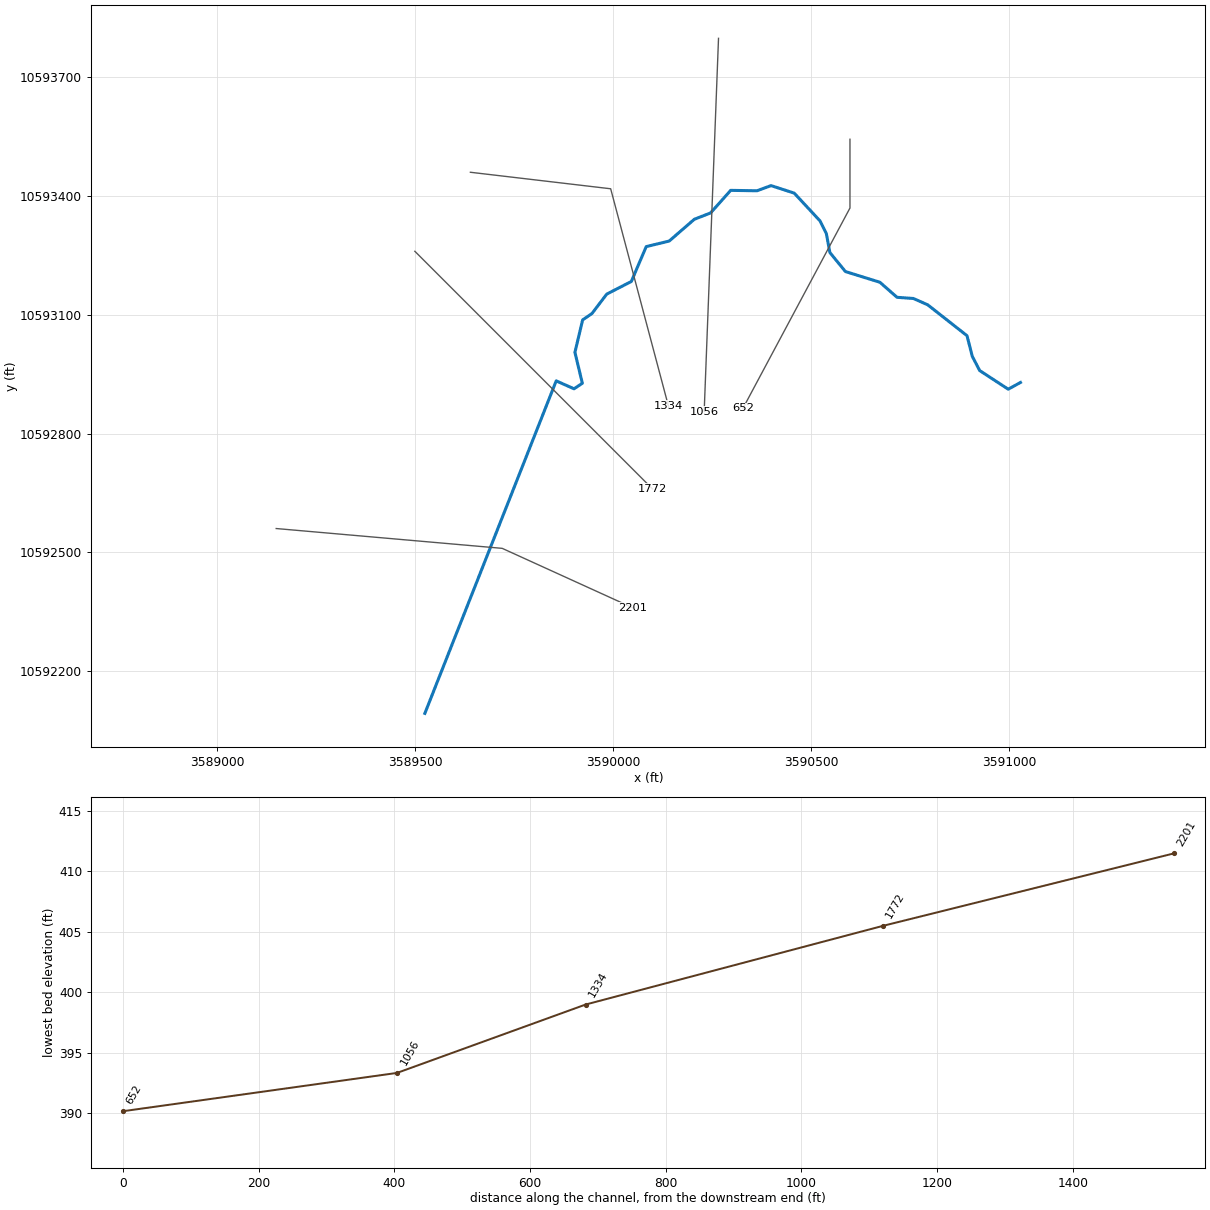
--- UNT 029 IN UKCR.prj (project) ---

Proj Title=UNT 029 IN UKCR Base Level Engineering
Current Plan=p01
Default Exp/Contr=0.3,0.1
English Units
Geom File=g01
Flow File=f01
Plan File=p01
Y Axis Title=Elevation
X Axis Title(PF)=Main Channel Distance
X Axis Title(XS)=Station
BEGIN DESCRIPTION:
UNT 029 IN UKCR
END DESCRIPTION:
DSS Export Rating Curves= 0
DSS Export Rating Curve Sorted= 0
DSS Export Volume Flow Curves= 0
DXF OffsetX= 0
DXF OffsetY= 0
DXF ScaleX= 1
DXF ScaleY= 10

--- UNT 029 IN UKCR.p01 (plan) ---

Plan Title=Multiple Run
Short Identifier=Multiple
Geom File=g01
Flow File=f01
Subcritical Flow
K Sum by GR= 0
Std Step Tol= 0.01
Critical Tol= 0.01
Num of Std Step Trials= 20
Max Error Tol= 0.3
Flow Tol Ratio= 0.001
Split Flow NTrial= 30
Split Flow Tol= 0.02
Split Flow Ratio= 0.02
Log Output Level= 0
Friction Slope Method= 1
Unsteady Friction Slope Method= 2
Unsteady Bridges Friction Slope Method= 1
Parabolic Critical Depth
Global Vel Dist=  1 , 1 , 1
Global Log Level= 0
CheckData=True
Encroach Param= -1, 0, 0, 0
BEGIN DESCRIPTION:
Multiple Run
END DESCRIPTION:

--- UNT 029 IN UKCR.f01 (steady flow) ---

Flow Title=Multiple
Number of Profiles=7
Profile Names=10-year,25-year,50-year,1pct_min,100-year,1pct_plu,500-year
River Rch & RM= UNT 029 IN UKCR,Reach-1,2201
     286     362     420     358     485     655     640
Boundary for River Rch & Prof#=UNT 029 IN UKCR,Reach-1,1
Up Type=0
Dn Type=3
Dn Slope=0.005
Boundary for River Rch & Prof#=UNT 029 IN UKCR,Reach-1,2
Up Type=0
Dn Type=3
Dn Slope=0.005
Boundary for River Rch & Prof#=UNT 029 IN UKCR,Reach-1,3
Up Type=0
Dn Type=3
Dn Slope=0.005
Boundary for River Rch & Prof#=UNT 029 IN UKCR,Reach-1,4
Up Type=0
Dn Type=3
Dn Slope=0.005
Boundary for River Rch & Prof#=UNT 029 IN UKCR,Reach-1,5
Up Type=0
Dn Type=3
Dn Slope=0.005
Boundary for River Rch & Prof#=UNT 029 IN UKCR,Reach-1,6
Up Type=0
Dn Type=3
Dn Slope=0.005
Boundary for River Rch & Prof#=UNT 029 IN UKCR,Reach-1,7
Up Type=0
Dn Type=3
Dn Slope=0.005

--- UNT 029 IN UKCR.g01 (geometry) ---

Geom Title=Existing Conditions
Program Version=4.10

River Reach=UNT 029 IN UKCR ,Reach-1
Reach XY= 30
      3589524.87     10592093.49       3589856.5       10592933.
       3589901.5       10592913.       3589922.5       10592927.
      3589903.75       10593005.      3589923.25       10593087.
      3589946.75       10593103.        3589984.       10593152.
      3590046.25       10593184.      3590083.75       10593272.
      3590141.75       10593286.      3590205.25       10593341.
      3590246.25       10593357.        3590297.       10593414.
       3590363.5       10593413.        3590399.       10593426.
       3590457.5       10593407.       3590522.5       10593337.
       3590538.5       10593305.       3590547.5       10593257.
      3590586.75       10593209.      3590673.75       10593182.
        3590717.       10593144.       3590758.5       10593141.
       3590794.5       10593125.      3590893.75       10593047.
        3590907.       10592995.      3590925.75       10592959.
      3590997.75       10592912.      3591028.75       10592929.

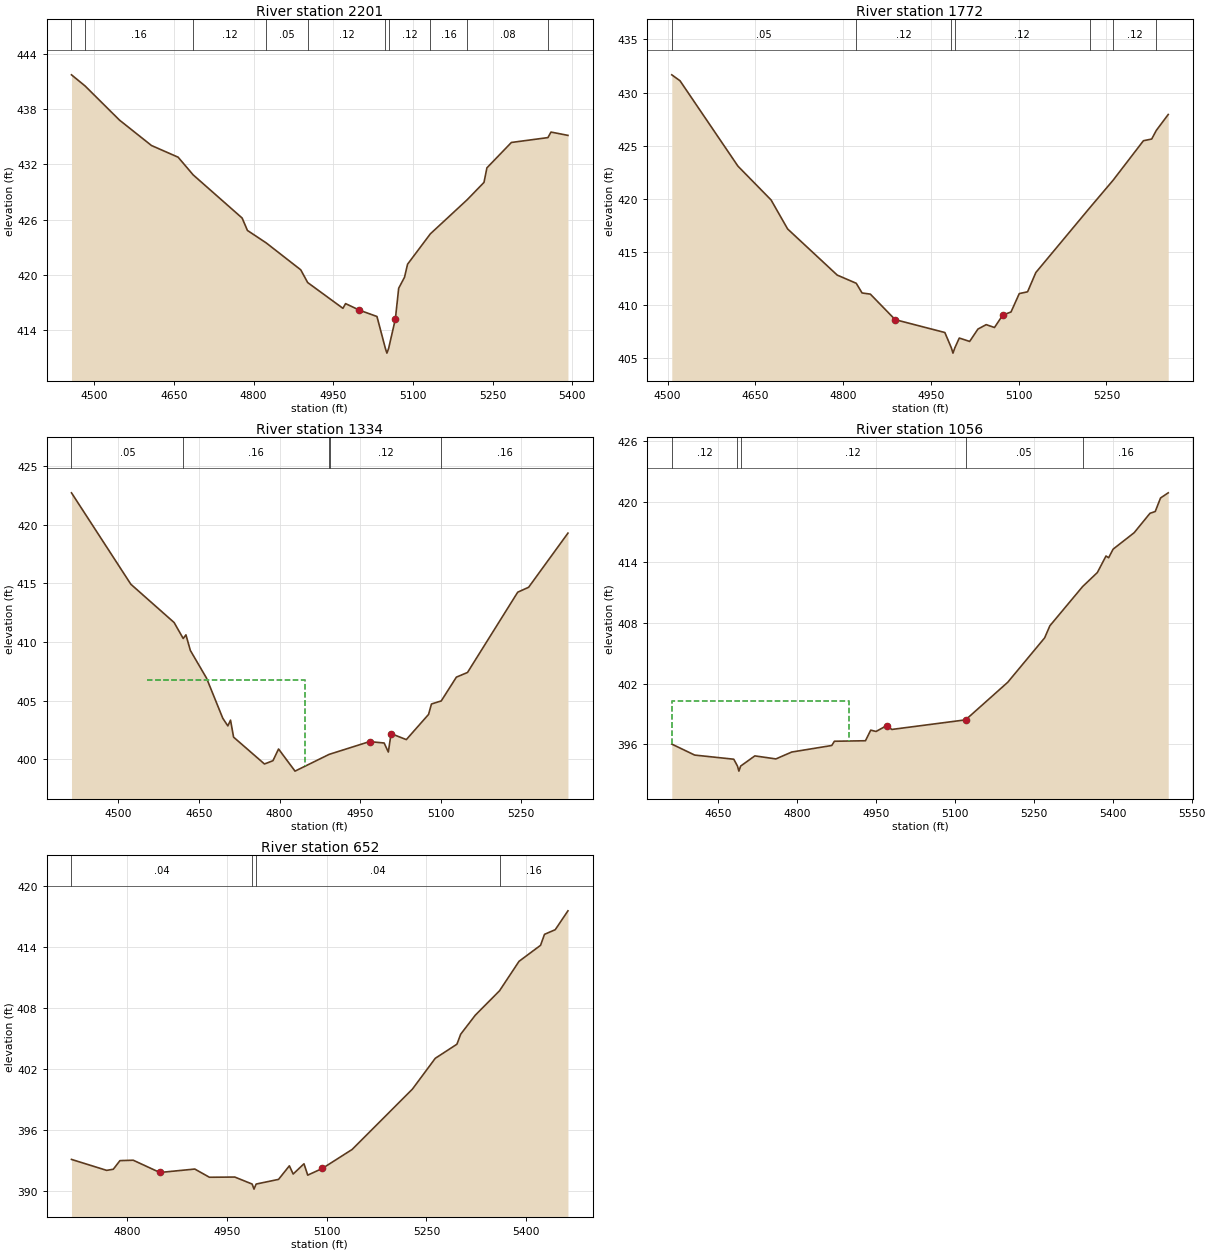
Type RM Length L Ch R = 1 ,2201    ,429,429,429
BEGIN DESCRIPTION:
UNT 029 IN UKCR 3.0
END DESCRIPTION:
XS GIS Cut Line= 3
      3589149.57     10592560.19      3589720.18     10592510.15
      3590049.65     10592360.17
#Sta/Elev= 30
    4457  441.73  4482.6  440.52  4547.4  436.81  4607.6  434.05  4657.8  432.78
  4686.1  430.86  4778.3  426.17  4788.3  424.82  4823.6  423.47  4888.7  420.54
  4901.7  419.16  4968.1  416.36  4973.1  416.87  4999.1  416.16  5032.2  415.47
  5048.1  411.99  5050.9  411.49  5054.1  411.99  5066.8  415.18  5073.1  418.54
  5084.1  419.74  5089.8  421.15  5132.7  424.45  5202.3  428.17  5233.7  430.04
  5239.2  431.62  5285.3  434.38  5354.1  434.91  5359.9  435.51  5391.8  435.15
#Mann= 10 ,-1 , 0
    4457     .05       0  4482.6     .16       0  4686.1     .12       0
  4823.6     .05       0  4901.7     .12       0  5048.1     .07       0
  5054.1     .12       0  5132.7     .16       0  5202.3     .08       0
  5354.1      .1       0
Bank Sta=4999.1,5066.8
XS Rating Curve= 0 ,0
Exp/Cntr=0.3,0.1

Type RM Length L Ch R = 1 ,1772    ,438,438,438
BEGIN DESCRIPTION:
UNT 029 IN UKCR 2.0
END DESCRIPTION:
XS GIS Cut Line= 3
      3589499.63     10593260.17      3589849.61     10592910.19
      3590099.61     10592660.19
#Sta/Elev= 30
  4507.2  431.67  4521.3  431.11  4620.3  423.08  4676.9   419.9  4705.2  417.17
    4790  412.83  4822.5  412.06  4832.4  411.15  4846.6  411.04    4889  408.64
  4973.9  407.43    4985  405.99  4987.8  405.49    4991  405.99  4998.6  406.91
  5016.3  406.59  5030.4  407.75  5044.6  408.17  5058.7   407.9  5072.9  409.07
    5087  409.36  5101.1  411.09  5115.3  411.26  5129.4  413.07  5221.7  419.17
  5261.4  421.75  5313.3  425.47  5327.4  425.63  5335.3  426.44  5355.7  427.94
#Mann= 7 ,-1 , 0
  4507.2     .05       0  4822.5     .12       0    4985     .07       0
    4991     .12       0  5221.7     .16       0  5261.4     .12       0
  5335.3     .16       0
Bank Sta=4889,5072.9
XS Rating Curve= 0 ,0
Exp/Cntr=0.3,0.1

Type RM Length L Ch R = 1 ,1334    ,278,278,278
BEGIN DESCRIPTION:
Mapping XS e56a28e4
END DESCRIPTION:
XS GIS Cut Line= 3
      3589639.83     10593459.71      3589994.02     10593418.04
      3590139.86     10592869.43
#Sta/Elev= 30
  4412.7  422.73  4523.2  414.93  4603.8  411.66  4620.7   410.3  4625.8  410.61
    4634  409.28  4664.2  406.91  4694.4  403.49  4703.8  402.84  4708.8  403.33
  4714.5  401.88    4772  399.59  4787.8  399.87  4798.2  400.87  4828.9  398.98
  4892.4  400.41  4894.5  400.44  4967.6   401.5  4994.8  401.38  5002.6  400.61
  5007.7  402.18  5036.1  401.67  5077.5  403.82  5082.9  404.71  5101.1  404.97
  5129.3     407    5150   407.4  5243.5  414.25  5263.8  414.67    5337  419.29
#Mann= 5 ,-1 , 0
  4412.7     .05       0  4620.7     .16       0  4892.4     .05       0
  4894.5     .12       0  5101.1     .16       0
#XS Ineff= 1 ,-1
 4552.85 4847.73406.7875
Permanent Ineff=
       F
Bank Sta=4967.6,5007.7
XS Rating Curve= 0 ,0
Exp/Cntr=0.3,0.1

Type RM Length L Ch R = 1 ,1056    ,404,404,404
BEGIN DESCRIPTION:
Mapping XS 2dafbf35
END DESCRIPTION:
XS GIS Cut Line= 2
      3590266.31     10593797.86      3590230.13     10592855.55
#Sta/Elev= 30
  4562.5     396    4606  394.91  4680.3   394.5  4687.3  393.82    4690  393.32
  4693.3  393.82  4720.3  394.83  4760.3  394.53  4790.3  395.21  4866.4  395.86
  4871.4  396.28  4930.4  396.33  4940.4  397.38  4950.5  397.25  4970.5  397.82
  4980.5  397.45  5120.6   398.4  5200.6  402.12  5270.7  406.52  5280.7  407.72
  5342.8   411.6  5370.8  412.99  5387.3  414.63  5392.3  414.46  5400.8  415.31
  5440.8  416.94  5470.8  418.86  5480.8  419.04  5490.9  420.38  5505.5  420.89
#Mann= 5 ,-1 , 0
  4562.5     .12       0  4687.3     .03       0  4693.3     .12       0
  5120.6     .05       0  5342.8     .16       0
#XS Ineff= 1 ,-1
    4475 4899.78400.2902
Permanent Ineff=
       F
Bank Sta=4970.5,5120.6
XS Rating Curve= 0 ,0
Exp/Cntr=0.3,0.1

Type RM Length L Ch R = 1 ,652     ,0,0,0
BEGIN DESCRIPTION:
UNT 029 IN UKCR 1.0
END DESCRIPTION:
XS GIS Cut Line= 3
      3590598.19     10593543.08      3590598.19     10593369.43
      3590328.06     10592863.81
#Sta/Elev= 30
    4716  393.08  4768.9     392  4778.9  392.11  4788.9  392.96  4808.9     393
  4848.9  391.79  4901.5  392.13  4923.5  391.32  4961.7  391.34  4987.8  390.65
  4990.6  390.15  4993.8  390.65  5027.5  391.11  5043.8  392.45  5049.5  391.64
  5065.8  392.65  5071.4  391.53  5093.4  392.19  5138.2  394.06  5228.9  400.01
  5263.3  403.05  5295.9  404.44  5301.5  405.42  5323.5   407.3    5360  409.71
  5389.3  412.61  5421.7  414.19  5427.6  415.27  5443.8  415.73  5462.9  417.59
#Mann= 4 ,-1 , 0
    4716     .04       0  4987.8     .03       0  4993.8     .04       0
    5360     .16       0
Bank Sta=4848.9,5093.4
XS Rating Curve= 0 ,0
Exp/Cntr=0.3,0.1

Chan Stop Cuts=-1
Use User Specified Reach Order=0
Composite Channel Slope=5