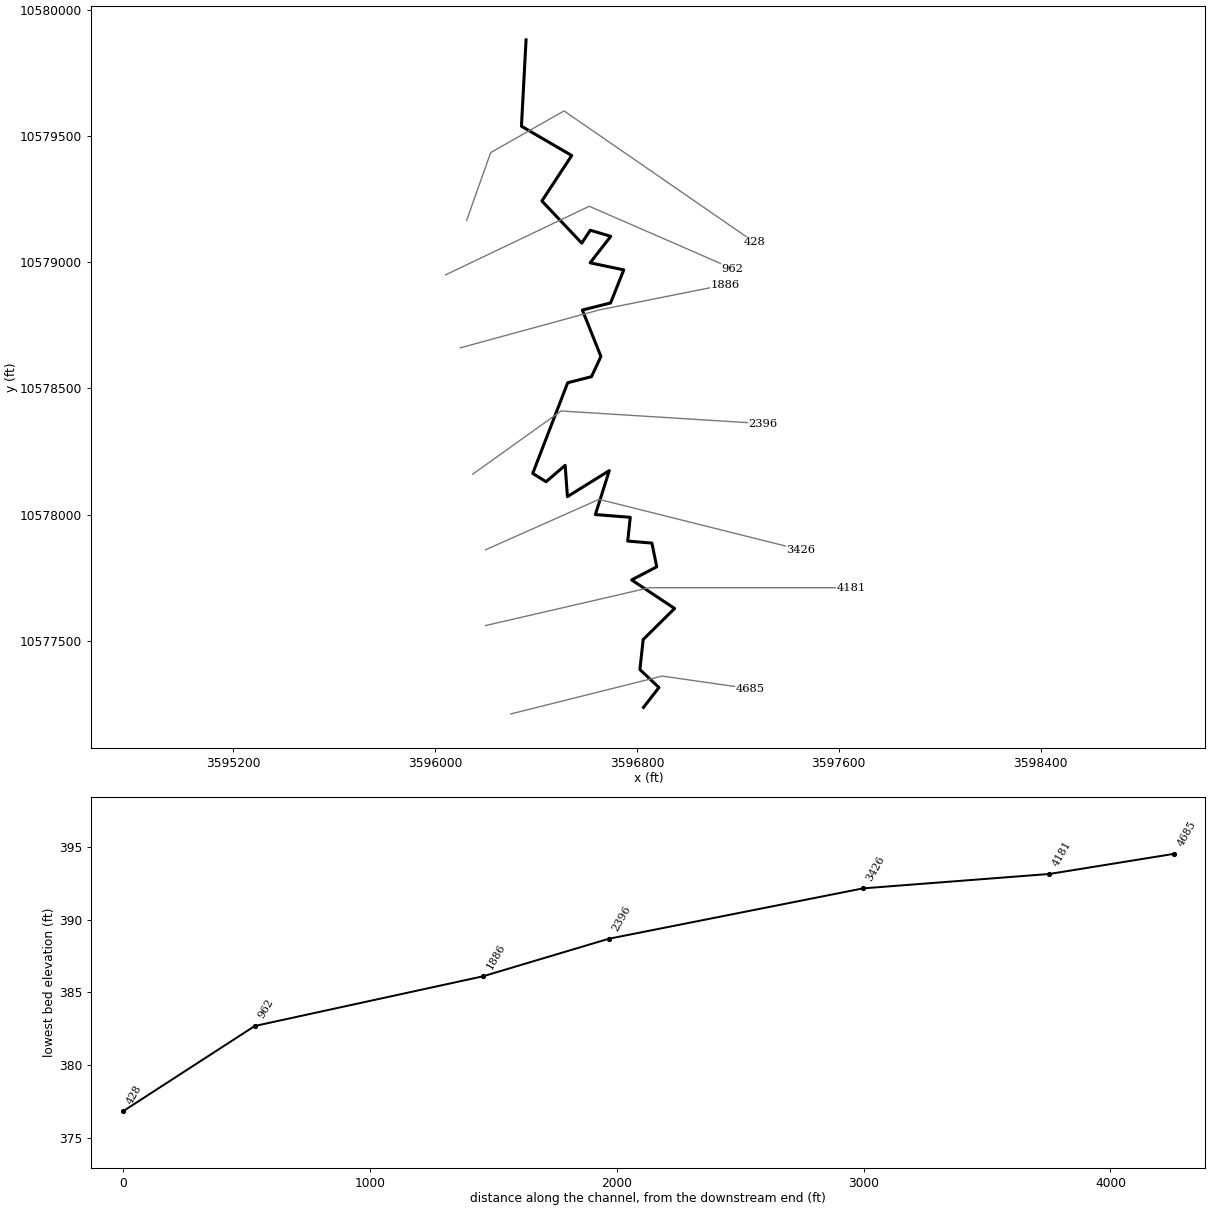
--- UNT 032 IN UKCR.prj (project) ---

Proj Title=UNT 032 IN UKCR Base Level Engineering
Current Plan=p01
Default Exp/Contr=0.3,0.1
English Units
Geom File=g01
Flow File=f01
Plan File=p01
BEGIN DESCRIPTION:
UNT 032 IN UKCR
END DESCRIPTION:

--- UNT 032 IN UKCR.p01 (plan) ---

Plan Title=Multiple Run
Short Identifier=Multiple
Geom File=g01
Flow File=f01
Subcritical Flow
K Sum by GR= 0
Std Step Tol= 0.01
Critical Tol= 0.01
Num of Std Step Trials= 20
Max Error Tol= 0.3
Flow Tol Ratio= 0.001
Split Flow NTrial= 30
Split Flow Tol= 0.02
Split Flow Ratio= 0.02
Log Output Level= 0
Friction Slope Method= 1
Unsteady Friction Slope Method= 2
Unsteady Bridges Friction Slope Method= 1
Parabolic Critical Depth
Global Vel Dist=  1 , 1 , 1
Global Log Level= 0
CheckData=True
Encroach Param= -1, 0, 0, 0
BEGIN DESCRIPTION:
Multiple Run
END DESCRIPTION:

--- UNT 032 IN UKCR.f01 (steady flow) ---

Flow Title=Multiple
Number of Profiles=7
Profile Names=10-year,25-year,50-year,1pct_min,100-year,1pct_plu,500-year
River Rch & RM= UNT 032 IN UKCR,Reach-1,4685
    1226    1704    2104    1896    2565    3468    3796
Boundary for River Rch & Prof#=UNT 032 IN UKCR,Reach-1,1
Up Type=0
Dn Type=3
Dn Slope=0.005
Boundary for River Rch & Prof#=UNT 032 IN UKCR,Reach-1,2
Up Type=0
Dn Type=3
Dn Slope=0.005
Boundary for River Rch & Prof#=UNT 032 IN UKCR,Reach-1,3
Up Type=0
Dn Type=3
Dn Slope=0.005
Boundary for River Rch & Prof#=UNT 032 IN UKCR,Reach-1,4
Up Type=0
Dn Type=3
Dn Slope=0.005
Boundary for River Rch & Prof#=UNT 032 IN UKCR,Reach-1,5
Up Type=0
Dn Type=3
Dn Slope=0.005
Boundary for River Rch & Prof#=UNT 032 IN UKCR,Reach-1,6
Up Type=0
Dn Type=3
Dn Slope=0.005
Boundary for River Rch & Prof#=UNT 032 IN UKCR,Reach-1,7
Up Type=0
Dn Type=3
Dn Slope=0.005

--- UNT 032 IN UKCR.g01 (geometry) ---

Geom Title=Existing Conditions

River Reach=UNT 032 IN UKCR,Reach-1
Reach XY= 30
      3596826.04     10577236.21      3596887.25     10577315.00
      3596811.75     10577386.00      3596824.75     10577505.00
      3596949.25     10577628.00      3596779.00     10577741.00
      3596878.50     10577793.00      3596859.25     10577887.00
      3596763.50     10577895.00      3596773.50     10577989.00
      3596635.25     10578000.00      3596690.50     10578174.00
      3596524.50     10578071.00      3596515.50     10578195.00
      3596439.75     10578130.00      3596387.00     10578163.00
      3596525.50     10578522.00      3596619.75     10578546.00
      3596657.25     10578626.00      3596583.75     10578810.00
      3596695.50     10578838.00      3596747.75     10578969.00
      3596614.50     10578997.00      3596696.25     10579102.00
      3596615.00     10579126.00      3596581.25     10579075.00
      3596423.25     10579242.00      3596541.50     10579422.00
      3596342.25     10579538.00      3596360.50     10579880.00

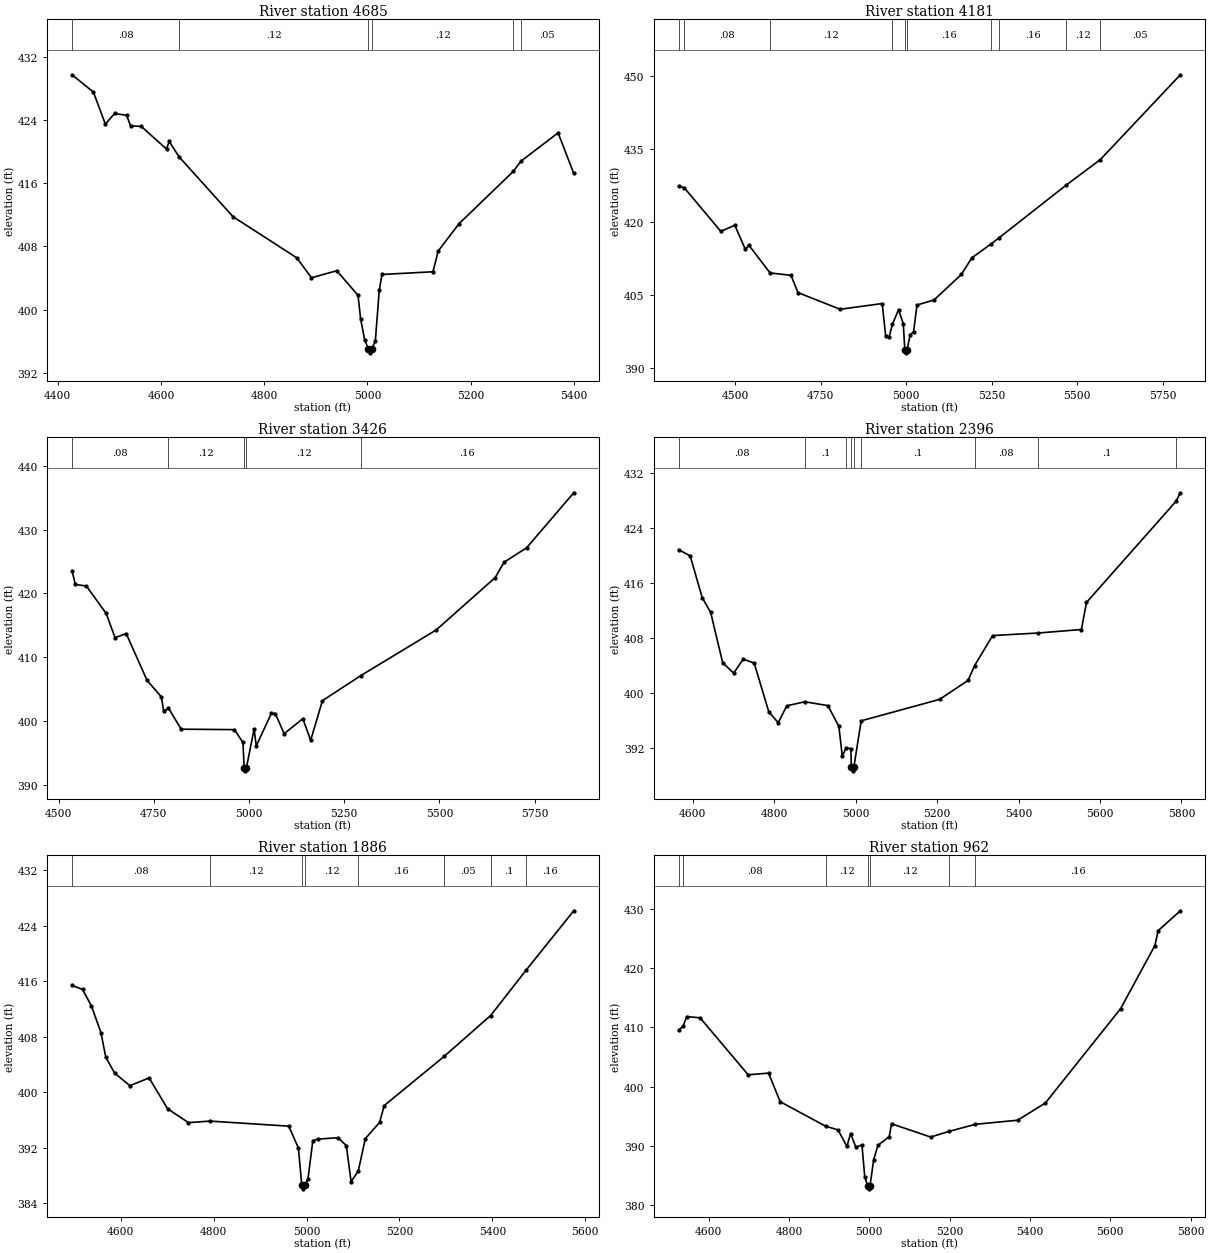
Type RM Length L Ch R = 1,4685,504,504,504
BEGIN DESCRIPTION:
UNT 032 IN UKCR 7.0
END DESCRIPTION:
XS GIS Cut Line= 3
      3596299.57     10577210.18      3596899.61     10577360.19
      3597249.65     10577310.18
#Sta/Elev= 30
  4427.7  429.71  4469.0  427.52  4492.2  423.47  4510.2  424.81  4533.4  424.58
  4541.1  423.24  4561.7  423.18  4610.7  420.31  4615.9  421.28  4635.0  419.33
  4739.6  411.75  4863.2  406.54  4891.6  404.02  4940.6  404.91  4981.8  401.80
  4986.9  398.80  4994.7  396.14  5002.0  395.02  5004.7  394.52  5008.0  395.02
  5015.3  395.98  5023.0  402.46  5028.2  404.44  5127.0  404.78  5137.1  407.40
  5177.5  410.86  5282.8  417.49  5297.4  418.77  5369.5  422.36  5399.8  417.23
#Mann=6,-1,0
  4427.7    0.08       0  4635.0    0.12       0  5002.0    0.07       0
  5008.0    0.12       0  5282.8    0.16       0  5297.4    0.05       0
Bank Sta=5002,5008
Exp/Cntr=0.3,0.1

Type RM Length L Ch R = 1,4181,755,755,755
BEGIN DESCRIPTION:
UNT 032 IN UKCR 6.0
END DESCRIPTION:
XS GIS Cut Line= 3
      3596199.65     10577560.20      3596849.61     10577710.19
      3597649.56     10577710.19
#Sta/Elev= 30
  4334.5  427.49  4351.2  427.07  4457.6  418.13  4498.7  419.38  4529.5  414.42
  4539.7  415.29  4601.9  409.57  4662.9  409.09  4683.4  405.53  4806.6  402.10
  4929.7  403.28  4940.0  396.53  4950.2  396.45  4959.6  399.03  4977.6  402.02
  4991.3  399.16  4996.0  393.64  4998.7  393.14  5002.0  393.64  5011.5  396.83
  5021.5  397.50  5031.5  402.97  5081.5  404.03  5161.5  409.28  5191.5  412.66
  5248.9  415.58  5270.7  416.76  5468.5  427.68  5567.4  432.87  5801.5  450.33
#Mann=10,-1,0
  4334.5     0.1       0  4351.2    0.08       0  4601.9    0.12       0
  4959.6    0.16       0  4996.0    0.07       0  5002.0    0.16       0
  5248.9    0.12       0  5270.7    0.16       0  5468.5    0.12       0
  5567.4    0.05       0
Bank Sta=4996,5002
Exp/Cntr=0.3,0.1

Type RM Length L Ch R = 1,3426,1030,1030,1030
BEGIN DESCRIPTION:
UNT 032 IN UKCR 5.0
END DESCRIPTION:
XS GIS Cut Line= 3
      3596199.65     10577860.21      3596649.61     10578060.19
      3597449.59     10577860.19
#Sta/Elev= 30
  4535.6  423.54  4544.4  421.41  4573.2  421.17  4625.2  416.86  4648.4  413.06
  4677.8  413.70  4732.5  406.34  4770.1  403.76  4776.3  401.50  4788.7  401.99
  4822.1  398.69  4961.7  398.62  4984.2  396.60  4987.4  392.65  4990.1  392.15
  4993.4  392.65  5013.6  398.74  5019.1  396.06  5058.9  401.19  5069.2  401.14
  5092.4  397.98  5141.4  400.34  5162.0  396.95  5192.9  403.17  5293.8  407.11
  5491.8  414.28  5646.5  422.50  5669.7  424.91  5728.9  427.17  5852.6  435.81
#Mann=5,-1,0
  4535.6    0.08       0  4788.7    0.12       0  4987.4    0.07       0
  4993.4    0.12       0  5293.8    0.16       0
Bank Sta=4987.4,4993.4
Exp/Cntr=0.3,0.1

Type RM Length L Ch R = 1,2396,510,510,510
BEGIN DESCRIPTION:
UNT 032 IN UKCR 4.0
END DESCRIPTION:
XS GIS Cut Line= 3
      3596149.63     10578160.21      3596499.61     10578410.19
      3597299.56     10578360.19
#Sta/Elev= 30
  4565.6  420.84  4593.8  419.96  4623.3  413.89  4644.2  411.72  4673.7  404.40
  4700.8  402.90  4724.1  404.93  4751.1  404.35  4786.8  397.28  4810.1  395.68
  4831.0  398.15  4875.4  398.73  4931.8  398.18  4958.8  395.18  4967.4  390.81
  4976.7  392.03  4988.3  391.91  4989.6  389.19  4992.4  388.69  4995.6  389.19
  5013.7  395.96  5206.1  399.08  5276.2  401.84  5292.0  403.98  5336.4  408.36
  5448.0  408.73  5554.3  409.24  5566.8  413.17  5786.6  427.88  5797.2  429.12
#Mann=9,-1,0
  4565.6    0.08       0  4875.4     0.1       0  4976.7    0.12       0
  4989.6    0.07       0  4995.6    0.12       0  5013.7     0.1       0
  5292.0    0.08       0  5448.0     0.1       0  5786.6    0.16       0
Bank Sta=4989.6,4995.6
Exp/Cntr=0.3,0.1

Type RM Length L Ch R = 1,1886,924,924,924
BEGIN DESCRIPTION:
UNT 032 IN UKCR 3.0
END DESCRIPTION:
XS GIS Cut Line= 3
      3596099.58     10578660.18      3596649.61     10578810.19
      3597149.59     10578910.18
#Sta/Elev= 30
  4495.2  415.41  4517.7  414.84  4536.7  412.49  4557.4  408.62  4567.8  405.07
  4586.8  402.79  4619.6  400.97  4661.1  402.09  4700.8  397.65  4745.7  395.65
  4792.2  395.87  4961.7  395.14  4982.4  392.00  4989.8  386.61  4992.5  386.11
  4995.8  386.61  5003.1  387.55  5013.5  393.05  5023.9  393.27  5067.9  393.48
  5085.7  392.33  5095.9  387.13  5111.4  388.70  5126.5  393.34  5157.1  395.67
  5167.3  398.11  5296.2  405.19  5396.3  411.08  5473.1  417.65  5575.2  426.17
#Mann=8,-1,0
  4495.2    0.08       0  4792.2    0.12       0  4989.8    0.07       0
  4995.8    0.12       0  5111.4    0.16       0  5296.2    0.05       0
  5396.3     0.1       0  5473.1    0.16       0
Bank Sta=4989.8,4995.8
Exp/Cntr=0.3,0.1

Type RM Length L Ch R = 1,962,534,534,534
BEGIN DESCRIPTION:
UNT 032 IN UKCR 2.0
END DESCRIPTION:
XS GIS Cut Line= 3
      3596041.44     10578949.28      3596610.92     10579220.99
      3597177.71     10578974.37
#Sta/Elev= 30
  4525.5  409.53  4536.9  410.29  4545.6  411.85  4578.9  411.64  4698.5  402.00
  4749.4  402.28  4778.3  397.44  4891.4  393.30  4922.3  392.67  4944.5  389.87
  4953.6  392.06  4966.7  389.75  4981.9  390.13  4988.8  384.75  4996.0  383.20
  4998.8  382.70  5002.0  383.20  5011.0  387.61  5021.7  390.06  5049.9  391.54
  5055.5  393.71  5153.0  391.46  5198.6  392.42  5264.2  393.62  5369.6  394.31
  5438.6  397.23  5625.8  413.18  5711.2  423.86  5719.6  426.40  5774.6  429.75
#Mann=7,-1,0
  4525.5     0.1       0  4536.9    0.08       0  4891.4    0.12       0
  4996.0    0.07       0  5002.0    0.12       0  5198.6    0.05       0
  5264.2    0.16       0
Bank Sta=4996,5002
Exp/Cntr=0.3,0.1

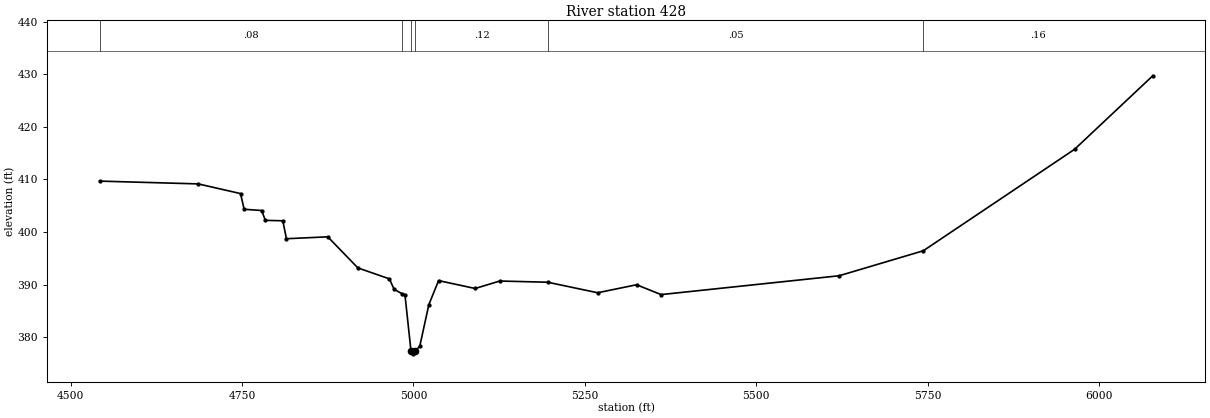
Type RM Length L Ch R = 1,428,0,0,0
BEGIN DESCRIPTION:
UNT 032 IN UKCR 1.0
END DESCRIPTION:
XS GIS Cut Line= 4
      3596124.81     10579164.58      3596220.29     10579433.67
      3596511.09     10579598.60      3597265.45     10579078.35
#Sta/Elev= 30
  4542.3  409.67  4686.1  409.14  4747.8  407.30  4753.1  404.32  4778.7  404.08
  4784.0  402.21  4809.5  402.13  4814.8  398.72  4875.1  399.08  4919.0  393.17
  4965.0  391.09  4971.8  389.11  4983.6  388.25  4987.7  388.05  4996.5  377.34
  4999.2  376.84  5002.5  377.34  5009.3  378.30  5022.5  386.18  5036.7  390.76
  5090.1  389.26  5125.9  390.68  5196.0  390.45  5268.7  388.45  5325.5  389.97
  5361.3  388.10  5621.0  391.68  5743.8  396.43  5964.5  415.72  6078.5  429.69
#Mann=6,-1,0
  4542.3    0.08       0  4983.6    0.12       0  4996.5    0.07       0
  5002.5    0.12       0  5196.0    0.05       0  5743.8    0.16       0
Bank Sta=4996.5,5002.5
Exp/Cntr=0.3,0.1

Chan Stop Cuts=-1