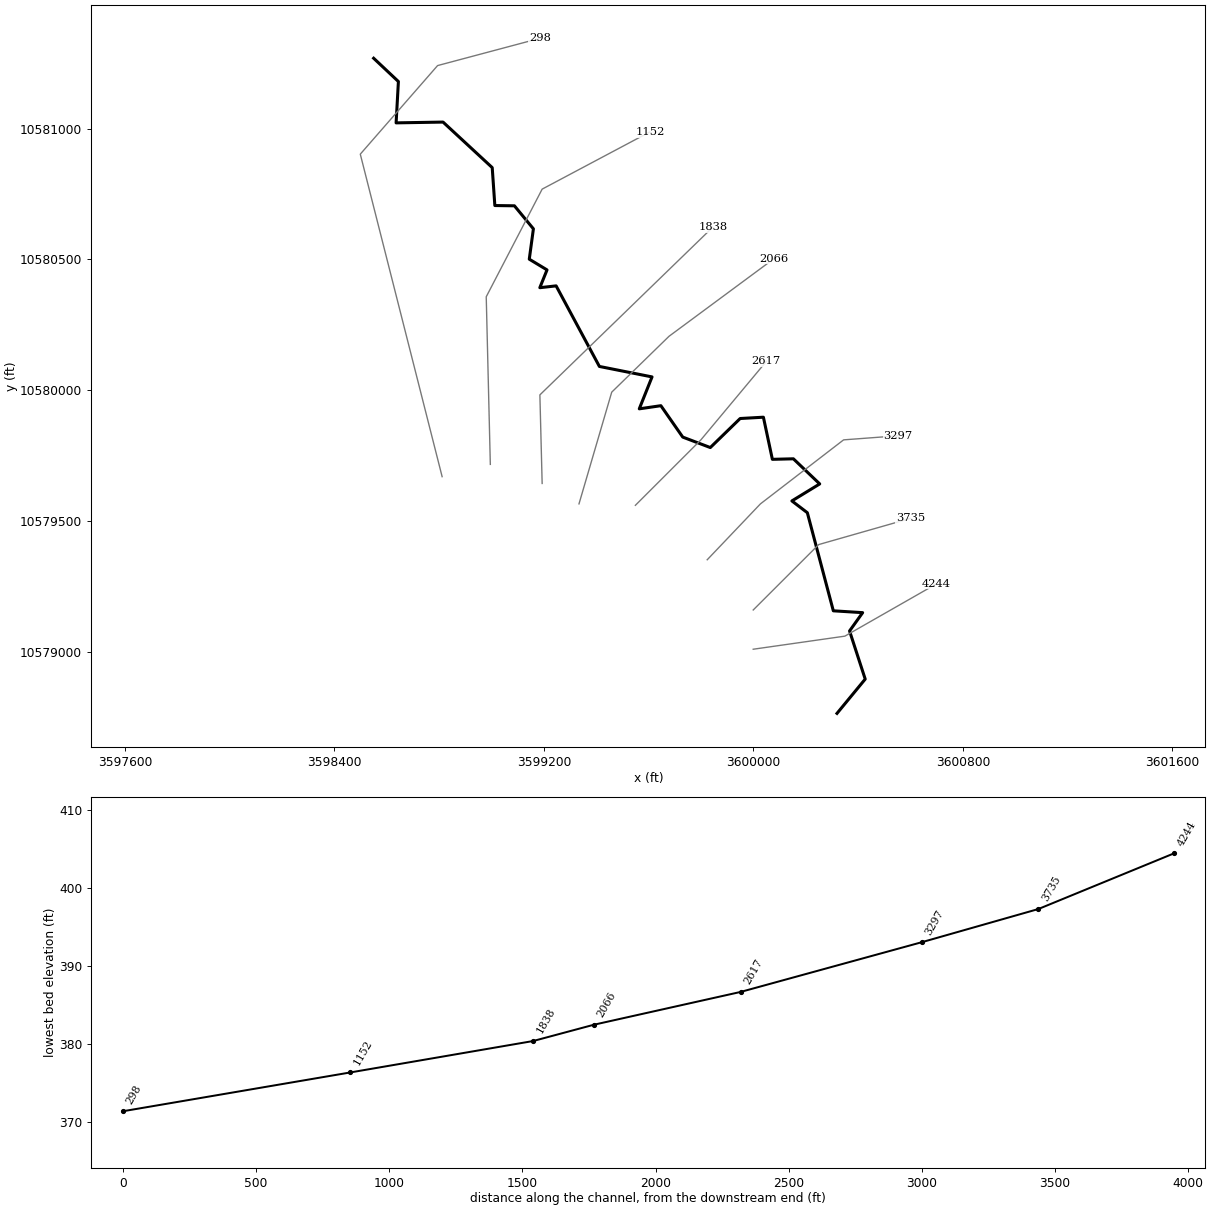
--- UNT 033 IN UKCR.prj (project) ---

Proj Title=UNT 033 IN UKCR Base Level Engineering
Current Plan=p01
Default Exp/Contr=0.3,0.1
English Units
Geom File=g01
Flow File=f01
Plan File=p01
BEGIN DESCRIPTION:
UNT 033 IN UKCR
END DESCRIPTION:

--- UNT 033 IN UKCR.p01 (plan) ---

Plan Title=Multiple Run
Short Identifier=Multiple
Geom File=g01
Flow File=f01
Subcritical Flow
K Sum by GR= 0
Std Step Tol= 0.01
Critical Tol= 0.01
Num of Std Step Trials= 20
Max Error Tol= 0.3
Flow Tol Ratio= 0.001
Split Flow NTrial= 30
Split Flow Tol= 0.02
Split Flow Ratio= 0.02
Log Output Level= 0
Friction Slope Method= 1
Unsteady Friction Slope Method= 2
Unsteady Bridges Friction Slope Method= 1
Parabolic Critical Depth
Global Vel Dist=  1 , 1 , 1
Global Log Level= 0
CheckData=True
Encroach Param= -1, 0, 0, 0
BEGIN DESCRIPTION:
Multiple Run
END DESCRIPTION:

--- UNT 033 IN UKCR.f01 (steady flow) ---

Flow Title=Multiple
Number of Profiles=7
Profile Names=10-year,25-year,50-year,1pct_min,100-year,1pct_plu,500-year
River Rch & RM= UNT 033 IN UKCR,Reach-1,4244
     559     741     886     777    1051    1421    1467
Boundary for River Rch & Prof#=UNT 033 IN UKCR,Reach-1,1
Up Type=0
Dn Type=3
Dn Slope=0.005
Boundary for River Rch & Prof#=UNT 033 IN UKCR,Reach-1,2
Up Type=0
Dn Type=3
Dn Slope=0.005
Boundary for River Rch & Prof#=UNT 033 IN UKCR,Reach-1,3
Up Type=0
Dn Type=3
Dn Slope=0.005
Boundary for River Rch & Prof#=UNT 033 IN UKCR,Reach-1,4
Up Type=0
Dn Type=3
Dn Slope=0.005
Boundary for River Rch & Prof#=UNT 033 IN UKCR,Reach-1,5
Up Type=0
Dn Type=3
Dn Slope=0.005
Boundary for River Rch & Prof#=UNT 033 IN UKCR,Reach-1,6
Up Type=0
Dn Type=3
Dn Slope=0.005
Boundary for River Rch & Prof#=UNT 033 IN UKCR,Reach-1,7
Up Type=0
Dn Type=3
Dn Slope=0.005

--- UNT 033 IN UKCR.g01 (geometry) ---

Geom Title=Existing Conditions

River Reach=UNT 033 IN UKCR,Reach-1
Reach XY= 30
      3600319.50     10578765.00      3600427.25     10578896.00
      3600367.50     10579080.00      3600417.50     10579150.00
      3600305.50     10579157.00      3600206.25     10579532.00
      3600147.25     10579577.00      3600253.50     10579642.00
      3600153.00     10579738.00      3600072.75     10579736.00
      3600038.50     10579897.00      3599949.75     10579892.00
      3599835.75     10579781.00      3599730.50     10579821.00
      3599647.00     10579941.00      3599564.50     10579929.00
      3599613.25     10580051.00      3599412.25     10580091.00
      3599247.00     10580399.00      3599184.75     10580392.00
      3599212.25     10580460.00      3599144.50     10580501.00
      3599160.25     10580617.00      3599087.75     10580705.00
      3599013.00     10580706.00      3599003.00     10580851.00
      3598815.25     10581025.00      3598636.00     10581022.00
      3598644.75     10581180.00      3598550.25     10581269.00

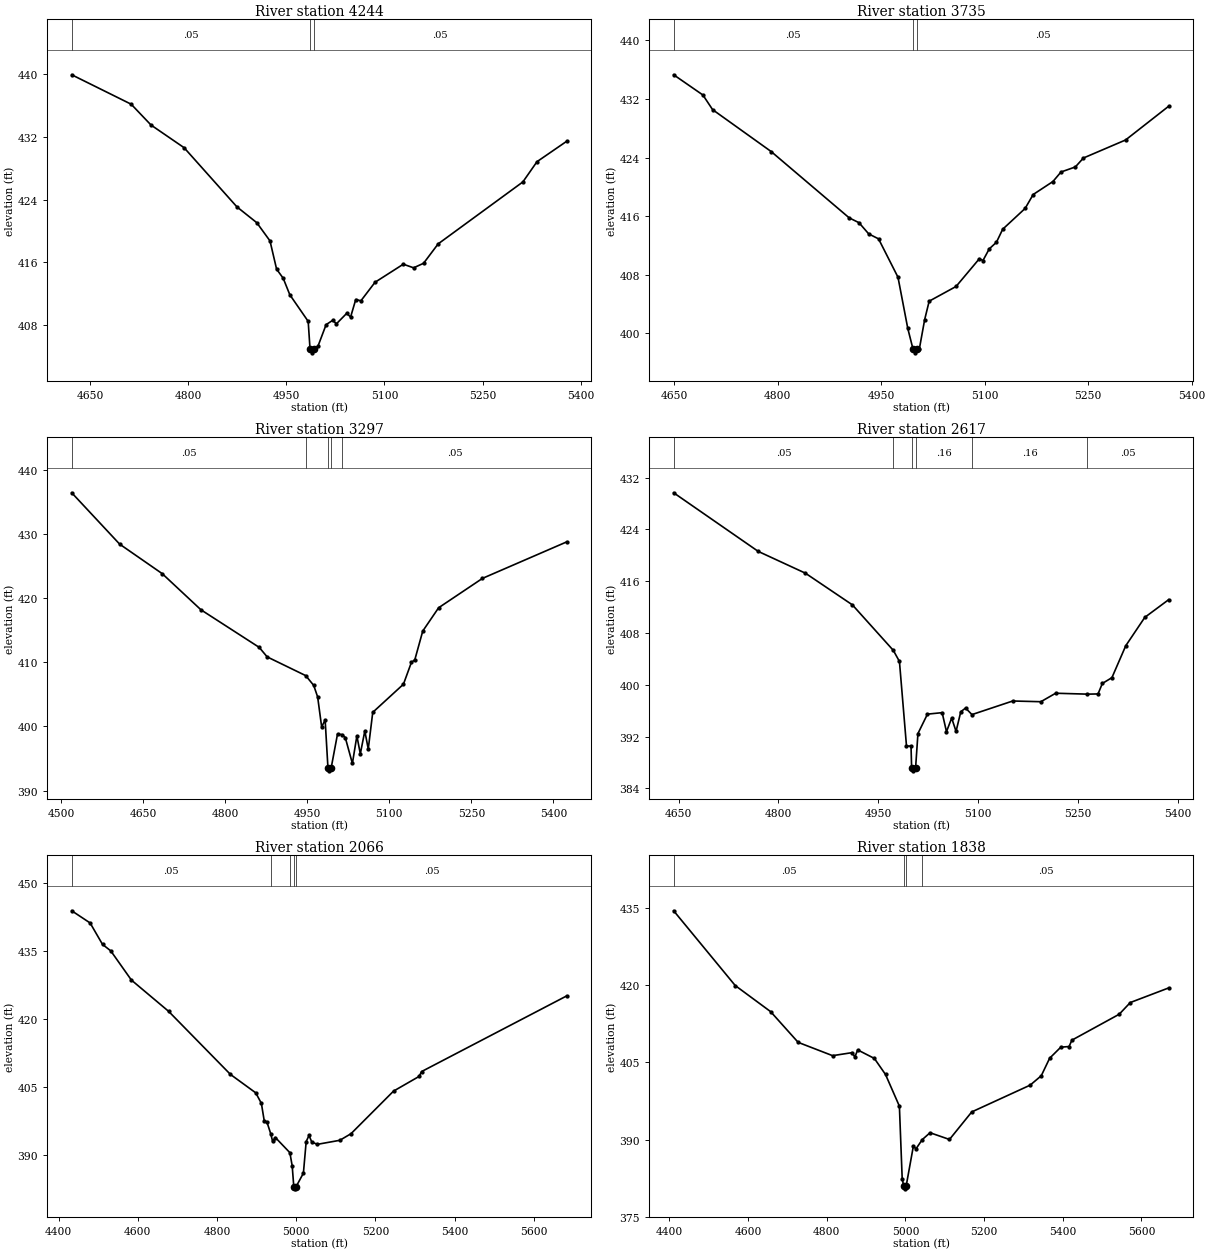
Type RM Length L Ch R = 1,4244,509,509,509
BEGIN DESCRIPTION:
UNT 033 IN UKCR 8.0
END DESCRIPTION:
XS GIS Cut Line= 3
      3599999.58     10579010.18      3600349.61     10579060.19
      3600699.62     10579260.19
#Sta/Elev= 30
  4621.9  439.91  4712.8  436.16  4743.1  433.51  4793.7  430.62  4874.5  423.08
  4904.8  421.07  4925.0  418.75  4935.1  415.15  4945.2  413.99  4955.3  411.89
  4983.4  408.50  4986.2  404.99  4988.9  404.49  4992.2  404.99  4998.5  405.37
  5010.8  408.08  5020.8  408.63  5026.6  408.19  5042.4  409.53  5048.2  409.04
  5056.1  411.28  5064.0  411.12  5085.6  413.48  5128.8  415.78  5144.6  415.32
  5159.8  415.90  5182.1  418.37  5311.6  426.26  5333.2  428.84  5378.6  431.44
#Mann=3,-1,0
  4621.9    0.05       0  4986.2    0.03       0  4992.2    0.05       0
Bank Sta=4986.2,4992.2
Exp/Cntr=0.3,0.1

Type RM Length L Ch R = 1,3735,438,438,438
BEGIN DESCRIPTION:
UNT 033 IN UKCR 7.0
END DESCRIPTION:
XS GIS Cut Line= 3
      3599999.63     10579160.21      3600249.61     10579410.19
      3600599.58     10579510.18
#Sta/Elev= 30
  4649.0  435.30  4691.4  432.54  4705.5  430.54  4790.4  424.82  4903.5  415.77
  4917.7  415.11  4931.8  413.58  4946.0  412.91  4974.2  407.67  4988.4  400.68
  4996.0  397.85  4998.7  397.35  5002.0  397.85  5005.1  397.85  5012.9  401.90
  5019.4  404.40  5058.4  406.41  5092.2  410.20  5097.4  409.95  5106.5  411.54
  5116.9  412.44  5126.0  414.22  5158.5  417.06  5170.2  418.96  5198.8  420.73
  5210.5  422.03  5231.3  422.72  5243.0  423.94  5304.1  426.40  5366.5  431.00
#Mann=3,-1,0
  4649.0    0.05       0  4996.0    0.03       0  5002.0    0.05       0
Bank Sta=4996,5002
Exp/Cntr=0.3,0.1

Type RM Length L Ch R = 1,3297,680,680,680
BEGIN DESCRIPTION:
UNT 033 IN UKCR 6.0
END DESCRIPTION:
XS GIS Cut Line= 4
      3599823.88     10579352.07      3600027.01     10579565.61
      3600344.72     10579810.40      3600553.03     10579826.03
#Sta/Elev= 30
  4519.6  436.40  4607.2  428.40  4684.9  423.81  4755.7  418.18  4862.3  412.32
  4876.8  410.84  4947.3  407.92  4961.9  406.40  4969.1  404.60  4976.4  399.94
  4982.8  401.00  4987.9  393.59  4990.7  393.09  4993.9  393.59  5005.4  398.82
  5013.9  398.73  5019.6  398.27  5032.6  394.24  5040.8  398.53  5047.1  395.74
  5055.3  399.30  5061.6  396.48  5069.8  402.20  5125.9  406.58  5140.4  409.97
  5146.7  410.39  5161.2  414.86  5190.2  418.49  5270.4  423.07  5424.3  428.75
#Mann=5,-1,0
  4519.6    0.05       0  4947.3    0.12       0  4987.9    0.07       0
  4993.9    0.12       0  5013.9    0.05       0
Bank Sta=4987.9,4993.9
Exp/Cntr=0.3,0.1

Type RM Length L Ch R = 1,2617,551,551,551
BEGIN DESCRIPTION:
UNT 033 IN UKCR 5.0
END DESCRIPTION:
XS GIS Cut Line= 3
      3599549.64     10579560.22      3599799.61     10579810.19
      3600049.59     10580110.17
#Sta/Elev= 30
  4642.4  429.67  4769.6  420.61  4840.4  417.25  4911.1  412.35  4972.6  405.32
  4981.8  403.61  4992.4  390.54  4999.2  390.54  5000.1  387.21  5002.8  386.71
  5006.1  387.21  5009.6  392.47  5023.9  395.47  5046.0  395.70  5052.5  392.76
  5060.3  394.86  5066.9  392.81  5074.0  395.84  5081.2  396.41  5090.8  395.40
  5152.1  397.50  5194.4  397.39  5216.6  398.70  5264.3  398.56  5280.3  398.59
  5286.8  400.21  5301.2  401.11  5322.0  406.04  5350.6  410.42  5386.4  413.15
#Mann=6,-1,0
  4642.4    0.05       0  4972.6    0.16       0  5000.1    0.07       0
  5006.1    0.16       0  5090.8    0.16       0  5264.3    0.05       0
Bank Sta=5000.1,5006.1
Exp/Cntr=0.3,0.1

Type RM Length L Ch R = 1,2066,228,228,228
BEGIN DESCRIPTION:
UNT 033 IN UKCR 4.0
END DESCRIPTION:
XS GIS Cut Line= 4
      3599334.31     10579565.64      3599459.30     10579992.70
      3599678.05     10580206.24      3600079.06     10580503.09
#Sta/Elev= 30
  4433.1  443.91  4479.5  441.22  4510.8  436.49  4531.6  435.06  4583.7  428.61
  4677.5  421.72  4833.8  407.77  4897.7  403.70  4911.9  401.38  4919.0  397.58
  4926.0  397.23  4935.4  394.70  4940.2  393.01  4947.3  393.83  4983.8  390.49
  4989.7  387.58  4993.7  383.00  4996.5  382.50  4999.7  383.00  5018.0  385.97
  5025.0  392.94  5032.2  394.29  5039.2  392.82  5053.3  392.33  5109.9  393.22
  5138.2  394.68  5245.5  404.08  5310.1  407.33  5316.4  408.40  5682.7  425.11
#Mann=5,-1,0
  4433.1    0.05       0  4935.4    0.16       0  4983.8    0.05       0
  4993.7    0.03       0  4999.7    0.05       0
Bank Sta=4993.7,4999.7
Exp/Cntr=0.3,0.1

Type RM Length L Ch R = 1,1838,686,686,686
BEGIN DESCRIPTION:
UNT 033 IN UKCR 3.0
END DESCRIPTION:
XS GIS Cut Line= 3
      3599193.67     10579643.77      3599184.99     10579982.28
      3599844.64     10580622.83
#Sta/Elev= 30
  4411.0  434.53  4567.5  419.98  4657.5  414.90  4727.5  408.92  4815.0  406.33
  4864.6  406.92  4871.6  406.07  4878.8  407.45  4921.2  405.79  4949.5  402.67
  4984.8  396.50  4991.9  382.40  4995.9  380.91  4998.7  380.41  5001.9  380.91
  5020.2  388.68  5027.2  388.22  5042.9  389.99  5062.7  391.33  5112.1  390.02
  5168.7  395.38  5317.1  400.59  5345.4  402.42  5366.7  405.83  5395.0  407.98
  5416.1  408.11  5423.3  409.35  5543.5  414.39  5571.7  416.67  5669.1  419.51
#Mann=4,-1,0
  4411.0    0.05       0  4995.9    0.03       0  5001.9    0.05       0
  5042.9    0.05       0
Bank Sta=4995.9,5001.9
Exp/Cntr=0.3,0.1

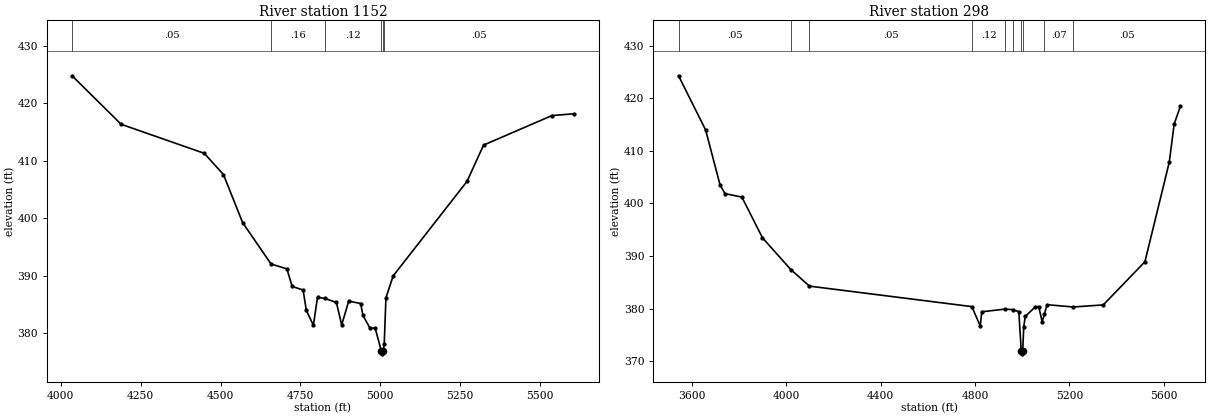
Type RM Length L Ch R = 1,1152,854,854,854
BEGIN DESCRIPTION:
UNT 033 IN UKCR 2.0
END DESCRIPTION:
XS GIS Cut Line= 4
      3598995.76     10579716.67      3598980.13     10580357.28
      3599193.67     10580768.74      3599604.90     10580987.37
#Sta/Elev= 30
  4035.5  424.76  4189.1  416.32  4449.1  411.27  4509.2  407.57  4569.2  399.21
  4658.1  392.01  4707.7  391.16  4724.2  388.10  4758.4  387.49  4768.5  383.94
  4790.6  381.34  4803.5  386.23  4827.2  386.01  4862.6  385.32  4879.1  381.41
  4901.2  385.56  4938.7  385.13  4945.4  383.10  4967.5  380.85  4983.8  380.86
  5003.2  376.88  5005.9  376.38  5009.2  376.88  5012.2  378.06  5017.6  386.11
  5040.1  389.93  5271.2  406.38  5323.1  412.70  5537.2  417.84  5605.6  418.15
#Mann=6,-1,0
  4035.5    0.05       0  4658.1    0.16       0  4827.2    0.12       0
  5003.2    0.07       0  5009.2    0.12       0  5012.2    0.05       0
Bank Sta=5003.2,5009.2
Exp/Cntr=0.3,0.1

Type RM Length L Ch R = 1,298,0,0,0
BEGIN DESCRIPTION:
UNT 033 IN UKCR 1.0
END DESCRIPTION:
XS GIS Cut Line= 4
      3598811.73     10579669.76      3598499.23     10580902.42
      3598794.37     10581240.96      3599184.84     10581345.09
#Sta/Elev= 30
  3544.5  424.29  3659.2  413.99  3720.3  403.53  3741.2  401.88  3812.8  401.21
  3899.9  393.47  4019.8  387.44  4098.8  384.28  4786.7  380.38  4822.1  376.68
  4828.7  379.40  4928.0  379.91  4959.5  379.81  4985.4  379.42  4995.9  371.90
  4998.7  371.40  5001.9  371.90  5006.3  376.56  5012.9  378.52  5055.6  380.36
  5069.9  380.38  5084.1  377.52  5094.2  379.00  5105.1  380.75  5216.1  380.31
  5343.2  380.71  5519.4  388.91  5622.6  407.85  5643.3  415.10  5669.4  418.46
#Mann=10,-1,0
  3544.5    0.05       0  4019.8    0.16       0  4098.8    0.05       0
  4786.7    0.12       0  4928.0    0.16       0  4959.5    0.12       0
  4995.9    0.07       0  5001.9    0.12       0  5094.2    0.07       0
  5216.1    0.05       0
Bank Sta=4995.9,5001.9
Exp/Cntr=0.3,0.1

Chan Stop Cuts=-1