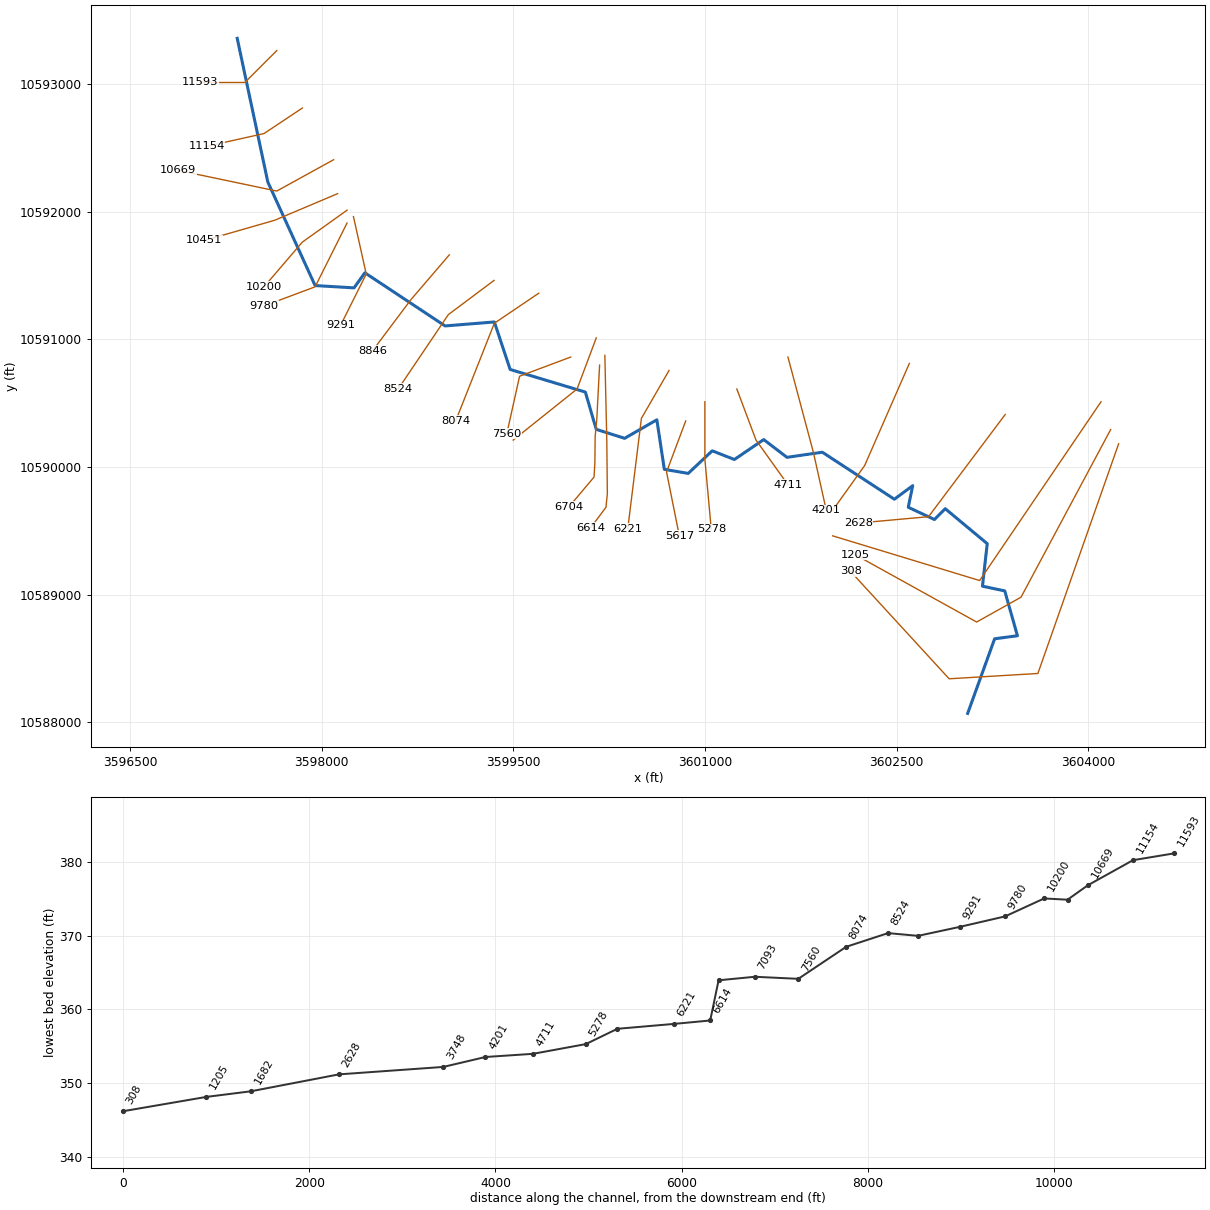
--- UNT 034 IN UKCR.prj (project) ---

Proj Title=UNT 034 IN UKCR Base Level Engineering
Current Plan=p01
Default Exp/Contr=0.3,0.1
English Units
Geom File=g01
Flow File=f01
Plan File=p01
Y Axis Title=Elevation
X Axis Title(PF)=Main Channel Distance
X Axis Title(XS)=Station
BEGIN DESCRIPTION:
UNT 034 IN UKCR
END DESCRIPTION:
DSS Export Rating Curves= 0
DSS Export Rating Curve Sorted= 0
DSS Export Volume Flow Curves= 0
DXF OffsetX= 0
DXF OffsetY= 0
DXF ScaleX= 1
DXF ScaleY= 10

--- UNT 034 IN UKCR.p01 (plan) ---

Plan Title=Multiple Run
Short Identifier=Multiple
Geom File=g01
Flow File=f01
Subcritical Flow
K Sum by GR= 0
Std Step Tol= 0.01
Critical Tol= 0.01
Num of Std Step Trials= 20
Max Error Tol= 0.3
Flow Tol Ratio= 0.001
Split Flow NTrial= 30
Split Flow Tol= 0.02
Split Flow Ratio= 0.02
Log Output Level= 0
Friction Slope Method= 1
Unsteady Friction Slope Method= 2
Unsteady Bridges Friction Slope Method= 1
Parabolic Critical Depth
Global Vel Dist=  1 , 1 , 1
Global Log Level= 0
CheckData=True
Encroach Param= -1, 0, 0, 0
BEGIN DESCRIPTION:
Multiple Run
END DESCRIPTION:

--- UNT 034 IN UKCR.f01 (steady flow) ---

Flow Title=Multiple
Program Version=4.10
Number of Profiles= 7
Profile Names=10-year,25-year,50-year,1pct_min,100-year,1pct_plu,500-year
River Rch & RM=UNT 034 IN UKCR,Reach-1         ,11593
    1040    1423    1738    1549    2094    2832    3030
River Rch & RM=UNT 034 IN UKCR,Reach-1         ,8846
    1484    2066    2551    2297    3106    4200    4588
River Rch & RM=UNT 034 IN UKCR,Reach-1         ,3748
    1870    2636    3283    2977    4027    5446    6041
River Rch & RM=UNT 034 IN UKCR,Reach-1         ,2628
    1870    2636    3283    2977    4027    5446    6041
Boundary for River Rch & Prof#=UNT 034 IN UKCR,Reach-1         , 1
Up Type= 0
Dn Type= 3
Dn Slope=0.005
Boundary for River Rch & Prof#=UNT 034 IN UKCR,Reach-1         , 2
Up Type= 0
Dn Type= 3
Dn Slope=0.005
Boundary for River Rch & Prof#=UNT 034 IN UKCR,Reach-1         , 3
Up Type= 0
Dn Type= 3
Dn Slope=0.005
Boundary for River Rch & Prof#=UNT 034 IN UKCR,Reach-1         , 4
Up Type= 0
Dn Type= 3
Dn Slope=0.005
Boundary for River Rch & Prof#=UNT 034 IN UKCR,Reach-1         , 5
Up Type= 0
Dn Type= 3
Dn Slope=0.005
Boundary for River Rch & Prof#=UNT 034 IN UKCR,Reach-1         , 6
Up Type= 0
Dn Type= 3
Dn Slope=0.005
Boundary for River Rch & Prof#=UNT 034 IN UKCR,Reach-1         , 7
Up Type= 0
Dn Type= 3
Dn Slope=0.005
DSS Import GetInterval= 0
DSS Import GetPeak= 0
DSS Import FillOption= 0

--- UNT 034 IN UKCR.g01 (geometry) ---

Geom Title=Existing Conditions

River Reach=UNT 034 IN UKCR,Reach-1
Reach XY= 30
      3597340.00     10593356.00      3597579.50     10592231.00
      3597949.50     10591420.00      3598254.25     10591402.00
      3598339.00     10591520.00      3598966.75     10591104.00
      3599352.25     10591135.00      3599476.00     10590763.00
      3600064.25     10590586.00      3600149.50     10590294.00
      3600371.75     10590224.00      3600623.75     10590369.00
      3600682.25     10589981.00      3600869.00     10589949.00
      3601057.00     10590126.00      3601230.75     10590058.00
      3601460.00     10590214.00      3601642.00     10590075.00
      3601918.75     10590115.00      3602482.25     10589747.00
      3602626.00     10589853.00      3602591.00     10589684.00
      3602796.00     10589588.00      3602880.25     10589673.00
      3603209.00     10589399.00      3603171.75     10589066.00
      3603346.25     10589029.00      3603445.25     10588678.00
      3603267.00     10588654.00      3603056.00     10588070.00

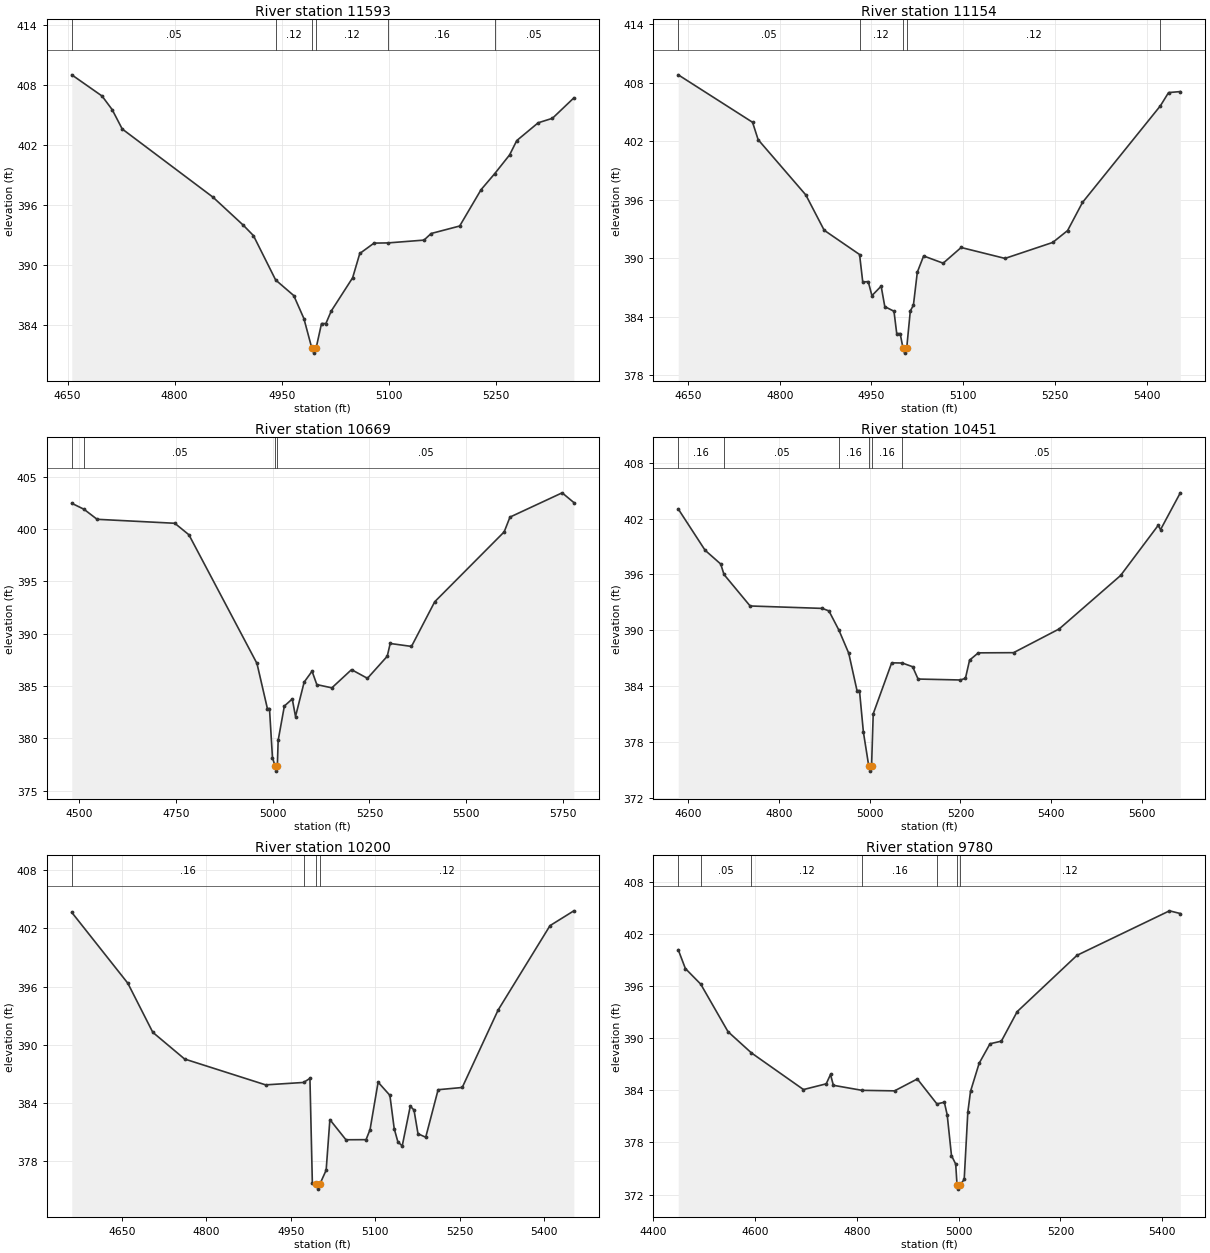
Type RM Length L Ch R = 1,11593,439,439,439
BEGIN DESCRIPTION:
UNT 034 IN UKCR 21.0
END DESCRIPTION:
XS GIS Cut Line= 3
      3597649.62     10593260.20      3597399.61     10593010.19
      3597049.58     10593010.19
#Sta/Elev= 30
  4655.9  409.04  4698.3  406.92  4712.5  405.56  4726.6  403.62  4853.9  396.79
  4896.3  393.99  4910.5  392.95  4941.6  388.51  4967.0  386.95  4981.2  384.65
  4992.3  381.69  4995.1  381.19  4998.3  381.69  5005.9  384.15  5012.0  384.15
  5019.5  385.40  5049.5  388.73  5059.5  391.16  5079.5  392.20  5099.2  392.22
  5149.5  392.50  5159.5  393.16  5199.5  393.91  5229.5  397.55  5248.6  399.15
  5269.5  401.03  5279.5  402.46  5309.5  404.24  5329.5  404.69  5359.5  406.73
#Mann=6,-1,0
  4655.9    0.05       0  4941.6    0.12       0  4992.3    0.07       0
  4998.3    0.12       0  5099.2    0.16       0  5248.6    0.05       0
Bank Sta=4992.3,4998.3
Exp/Cntr=0.3,0.1

Type RM Length L Ch R = 1,11154,485,485,485
BEGIN DESCRIPTION:
UNT 034 IN UKCR 20.0
END DESCRIPTION:
XS GIS Cut Line= 3
      3597849.57     10592810.16      3597549.61     10592610.19
      3597099.59     10592510.19
#Sta/Elev= 30
  4633.8  408.83  4755.4  403.96  4764.5  402.18  4842.6  396.50  4872.6  392.88
  4930.5  390.39  4935.7  387.57  4944.7  387.61  4950.7  386.17  4965.8  387.14
  4971.8  385.04  4986.8  384.57  4991.3  382.28  4996.9  382.28  5001.6  380.77
  5004.3  380.27  5007.6  380.77  5013.5  384.59  5018.6  385.19  5025.0  388.58
  5035.3  390.24  5067.3  389.50  5096.7  391.11  5168.5  389.99  5246.6  391.63
  5270.9  392.85  5295.2  395.73  5422.7  405.65  5436.1  407.01  5455.3  407.11
#Mann=5,-1,0
  4633.8    0.05       0  4930.5    0.12       0  5001.6    0.07       0
  5007.6    0.12       0  5422.7    0.16       0
Bank Sta=5001.6,5007.6
Exp/Cntr=0.3,0.1

Type RM Length L Ch R = 1,10669,218,218,218
BEGIN DESCRIPTION:
UNT 034 IN UKCR 19.0
END DESCRIPTION:
XS GIS Cut Line= 3
      3598094.40     10592405.38      3597649.61     10592160.19
      3596878.20     10592322.03
#Sta/Elev= 30
  4481.5  402.46  4513.0  401.89  4546.9  400.93  4747.5  400.55  4783.9  399.45
  4959.6  387.15  4986.5  382.84  4991.9  382.84  4999.6  378.15  5006.2  377.36
  5009.0  376.86  5012.2  377.36  5014.3  379.80  5030.3  383.08  5050.7  383.76
  5059.1  382.08  5081.4  385.37  5101.8  386.41  5114.1  385.13  5152.9  384.82
  5203.7  386.56  5244.8  385.73  5295.9  387.84  5303.5  389.06  5358.5  388.78
  5418.5  393.05  5597.8  399.73  5612.7  401.14  5747.4  403.46  5777.6  402.53
#Mann=4,-1,0
  4481.5    0.16       0  4513.0    0.05       0  5006.2    0.03       0
  5012.2    0.05       0
Bank Sta=5006.2,5012.2
Exp/Cntr=0.3,0.1

Type RM Length L Ch R = 1,10451,251,251,251
BEGIN DESCRIPTION:
Mapping XS 2b8a9e29
END DESCRIPTION:
XS GIS Cut Line= 3
      3598125.60     10592139.73      3597633.43     10591931.40
      3597083.01     10591773.02
#Sta/Elev= 30
  4577.7  403.03  4636.9  398.60  4671.4  397.12  4678.6  396.00  4736.2  392.62
  4895.4  392.36  4910.0  392.09  4932.0  390.03  4953.7  387.55  4971.9  383.55
  4977.4  383.54  4986.0  379.10  4998.0  375.40  5000.8  374.90  5004.0  375.40
  5007.7  381.05  5048.4  386.52  5071.9  386.50  5094.6  386.10  5106.6  384.78
  5199.4  384.68  5211.0  384.85  5220.2  386.81  5239.4  387.59  5317.2  387.61
  5417.9  390.16  5553.2  395.89  5636.1  401.27  5641.3  400.81  5684.9  404.76
#Mann=6,-1,0
  4577.7    0.16       0  4678.6    0.05       0  4932.0    0.16       0
  4998.0    0.07       0  5004.0    0.16       0  5071.9    0.05       0
Bank Sta=4998,5004
Exp/Cntr=0.3,0.1

Type RM Length L Ch R = 1,10200,420,420,420
BEGIN DESCRIPTION:
UNT 034 IN UKCR 18.0
END DESCRIPTION:
XS GIS Cut Line= 3
      3598199.61     10592010.19      3597849.61     10591760.19
      3597549.60     10591410.18
#Sta/Elev= 30
  4561.2  403.66  4660.7  396.34  4705.0  391.27  4761.5  388.51  4905.3  385.84
  4972.6  386.09  4983.9  386.51  4988.2  375.68  4995.4  375.57  4998.2  375.07
  5001.4  375.57  5012.7  377.03  5019.3  382.25  5047.8  380.17  5083.5  380.18
  5090.6  381.22  5104.9  386.12  5125.8  384.76  5133.5  381.31  5140.0  379.95
  5147.7  379.53  5162.0  383.64  5168.6  383.24  5175.7  380.79  5189.4  380.43
  5211.4  385.34  5254.2  385.57  5317.8  393.56  5410.0  402.29  5452.3  403.82
#Mann=4,-1,0
  4561.2    0.16       0  4972.6    0.12       0  4995.4    0.07       0
  5001.4    0.12       0
Bank Sta=4995.4,5001.4
Exp/Cntr=0.3,0.1

Type RM Length L Ch R = 1,9780,489,489,489
BEGIN DESCRIPTION:
UNT 034 IN UKCR 17.0
END DESCRIPTION:
XS GIS Cut Line= 3
      3598199.61     10591910.19      3597949.61     10591410.19
      3597549.63     10591260.19
#Sta/Elev= 30
  4449.2  400.18  4463.2  398.02  4493.4  396.22  4547.0  390.75  4592.9  388.31
  4695.2  384.09  4739.9  384.75  4748.3  385.83  4753.9  384.58  4810.1  384.00
  4874.1  383.94  4918.8  385.31  4957.3  382.44  4971.9  382.63  4977.5  381.18
  4985.9  376.50  4994.2  375.51  4996.8  373.13  4999.6  372.63  5002.8  373.13
  5010.9  373.74  5018.0  381.47  5023.3  383.88  5040.3  387.12  5061.6  389.36
  5083.9  389.66  5115.0  393.06  5232.5  399.54  5414.1  404.66  5435.4  404.35
#Mann=7,-1,0
  4449.2    0.16       0  4493.4    0.05       0  4592.9    0.12       0
  4810.1    0.16       0  4957.3    0.12       0  4996.8    0.07       0
  5002.8    0.12       0
Bank Sta=4996.8,5002.8
Exp/Cntr=0.3,0.1

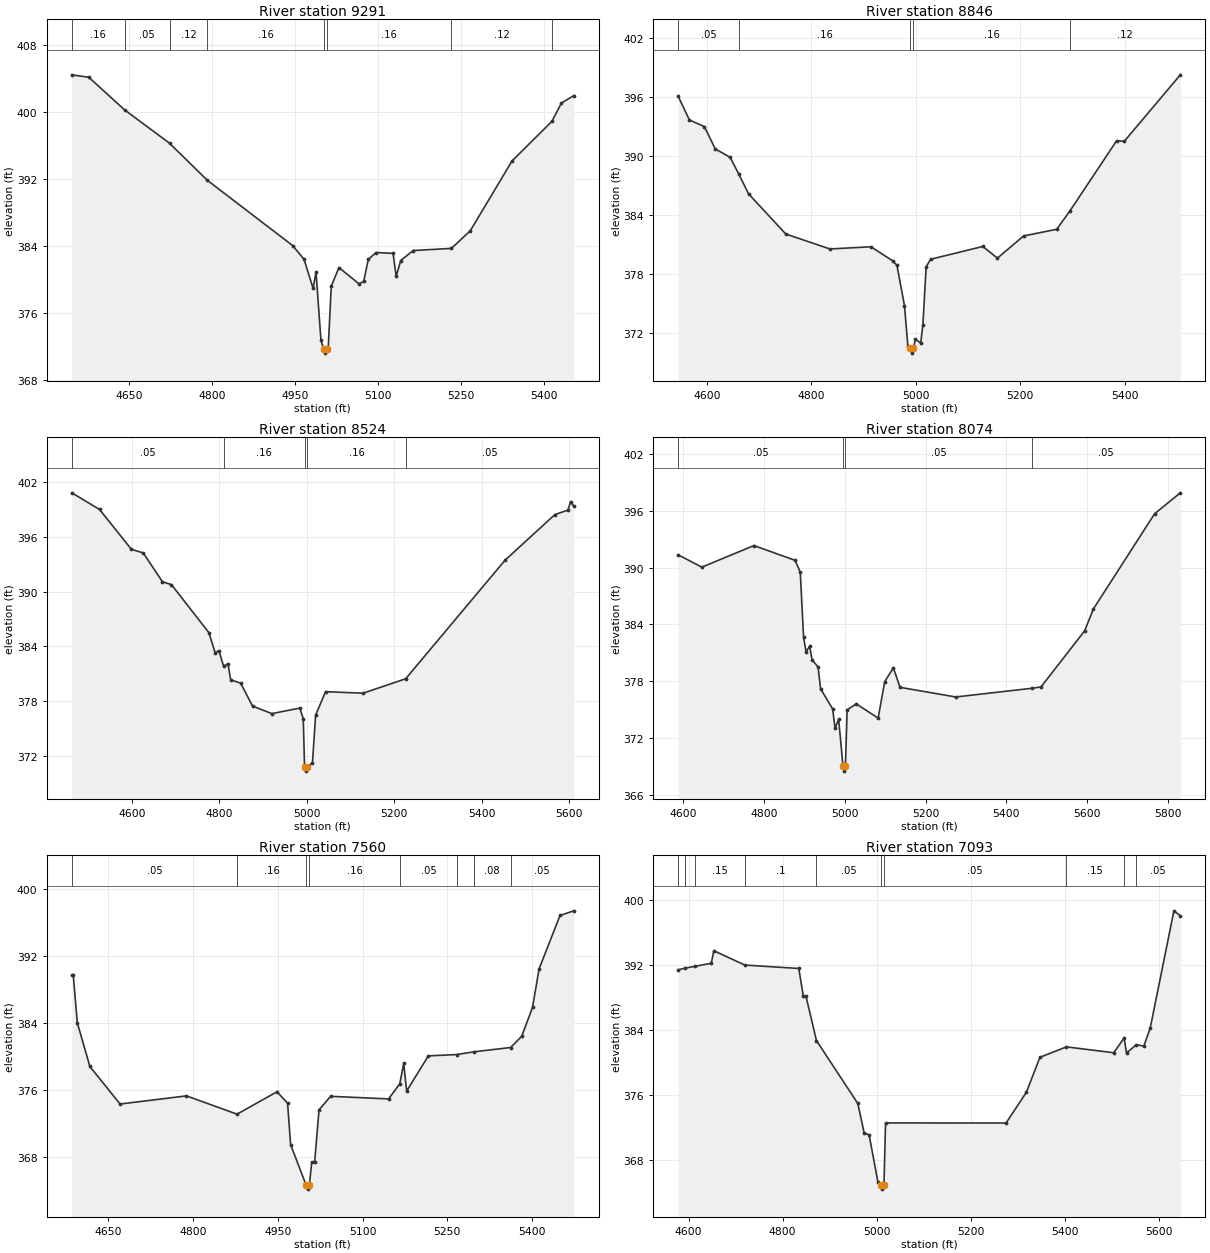
Type RM Length L Ch R = 1,9291,445,445,445
BEGIN DESCRIPTION:
UNT 034 IN UKCR 16.0
END DESCRIPTION:
XS GIS Cut Line= 3
      3598249.61     10591960.19      3598349.61     10591510.19
      3598149.60     10591110.18
#Sta/Elev= 30
  4546.4  404.49  4577.1  404.20  4642.1  400.29  4723.2  396.31  4791.5  391.88
  4945.9  384.07  4966.4  382.44  4983.0  378.94  4988.2  380.92  4997.1  372.78
  5001.8  371.70  5004.6  371.20  5007.8  371.70  5010.2  371.70  5015.8  379.19
  5029.7  381.44  5066.1  379.48  5074.5  379.79  5082.8  382.42  5096.8  383.23
  5127.6  383.14  5133.2  380.38  5141.5  382.28  5163.9  383.47  5233.2  383.73
  5267.3  385.84  5342.8  394.19  5415.0  398.93  5432.2  401.12  5454.6  402.01
#Mann=8,-1,0
  4546.4    0.16       0  4642.1    0.05       0  4723.2    0.12       0
  4791.5    0.16       0  5001.8    0.07       0  5007.8    0.16       0
  5233.2    0.12       0  5415.0    0.05       0
Bank Sta=5001.8,5007.8
Exp/Cntr=0.3,0.1

Type RM Length L Ch R = 1,8846,322,322,322
BEGIN DESCRIPTION:
UNT 034 IN UKCR 15.0
END DESCRIPTION:
XS GIS Cut Line= 3
      3598999.62     10591660.20      3598699.61     10591310.19
      3598399.61     10590910.18
#Sta/Elev= 30
  4545.2  396.09  4566.6  393.69  4595.2  393.02  4616.0  390.75  4644.5  389.90
  4660.9  388.21  4679.7  386.19  4751.0  382.10  4835.5  380.58  4914.0  380.80
  4956.3  379.35  4963.9  378.90  4978.2  374.83  4984.8  370.68  4989.5  370.49
  4992.2  369.99  4995.5  370.49  4999.1  371.42  5009.3  371.01  5013.5  372.88
  5019.7  378.75  5028.1  379.53  5128.1  380.83  5156.2  379.65  5206.2  381.90
  5269.7  382.58  5295.2  384.47  5384.3  391.58  5398.9  391.52  5506.2  398.28
#Mann=5,-1,0
  4545.2    0.05       0  4660.9    0.16       0  4989.5    0.07       0
  4995.5    0.16       0  5295.2    0.12       0
Bank Sta=4989.5,4995.5
Exp/Cntr=0.3,0.1

Type RM Length L Ch R = 1,8524,450,450,450
BEGIN DESCRIPTION:
UNT 034 IN UKCR 14.0
END DESCRIPTION:
XS GIS Cut Line= 3
      3599349.64     10591460.21      3598991.94     10591192.25
      3598599.60     10590610.17
#Sta/Elev= 30
  4462.1  400.79  4525.7  398.97  4598.6  394.61  4625.7  394.22  4669.5  391.07
  4690.3  390.75  4775.7  385.51  4790.3  383.29  4798.7  383.54  4809.6  381.81
  4819.5  382.12  4825.7  380.35  4848.7  379.97  4875.7  377.47  4919.9  376.65
  4983.9  377.25  4991.8  376.09  4994.8  370.86  4997.6  370.36  5000.8  370.86
  5012.8  371.22  5020.1  376.48  5042.8  379.05  5128.6  378.88  5226.2  380.46
  5453.5  393.42  5567.5  398.41  5597.5  398.90  5603.5  399.82  5611.0  399.31
#Mann=5,-1,0
  4462.1    0.05       0  4809.6    0.16       0  4994.8    0.07       0
  5000.8    0.16       0  5226.2    0.05       0
Bank Sta=4994.8,5000.8
Exp/Cntr=0.3,0.1

Type RM Length L Ch R = 1,8074,514,514,514
BEGIN DESCRIPTION:
UNT 034 IN UKCR 13.0
END DESCRIPTION:
XS GIS Cut Line= 3
      3599699.64     10591360.21      3599352.18     10591124.98
      3599049.60     10590360.15
#Sta/Elev= 30
  4588.1  391.34  4646.5  390.04  4775.4  392.32  4877.2  390.76  4890.0  389.51
  4898.2  382.64  4904.2  381.11  4913.1  381.68  4919.2  380.26  4934.1  379.49
  4940.2  377.20  4970.1  375.07  4976.1  373.01  4985.0  374.00  4995.7  369.00
  4998.5  368.50  5001.7  369.00  5006.0  374.98  5028.6  375.60  5082.7  374.10
  5098.9  377.95  5120.4  379.41  5136.8  377.35  5274.6  376.33  5463.3  377.25
  5485.5  377.39  5593.6  383.32  5615.1  385.62  5766.6  395.68  5830.2  397.89
#Mann=4,-1,0
  4588.1    0.05       0  4995.7    0.07       0  5001.7    0.05       0
  5463.3    0.05       0
Bank Sta=4995.7,5001.7
Exp/Cntr=0.3,0.1

Type RM Length L Ch R = 1,7560,467,467,467
BEGIN DESCRIPTION:
UNT 034 IN UKCR 12.0
END DESCRIPTION:
XS GIS Cut Line= 3
      3599949.59     10590860.18      3599549.61     10590710.19
      3599449.60     10590260.15
#Sta/Elev= 30
  4585.6  389.63  4588.3  389.63  4595.4  383.99  4617.6  378.78  4671.0  374.30
  4788.5  375.27  4878.0  373.09  4948.7  375.76  4967.4  374.39  4972.7  369.47
  5000.0  364.65  5002.7  364.15  5006.0  364.65  5010.1  367.39  5015.3  367.39
  5023.0  373.60  5043.5  375.22  5146.0  374.91  5165.9  376.71  5172.8  379.14
  5178.0  375.85  5216.4  380.04  5267.2  380.20  5296.3  380.52  5361.9  381.04
  5381.6  382.38  5400.8  385.84  5412.3  390.42  5449.4  396.79  5473.8  397.34
#Mann=8,-1,0
  4585.6    0.05       0  4878.0    0.16       0  5000.0    0.07       0
  5006.0    0.16       0  5165.9    0.05       0  5267.2     0.1       0
  5296.3    0.08       0  5361.9    0.05       0
Bank Sta=5000,5006
Exp/Cntr=0.3,0.1

Type RM Length L Ch R = 1,7093,389,389,389
BEGIN DESCRIPTION:
UNT 034 IN UKCR 11.0
END DESCRIPTION:
XS GIS Cut Line= 3
      3600149.62     10591010.21      3599999.61     10590610.19
      3599499.64     10590210.21
#Sta/Elev= 30
  4578.1  391.37  4592.4  391.57  4613.2  391.79  4648.4  392.17  4653.8  393.71
  4719.5  391.95  4834.4  391.53  4844.2  388.10  4849.6  388.14  4872.0  382.67
  4959.9  374.95  4973.3  371.36  4984.0  371.08  5002.7  365.28  5009.5  364.93
  5012.3  364.43  5015.5  364.93  5018.9  372.56  5275.1  372.55  5318.3  376.32
  5347.1  380.62  5403.4  381.90  5504.0  381.18  5526.2  382.99  5531.2  381.15
  5552.0  382.17  5568.0  381.99  5581.6  384.20  5632.0  398.61  5645.6  398.01
#Mann=10,-1,0
  4578.1    0.05       0  4592.4    0.08       0  4613.2    0.15       0
  4719.5     0.1       0  4872.0    0.05       0  5009.5    0.03       0
  5015.5    0.05       0  5403.4    0.15       0  5526.2     0.1       0
  5552.0    0.05       0
Bank Sta=5009.5,5015.5
Exp/Cntr=0.3,0.1

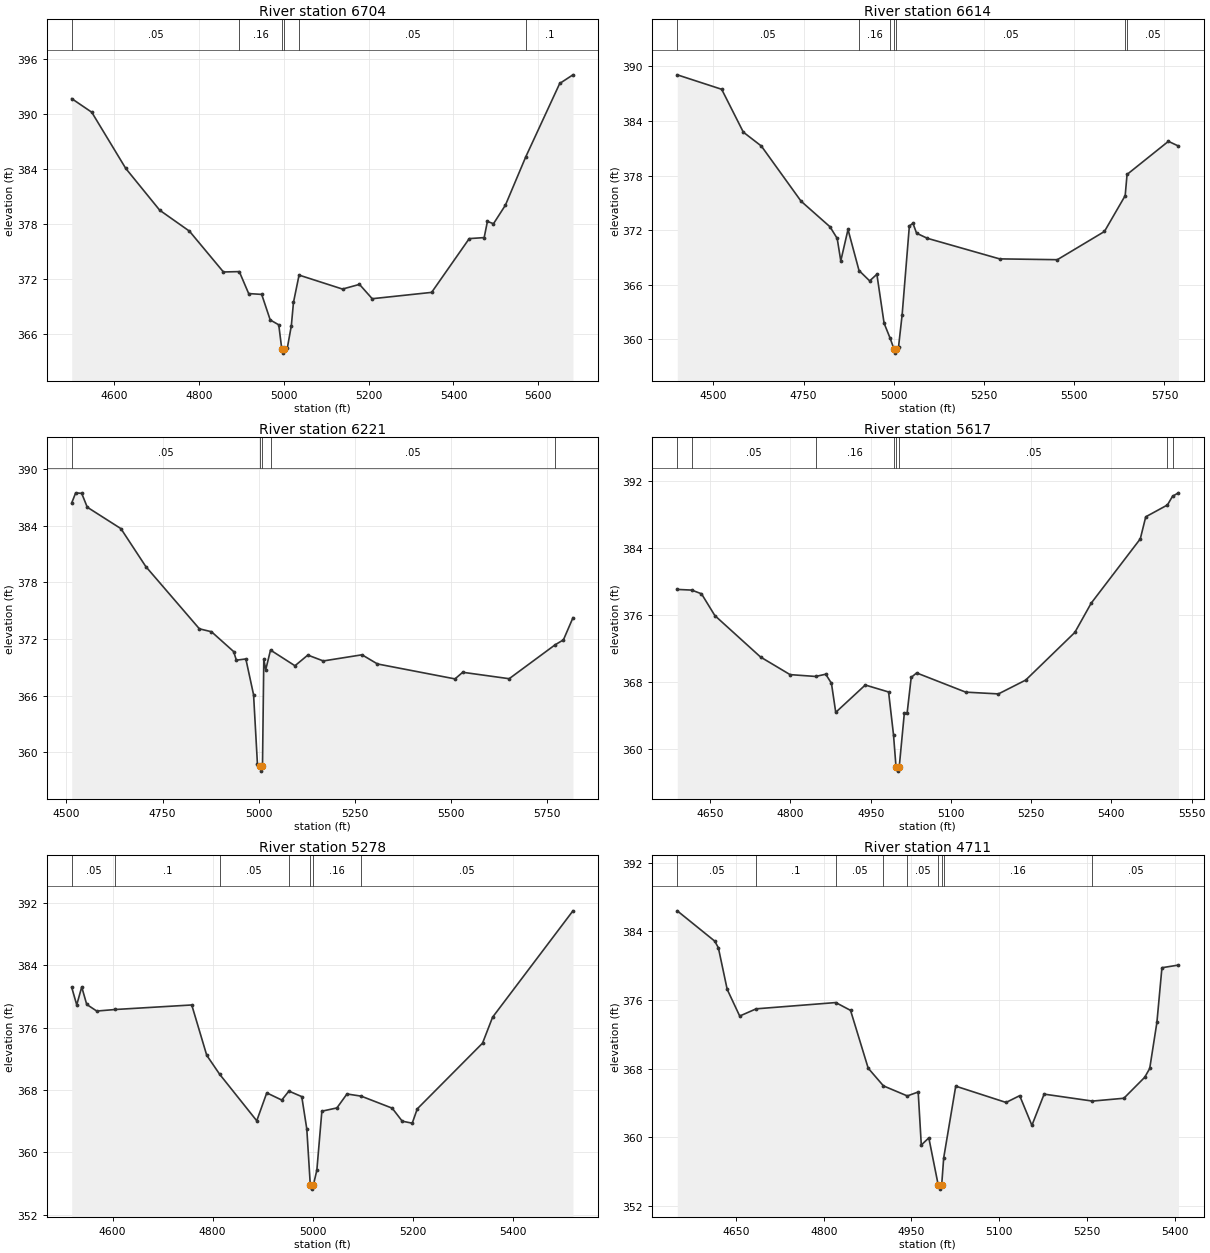
Type RM Length L Ch R = 1,6704,90,90,90
BEGIN DESCRIPTION:
UNT 034 IN UKCR 10.0
END DESCRIPTION:
XS GIS Cut Line= 6
      3600175.71     10590797.30      3600154.01     10590376.28
      3600140.99     10590237.39      3600138.82     10590031.23
      3600132.31     10589920.55      3599937.02     10589688.38
#Sta/Elev= 30
  4500.2  391.64  4547.4  390.16  4627.5  384.05  4707.6  379.50  4777.7  377.22
  4857.8  372.78  4895.2  372.82  4917.3  370.43  4948.0  370.34  4968.1  367.56
  4988.2  367.03  4995.2  364.45  4998.0  363.95  5001.2  364.45  5008.2  364.46
  5017.9  366.94  5022.9  369.47  5036.1  372.44  5138.5  370.92  5178.5  371.43
  5208.5  369.87  5348.6  370.56  5437.2  376.41  5472.4  376.52  5480.1  378.28
  5494.4  378.03  5522.5  380.05  5570.6  385.32  5650.5  393.29  5681.7  394.23
#Mann=6,-1,0
  4500.2    0.05       0  4895.2    0.16       0  4995.2    0.07       0
  5001.2    0.16       0  5036.1    0.05       0  5570.6     0.1       0
Bank Sta=4995.2,5001.2
Exp/Cntr=0.3,0.1

Type RM Length L Ch R = 1,6614,393,393,393
BEGIN DESCRIPTION:
UNT 034 IN UKCR 9.0
END DESCRIPTION:
XS GIS Cut Line= 5
      3600216.94     10590873.25      3600232.14     10590204.84
      3600236.48     10589790.34      3600225.63     10589684.00
      3600106.91     10589524.28
#Sta/Elev= 30
  4399.8  389.08  4522.9  387.49  4582.9  382.78  4632.9  381.25  4742.9  375.19
  4823.0  372.38  4843.0  371.10  4853.0  368.63  4873.0  372.08  4903.5  367.57
  4933.0  366.43  4953.0  367.16  4973.0  361.78  4989.7  360.13  5000.0  358.99
  5002.8  358.49  5006.0  358.99  5013.0  359.17  5023.0  362.70  5043.0  372.47
  5053.0  372.76  5063.0  371.67  5093.0  371.11  5293.0  368.85  5453.1  368.76
  5583.6  371.86  5641.1  375.80  5646.3  378.13  5760.9  381.77  5788.8  381.25
#Mann=7,-1,0
  4399.8    0.05       0  4903.5    0.16       0  4989.7    0.05       0
  5000.0    0.03       0  5006.0    0.05       0  5641.1    0.08       0
  5646.3    0.05       0
Bank Sta=5000,5006
Exp/Cntr=0.3,0.1

Type RM Length L Ch R = 1,6221,604,604,604
BEGIN DESCRIPTION:
Mapping XS f9ee5ff5
END DESCRIPTION:
XS GIS Cut Line= 3
      3600719.11     10590755.17      3600502.97     10590380.18
      3600396.19     10589515.56
#Sta/Elev= 30
  4513.8  386.40  4524.1  387.47  4539.8  387.41  4554.2  385.95  4641.8  383.68
  4706.5  379.67  4845.9  373.08  4877.4  372.77  4935.1  370.67  4942.1  369.76
  4966.8  369.89  4986.9  366.10  4997.0  358.73  5004.1  358.52  5006.8  358.02
  5010.1  358.52  5013.5  369.86  5018.5  368.75  5031.0  370.83  5094.6  369.17
  5128.0  370.30  5168.3  369.68  5269.0  370.33  5309.3  369.36  5510.9  367.78
  5531.0  368.48  5651.9  367.80  5771.5  371.39  5793.0  371.91  5817.8  374.25
#Mann=5,-1,0
  4513.8    0.05       0  5004.1    0.03       0  5010.1    0.05       0
  5031.0    0.05       0  5771.5    0.08       0
Bank Sta=5004.1,5010.1
Exp/Cntr=0.3,0.1

Type RM Length L Ch R = 1,5617,339,339,339
BEGIN DESCRIPTION:
UNT 034 IN UKCR 8.0
END DESCRIPTION:
XS GIS Cut Line= 3
      3600849.59     10590360.15      3600699.61     10589960.19
      3600799.62     10589460.15
#Sta/Elev= 30
  4588.3  379.03  4615.3  378.95  4633.6  378.51  4658.6  375.91  4744.0  370.97
  4799.2  368.87  4847.1  368.65  4865.9  368.92  4876.6  367.83  4884.6  364.37
  4939.8  367.63  4983.4  366.80  4992.6  361.70  4997.3  357.86  5000.1  357.36
  5003.3  357.86  5012.8  364.24  5018.0  364.24  5025.7  368.54  5035.9  369.07
  5127.6  366.78  5188.8  366.57  5239.8  368.22  5331.6  373.90  5362.2  377.39
  5454.0  385.06  5464.2  387.69  5504.7  389.10  5514.3  390.14  5525.4  390.55
#Mann=8,-1,0
  4588.3     0.1       0  4615.3    0.05       0  4847.1    0.16       0
  4992.6    0.05       0  4997.3    0.03       0  5003.3    0.05       0
  5504.7    0.08       0  5514.3    0.05       0
Bank Sta=4997.3,5003.3
Exp/Cntr=0.3,0.1

Type RM Length L Ch R = 1,5278,567,567,567
BEGIN DESCRIPTION:
UNT 034 IN UKCR 7.0
END DESCRIPTION:
XS GIS Cut Line= 3
      3600999.61     10590510.18      3600999.61     10590060.19
      3601049.61     10589510.14
#Sta/Elev= 30
  4518.4  381.16  4528.4  378.92  4538.4  381.22  4548.4  378.98  4568.4  378.13
  4605.9  378.33  4758.4  378.91  4788.4  372.45  4814.2  370.02  4888.4  364.05
  4908.4  367.63  4938.4  366.71  4952.7  367.86  4978.4  367.15  4988.5  362.98
  4995.5  355.78  4998.3  355.28  5001.5  355.78  5008.6  357.72  5018.6  365.28
  5048.7  365.70  5068.8  367.49  5097.3  367.21  5159.2  365.67  5179.3  364.00
  5199.3  363.74  5209.4  365.58  5339.9  374.01  5360.0  377.34  5520.7  390.99
#Mann=7,-1,0
  4518.4    0.05       0  4605.9     0.1       0  4814.2    0.05       0
  4952.7    0.16       0  4995.5    0.07       0  5001.5    0.16       0
  5097.3    0.05       0
Bank Sta=4995.5,5001.5
Exp/Cntr=0.3,0.1

Type RM Length L Ch R = 1,4711,510,510,510
BEGIN DESCRIPTION:
UNT 034 IN UKCR 6.0
END DESCRIPTION:
XS GIS Cut Line= 3
      3601249.61     10590610.18      3601399.61     10590210.19
      3601649.61     10589860.19
#Sta/Elev= 30
  4549.4  386.39  4613.5  382.86  4619.7  382.09  4634.8  377.24  4656.2  374.13
  4684.4  374.97  4820.5  375.70  4845.8  374.79  4876.0  368.05  4902.1  365.99
  4942.9  364.82  4961.5  365.28  4966.8  359.10  4979.7  359.93  4995.7  354.46
  4998.5  353.96  5001.7  354.46  5005.1  357.59  5025.7  365.96  5111.8  364.06
  5135.1  364.85  5156.0  361.39  5176.9  365.03  5259.6  364.22  5313.3  364.55
  5348.9  366.99  5357.5  368.02  5369.8  373.39  5378.4  379.76  5406.7  380.07
#Mann=9,-1,0
  4549.4    0.05       0  4684.4     0.1       0  4820.5    0.05       0
  4902.1    0.08       0  4942.9    0.05       0  4995.7    0.03       0
  5001.7    0.05       0  5005.1    0.16       0  5259.6    0.05       0
Bank Sta=4995.7,5001.7
Exp/Cntr=0.3,0.1

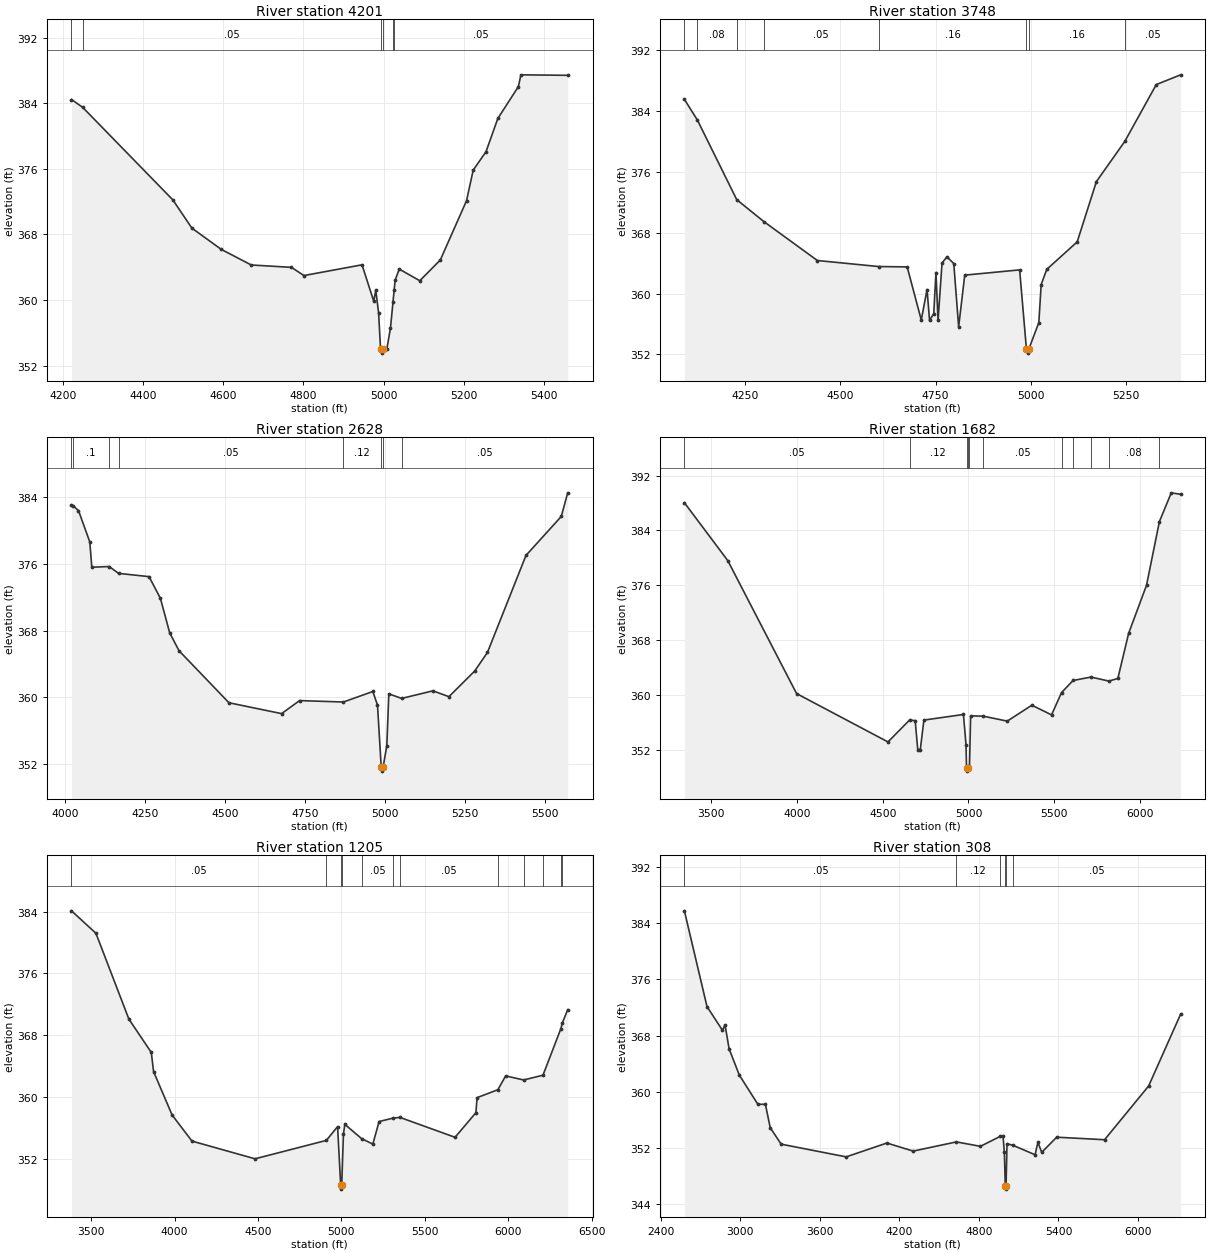
Type RM Length L Ch R = 1,4201,453,453,453
BEGIN DESCRIPTION:
UNT 034 IN UKCR 5.0
END DESCRIPTION:
XS GIS Cut Line= 3
      3601649.61     10590860.17      3601849.61     10590110.19
      3601949.62     10589660.16
#Sta/Elev= 30
  4221.6  384.46  4249.4  383.51  4474.5  372.21  4521.7  368.78  4594.8  366.19
  4669.8  364.28  4770.1  363.99  4801.2  362.99  4946.0  364.30  4975.2  359.86
  4980.3  361.21  4987.4  358.40  4992.2  354.03  4995.0  353.53  4998.2  354.03
  5008.0  354.06  5017.0  356.62  5023.2  359.74  5026.2  361.25  5028.5  362.41
  5038.8  363.78  5090.0  362.36  5141.2  364.89  5206.5  372.11  5223.2  375.85
  5255.2  378.10  5284.6  382.15  5335.8  386.03  5342.2  387.47  5458.8  387.41
#Mann=6,-1,0
  4221.6     0.1       0  4249.4    0.05       0  4992.2    0.03       0
  4998.2    0.05       0  5023.2    0.16       0  5026.2    0.05       0
Bank Sta=4992.2,4998.2
Exp/Cntr=0.3,0.1

Type RM Length L Ch R = 1,3748,1120,1120,1120
BEGIN DESCRIPTION:
UNT 034 IN UKCR 4.0
END DESCRIPTION:
XS GIS Cut Line= 3
      3602599.63     10590810.23      3602249.61     10590010.19
      3601999.59     10589660.17
#Sta/Elev= 30
  4090.1  385.50  4124.1  382.80  4227.6  372.33  4298.9  369.45  4439.4  364.34
  4600.0  363.55  4675.3  363.50  4712.3  356.53  4727.5  360.53  4734.1  356.47
  4745.1  357.38  4750.9  362.76  4756.4  356.48  4766.9  364.02  4779.7  364.83
  4797.7  363.94  4810.5  355.64  4826.5  362.42  4970.7  363.11  4988.6  352.68
  4991.4  352.18  4994.6  352.68  5021.1  356.19  5027.3  361.19  5042.0  363.18
  5121.9  366.79  5172.3  374.70  5246.9  379.98  5329.6  387.44  5393.5  388.72
#Mann=8,-1,0
  4090.1    0.05       0  4124.1    0.08       0  4227.6     0.1       0
  4298.9    0.05       0  4600.0    0.16       0  4988.6    0.07       0
  4994.6    0.16       0  5246.9    0.05       0
Bank Sta=4988.6,4994.6
Exp/Cntr=0.3,0.1

Type RM Length L Ch R = 1,2628,946,946,946
BEGIN DESCRIPTION:
UNT 034 IN UKCR 3.0
END DESCRIPTION:
XS GIS Cut Line= 3
      3603349.63     10590410.21      3602749.61     10589610.19
      3602199.61     10589560.19
#Sta/Elev= 30
  4020.0  383.05  4024.9  382.96  4041.9  382.39  4077.3  378.63  4083.6  375.60
  4138.0  375.68  4167.3  374.86  4262.7  374.47  4298.2  371.87  4327.3  367.73
  4356.5  365.59  4512.7  359.36  4677.3  358.06  4733.6  359.62  4870.7  359.45
  4962.7  360.71  4977.3  359.08  4988.9  351.67  4991.7  351.17  4994.9  351.67
  5006.5  354.22  5012.7  360.43  5052.9  359.88  5150.6  360.79  5200.8  360.09
  5281.1  363.15  5321.3  365.39  5441.8  377.01  5552.2  381.68  5572.3  384.51
#Mann=8,-1,0
  4020.0    0.05       0  4024.9     0.1       0  4138.0    0.08       0
  4167.3    0.05       0  4870.7    0.12       0  4988.9    0.07       0
  4994.9    0.12       0  5052.9    0.05       0
Bank Sta=4988.9,4994.9
Exp/Cntr=0.3,0.1

Type RM Length L Ch R = 1,1682,477,477,477
BEGIN DESCRIPTION:
UNT 034 IN UKCR 2.0
END DESCRIPTION:
XS GIS Cut Line= 3
      3604099.62     10590510.20      3603149.61     10589110.19
      3601999.60     10589460.19
#Sta/Elev= 30
  3343.2  388.05  3596.2  379.60  3997.5  360.19  4530.6  353.13  4656.9  356.34
  4689.3  356.23  4704.2  352.01  4719.1  352.02  4740.1  356.32  4970.7  357.14
  4985.7  352.72  4988.7  349.37  4991.4  348.87  4994.7  349.37  5005.9  349.62
  5012.7  356.94  5086.8  356.89  5226.2  356.17  5369.6  358.49  5484.6  357.08
  5542.7  360.33  5610.0  362.10  5714.6  362.60  5819.2  362.01  5871.3  362.40
  5934.1  368.98  6038.6  376.01  6113.4  385.28  6182.7  389.49  6237.2  389.27
#Mann=11,-1,0
  3343.2    0.05       0  4656.9    0.12       0  4988.7    0.07       0
  4994.7    0.12       0  5005.9    0.16       0  5086.8    0.05       0
  5542.7    0.08       0  5610.0     0.1       0  5714.6    0.15       0
  5819.2    0.08       0  6113.4    0.05       0
Bank Sta=4988.7,4994.7
Exp/Cntr=0.3,0.1

Type RM Length L Ch R = 1,1205,897,897,897
BEGIN DESCRIPTION:
Mapping XS dcf41609
END DESCRIPTION:
XS GIS Cut Line= 4
      3604174.88     10590292.20      3603473.48     10588979.68
      3603126.25     10588785.23      3602174.88     10589313.00
#Sta/Elev= 30
  3382.4  384.09  3528.9  381.19  3726.5  370.09  3860.9  365.78  3874.4  363.31
  3985.6  357.69  4104.5  354.32  4482.5  352.03  4910.1  354.41  4977.3  356.19
  4996.0  348.61  4998.7  348.11  5002.0  348.61  5012.5  355.24  5020.7  356.49
  5121.2  354.64  5188.5  353.93  5226.1  356.85  5311.8  357.30  5351.6  357.38
  5681.4  354.81  5806.2  357.99  5813.6  359.94  5937.8  360.96  5984.7  362.75
  6092.8  362.22  6208.4  362.84  6315.5  368.85  6324.1  369.58  6356.5  371.31
#Mann=12,-1,0
  3382.4    0.05       0  4910.1    0.16       0  4996.0    0.07       0
  5002.0    0.16       0  5121.2    0.05       0  5311.8     0.1       0
  5351.6    0.05       0  5937.8     0.1       0  6092.8    0.08       0
  6208.4    0.05       0  6315.5    0.08       0  6324.1    0.05       0
Bank Sta=4996,5002
Exp/Cntr=0.3,0.1

Type RM Length L Ch R = 1,308,0,0,0
BEGIN DESCRIPTION:
UNT 034 IN UKCR 1.0
END DESCRIPTION:
XS GIS Cut Line= 4
      3604237.36     10590181.05      3603605.42     10588382.45
      3602910.98     10588340.79      3602140.12     10589181.09
#Sta/Elev= 30
  2578.9  385.76  2749.4  372.14  2866.0  368.76  2885.4  369.53  2916.4  366.11
  2993.2  362.39  3133.2  358.23  3189.9  358.23  3226.4  354.90  3308.5  352.56
  3799.0  350.75  4106.1  352.72  4304.5  351.57  4630.0  352.88  4811.7  352.25
  4961.2  353.67  4982.0  353.70  4992.0  351.45  4999.0  346.66  5001.8  346.16
  5005.0  346.66  5012.0  352.63  5060.0  352.37  5223.8  351.05  5245.4  352.83
  5273.8  351.39  5386.6  353.55  5747.9  353.19  6080.3  360.84  6321.3  371.05
#Mann=6,-1,0
  2578.9    0.05       0  4630.0    0.12       0  4961.2    0.16       0
  4999.0    0.07       0  5005.0    0.16       0  5060.0    0.05       0
Bank Sta=4999,5005
Exp/Cntr=0.3,0.1

Chan Stop Cuts=-1