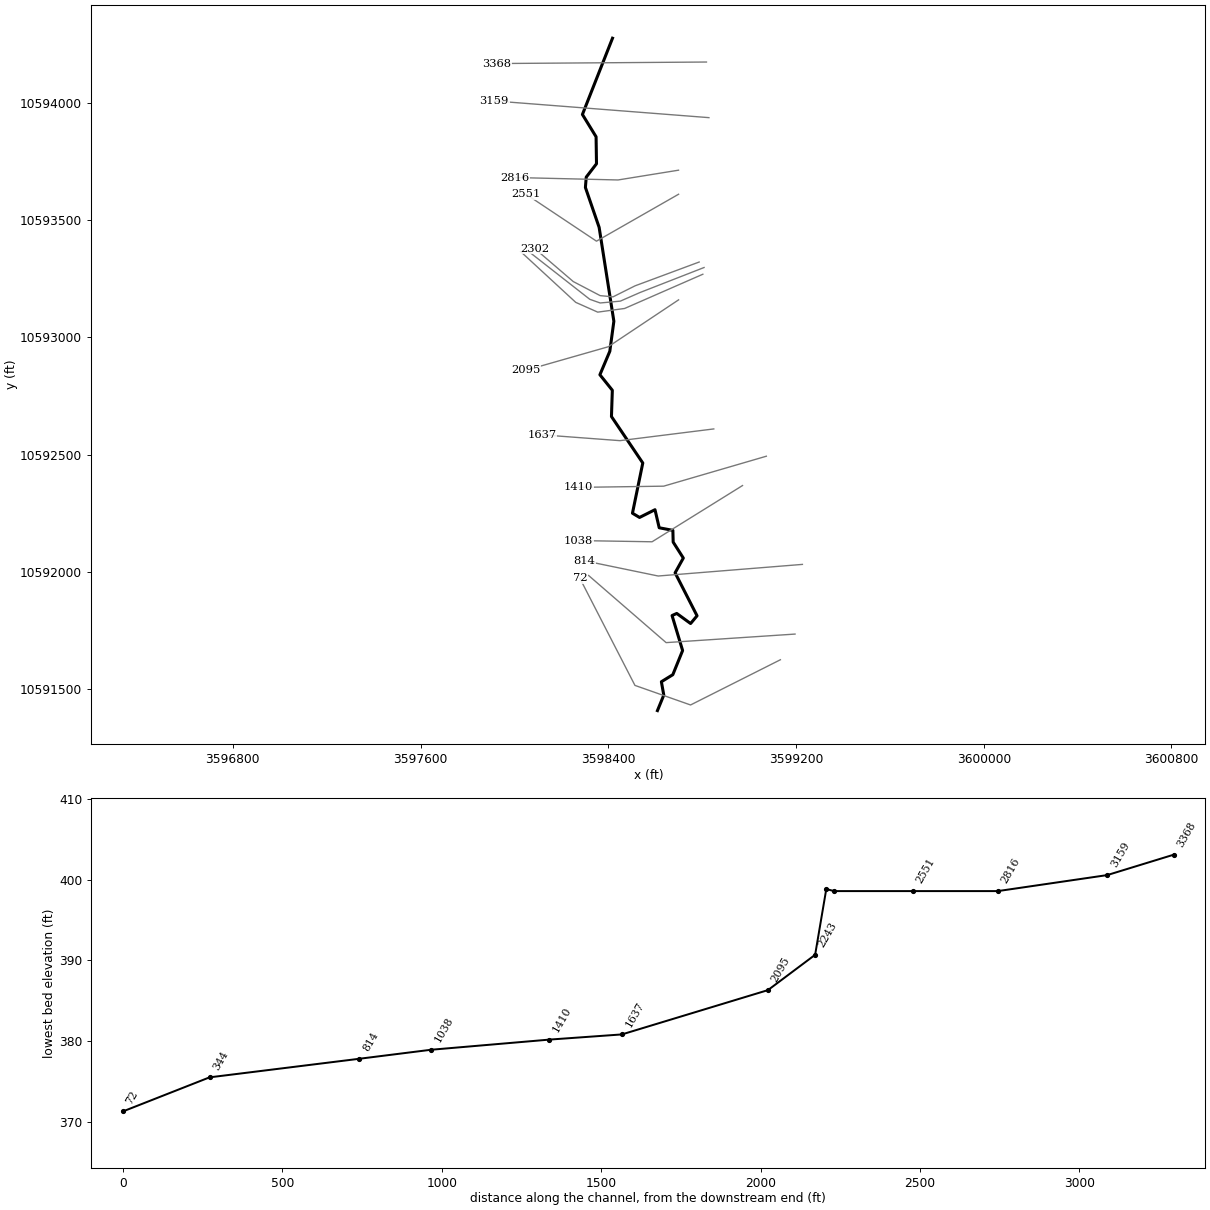
--- UNT 036 IN UKCR.prj (project) ---

Proj Title=UNT 036 IN UKCR Base Level Engineering
Current Plan=p01
Default Exp/Contr=0.3,0.1
English Units
Geom File=g01
Flow File=f01
Plan File=p01
Y Axis Title=Elevation
X Axis Title(PF)=Main Channel Distance
X Axis Title(XS)=Station
BEGIN DESCRIPTION:
UNT 036 IN UKCR
END DESCRIPTION:
DSS Export Rating Curves= 0
DSS Export Rating Curve Sorted= 0
DSS Export Volume Flow Curves= 0
DXF OffsetX= 0
DXF OffsetY= 0
DXF ScaleX= 1
DXF ScaleY= 10

--- UNT 036 IN UKCR.p01 (plan) ---

Plan Title=Multiple Run
Short Identifier=Multiple
Geom File=g01
Flow File=f01
Subcritical Flow
K Sum by GR= 0
Std Step Tol= 0.01
Critical Tol= 0.01
Num of Std Step Trials= 20
Max Error Tol= 0.3
Flow Tol Ratio= 0.001
Split Flow NTrial= 30
Split Flow Tol= 0.02
Split Flow Ratio= 0.02
Log Output Level= 0
Friction Slope Method= 1
Unsteady Friction Slope Method= 2
Unsteady Bridges Friction Slope Method= 1
Parabolic Critical Depth
Global Vel Dist=  1 , 1 , 1
Global Log Level= 0
CheckData=True
Encroach Param= -1, 0, 0, 0
BEGIN DESCRIPTION:
Multiple Run
END DESCRIPTION:

--- UNT 036 IN UKCR.f01 (steady flow) ---

Flow Title=Multiple
Number of Profiles=7
Profile Names=10-year,25-year,50-year,1pct_min,100-year,1pct_plu,500-year
River Rch & RM= UNT 036 IN UKCR,Reach-1,3368
     520     682     809     703     950    1285    1303
River Rch & RM= UNT 036 IN UKCR,Reach-1,72
    1484    2066    2551    2297    3106    4200    4588
Boundary for River Rch & Prof#=UNT 036 IN UKCR,Reach-1,1
Up Type=0
Dn Type=3
Dn Slope=0.005
Boundary for River Rch & Prof#=UNT 036 IN UKCR,Reach-1,2
Up Type=0
Dn Type=3
Dn Slope=0.005
Boundary for River Rch & Prof#=UNT 036 IN UKCR,Reach-1,3
Up Type=0
Dn Type=3
Dn Slope=0.005
Boundary for River Rch & Prof#=UNT 036 IN UKCR,Reach-1,4
Up Type=0
Dn Type=3
Dn Slope=0.005
Boundary for River Rch & Prof#=UNT 036 IN UKCR,Reach-1,5
Up Type=0
Dn Type=3
Dn Slope=0.005
Boundary for River Rch & Prof#=UNT 036 IN UKCR,Reach-1,6
Up Type=0
Dn Type=3
Dn Slope=0.005
Boundary for River Rch & Prof#=UNT 036 IN UKCR,Reach-1,7
Up Type=0
Dn Type=3
Dn Slope=0.005

--- UNT 036 IN UKCR.g01 (geometry) ---

Geom Title=Existing Conditions

River Reach=UNT 036 IN UKCR,Reach-1
Reach XY= 30
      3598418.00     10594275.00      3598289.75     10593950.00
      3598348.00     10593855.00      3598349.75     10593740.00
      3598306.00     10593683.00      3598302.50     10593639.00
      3598361.00     10593469.00      3598423.75     10593069.00
      3598406.50     10592941.00      3598364.25     10592841.00
      3598417.25     10592775.00      3598413.50     10592663.00
      3598547.00     10592465.00      3598503.00     10592251.00
      3598533.25     10592233.00      3598599.00     10592266.00
      3598617.00     10592189.00      3598675.25     10592178.00
      3598676.50     10592128.00      3598719.75     10592060.00
      3598684.75     10591997.00      3598778.25     10591814.00
      3598750.75     10591781.00      3598691.75     10591824.00
      3598671.75     10591815.00      3598716.75     10591666.00
      3598675.00     10591563.00      3598626.25     10591533.00
      3598636.50     10591476.00      3598609.50     10591410.00

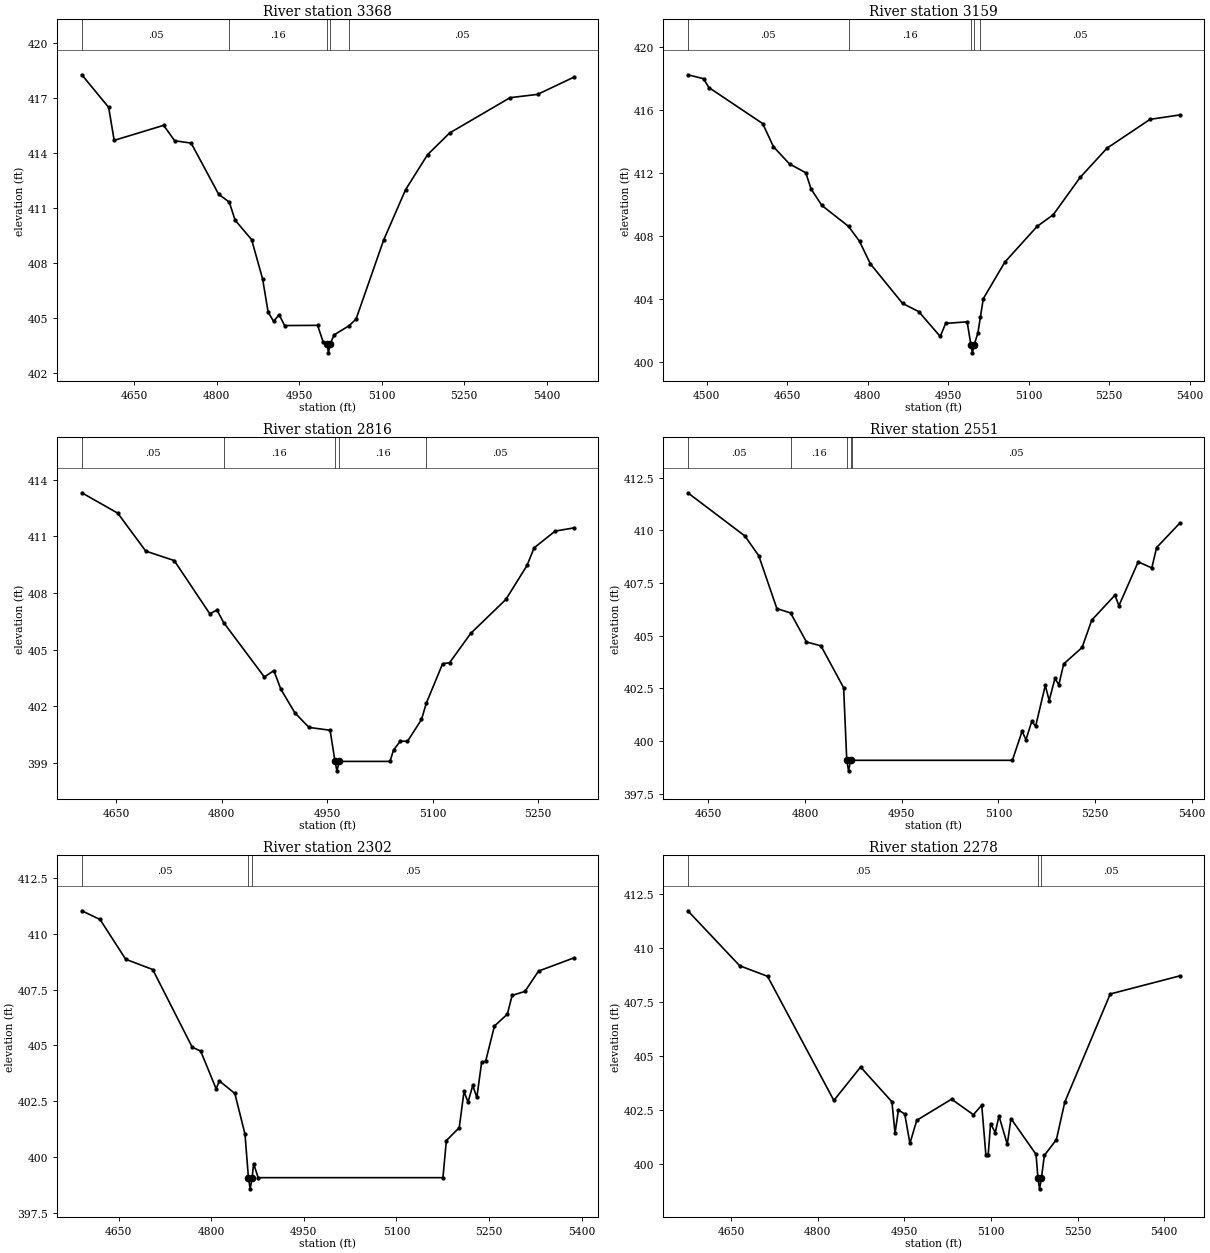
Type RM Length L Ch R = 1,3368,209,209,209
BEGIN DESCRIPTION:
UNT 036 IN UKCR 6.0
END DESCRIPTION:
XS GIS Cut Line= 2
      3598818.37     10594173.48      3597923.60     10594166.98
#Sta/Elev= 30
  4554.5  418.27  4603.3  416.49  4613.3  414.69  4703.3  415.51  4723.3  414.67
  4753.3  414.54  4803.3  411.75  4822.6  411.32  4833.3  410.33  4863.3  409.27
  4883.3  407.12  4893.3  405.31  4903.3  404.81  4913.3  405.17  4923.3  404.58
  4983.3  404.59  4993.3  403.69  5000.3  403.59  5003.0  403.09  5006.3  403.59
  5013.3  404.07  5041.0  404.58  5053.3  404.94  5103.3  409.24  5143.3  412.00
  5183.3  413.91  5223.3  415.09  5333.3  417.02  5383.3  417.20  5449.3  418.14
#Mann=5,-1,0
  4554.5    0.05       0  4822.6    0.16       0  5000.3    0.07       0
  5006.3    0.16       0  5041.0    0.05       0
Bank Sta=5000.3,5006.3
Exp/Cntr=0.3,0.1

Type RM Length L Ch R = 1,3159,343,343,343
BEGIN DESCRIPTION:
Mapping XS 1ba56369
END DESCRIPTION:
XS GIS Cut Line= 2
      3598828.81     10593936.51      3597914.28     10594007.66
#Sta/Elev= 30
  4464.6  418.22  4493.9  417.97  4503.9  417.41  4604.2  415.12  4624.3  413.65
  4654.4  412.55  4684.5  412.00  4694.5  410.96  4714.6  409.92  4764.3  408.59
  4784.8  407.64  4804.8  406.22  4865.0  403.70  4895.1  403.18  4935.2  401.60
  4945.3  402.43  4985.4  402.53  4992.4  401.06  4995.2  400.56  4998.4  401.06
  5005.4  401.82  5010.2  402.86  5015.5  404.00  5055.6  406.32  5115.8  408.59
  5145.9  409.33  5196.0  411.70  5246.2  413.56  5326.4  415.39  5381.9  415.67
#Mann=5,-1,0
  4464.6    0.05       0  4764.3    0.16       0  4992.4    0.07       0
  4998.4    0.16       0  5010.2    0.05       0
Bank Sta=4992.4,4998.4
Exp/Cntr=0.3,0.1

Type RM Length L Ch R = 1,2816,265,265,265
BEGIN DESCRIPTION:
Mapping XS 5772099a
END DESCRIPTION:
XS GIS Cut Line= 3
      3598699.31     10593712.65      3598441.53     10593670.99
      3598002.98     10593681.37
#Sta/Elev= 30
  4600.9  413.31  4652.0  412.23  4691.8  410.22  4732.3  409.72  4782.9  406.90
  4793.1  407.10  4802.7  406.43  4860.5  403.55  4874.0  403.89  4884.0  402.90
  4904.0  401.65  4924.0  400.88  4954.0  400.73  4961.0  399.08  4963.7  398.58
  4967.0  399.08  5039.2  399.08  5044.2  399.68  5054.0  400.16  5064.0  400.14
  5084.0  401.30  5090.8  402.16  5114.0  404.25  5124.0  404.31  5154.0  405.86
  5204.0  407.66  5234.1  409.46  5244.1  410.39  5274.1  411.28  5300.7  411.45
#Mann=5,-1,0
  4600.9    0.05       0  4802.7    0.16       0  4961.0    0.07       0
  4967.0    0.16       0  5090.8    0.05       0
Bank Sta=4961,4967
Exp/Cntr=0.3,0.1

Type RM Length L Ch R = 1,2551,249,249,249
BEGIN DESCRIPTION:
UNT 036 IN UKCR 5.0
END DESCRIPTION:
XS GIS Cut Line= 3
      3598699.58     10593610.17      3598349.61     10593410.19
      3598049.63     10593610.17
#Sta/Elev= 30
  4618.0  411.79  4706.5  409.74  4728.1  408.80  4756.2  406.29  4777.5  406.08
  4802.2  404.70  4824.6  404.52  4859.8  402.53  4864.7  399.08  4867.5  398.58
  4870.7  399.08  4872.9  399.08  5121.7  399.08  5136.8  400.46  5142.8  400.06
  5151.8  400.93  5157.8  400.70  5172.8  402.64  5178.8  401.92  5187.8  402.97
  5193.8  402.67  5201.4  403.66  5229.9  404.44  5244.9  405.74  5281.0  406.93
  5287.0  406.42  5317.0  408.51  5338.1  408.22  5345.6  409.19  5381.6  410.35
#Mann=5,-1,0
  4618.0    0.05       0  4777.5    0.16       0  4864.7   0.033       0
  4870.7    0.16       0  4872.9    0.05       0
Bank Sta=4864.7,4870.7
Exp/Cntr=0.3,0.1

Type RM Length L Ch R = 1,2302,24,24,24
BEGIN DESCRIPTION:
Mapping XS 4905b598
END DESCRIPTION:
XS GIS Cut Line= 6
      3598787.27     10593321.35      3598513.85     10593219.79
      3598420.10     10593172.92      3598365.41     10593178.13
      3598250.83     10593238.02      3598086.76     10593378.65
#Sta/Elev= 30
  4590.5  411.03  4620.0  410.64  4661.5  408.86  4705.3  408.40  4769.3  404.92
  4782.9  404.75  4808.0  403.06  4813.3  403.41  4838.3  402.85  4854.7  401.03
  4860.3  399.08  4863.1  398.58  4866.3  399.08  4868.7  399.71  4876.0  399.08
  5175.3  399.08  5180.8  400.74  5201.7  401.32  5209.4  402.94  5215.9  402.46
  5223.6  403.21  5230.2  402.67  5237.9  404.24  5244.5  404.30  5258.7  405.87
  5279.6  406.40  5287.3  407.24  5308.1  407.42  5330.1  408.33  5387.3  408.92
#Mann=3,-1,0
  4590.5    0.05       0  4860.3   0.033       0  4866.3    0.05       0
Bank Sta=4860.3,4866.3
Exp/Cntr=0.3,0.1

Type RM Length L Ch R = 1,2278,35,35,35
BEGIN DESCRIPTION:
Mapping XS b6323dc1
END DESCRIPTION:
XS GIS Cut Line= 6
      3598808.15     10593297.93      3598534.68     10593191.15
      3598451.35     10593154.69      3598365.41     10593146.88
      3598321.14     10593162.50      3598058.12     10593368.23
#Sta/Elev= 30
  4575.4  411.74  4665.2  409.19  4713.4  408.70  4828.2  402.94  4874.5  404.49
  4928.7  402.88  4934.1  401.42  4940.0  402.50  4950.9  402.31  4959.9  400.95
  4971.7  402.02  5032.0  403.00  5069.7  402.28  5084.2  402.72  5091.3  400.43
  5095.4  400.43  5099.5  401.87  5107.6  401.45  5114.0  402.22  5128.4  400.91
  5134.8  402.10  5178.2  400.44  5181.5  399.34  5184.3  398.84  5187.5  399.34
  5192.6  400.39  5213.4  401.12  5227.9  402.86  5306.6  407.88  5427.1  408.72
#Mann=3,-1,0
  4575.4    0.05       0  5181.5    0.03       0  5187.5    0.05       0
Bank Sta=5181.5,5187.5
Exp/Cntr=0.3,0.1

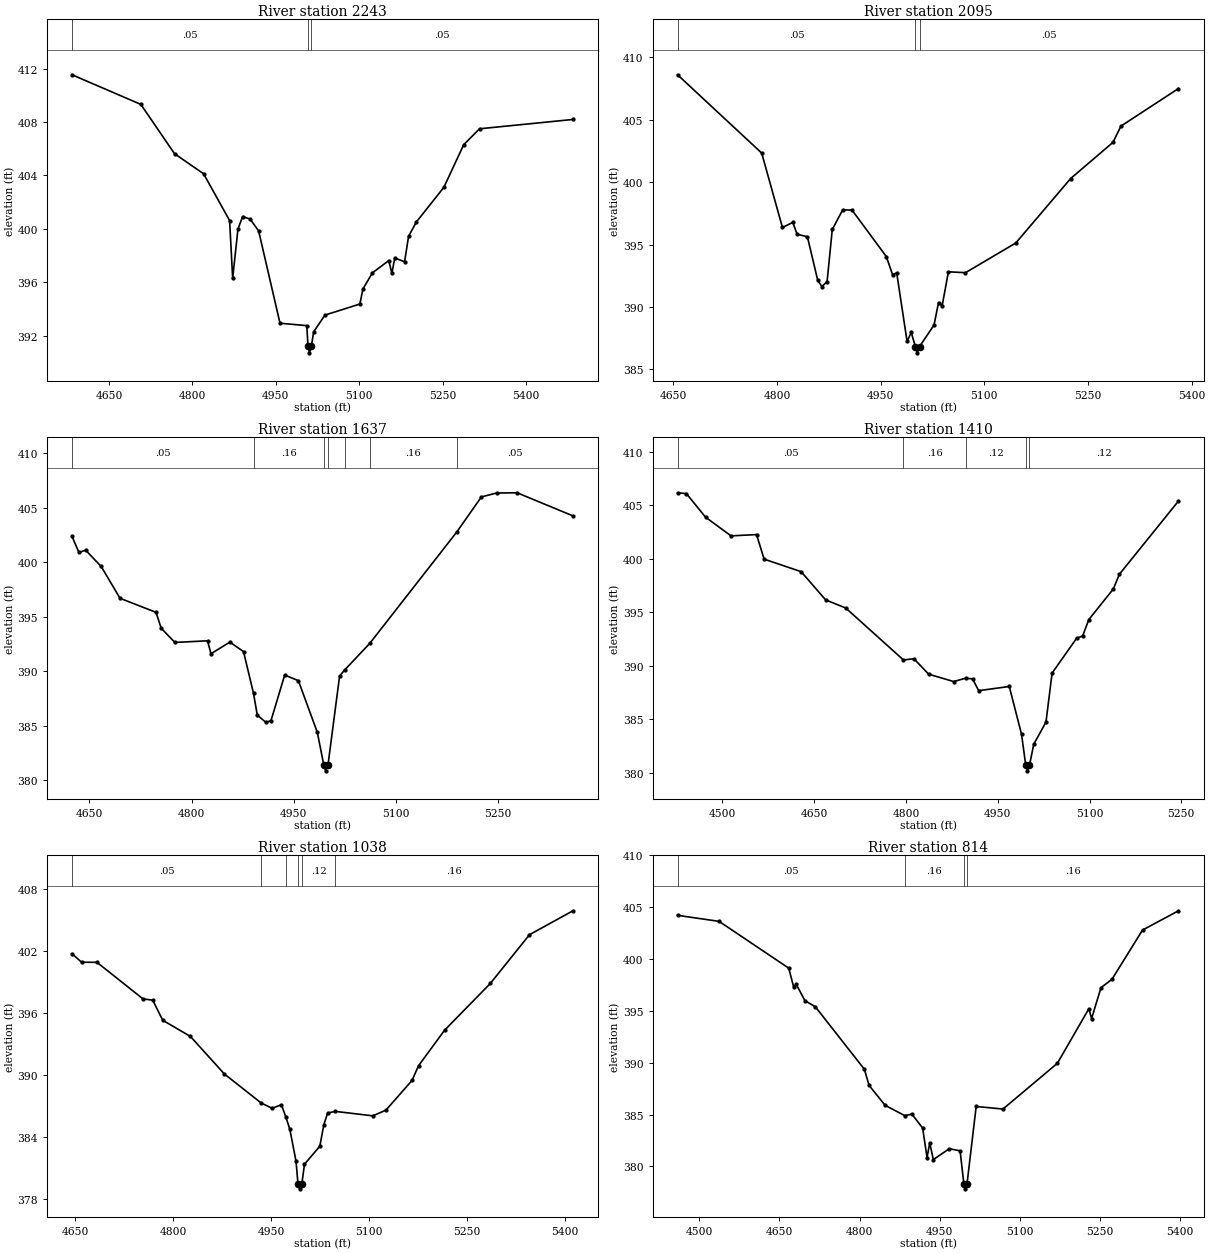
Type RM Length L Ch R = 1,2243,148,148,148
BEGIN DESCRIPTION:
Mapping XS 5a385813
END DESCRIPTION:
XS GIS Cut Line= 5
      3598802.92     10593269.28      3598469.58     10593123.44
      3598354.99     10593107.81      3598261.24     10593149.48
      3598027.10     10593365.41
#Sta/Elev= 30
  4583.6  411.55  4707.3  409.33  4767.9  405.63  4820.1  404.13  4866.9  400.62
  4872.4  396.29  4881.9  399.98  4890.3  400.92  4903.8  400.73  4919.1  399.84
  4957.5  392.92  5005.7  392.74  5007.8  391.20  5010.5  390.70  5013.8  391.20
  5018.1  392.28  5038.3  393.53  5101.1  394.36  5106.6  395.49  5123.7  396.70
  5153.1  397.62  5158.6  396.65  5163.8  397.81  5181.5  397.53  5188.6  399.43
  5202.8  400.52  5252.1  403.11  5287.8  406.31  5316.2  407.50  5484.2  408.20
#Mann=3,-1,0
  4583.6    0.05       0  5007.8    0.03       0  5013.8    0.05       0
Bank Sta=5007.8,5013.8
Exp/Cntr=0.3,0.1

Type RM Length L Ch R = 1,2095,458,458,458
BEGIN DESCRIPTION:
UNT 036 IN UKCR 4.0
END DESCRIPTION:
XS GIS Cut Line= 3
      3598699.61     10593160.19      3598399.61     10592960.19
      3598049.57     10592860.18
#Sta/Elev= 30
  4656.3  408.60  4778.0  402.33  4808.0  396.37  4823.1  396.78  4829.1  395.83
  4844.1  395.63  4859.1  392.13  4865.1  391.64  4872.6  392.04  4880.1  396.21
  4895.2  397.79  4908.7  397.76  4958.3  394.04  4967.3  392.59  4973.3  392.74
  4988.3  387.24  4994.3  387.96  5000.3  386.83  5003.1  386.33  5006.3  386.83
  5027.3  388.56  5033.8  390.36  5039.0  390.09  5048.1  392.82  5072.8  392.75
  5145.6  395.13  5224.9  400.29  5286.0  403.18  5297.7  404.49  5380.9  407.50
#Mann=3,-1,0
  4656.3    0.05       0  5000.3    0.03       0  5006.3    0.05       0
Bank Sta=5000.3,5006.3
Exp/Cntr=0.3,0.1

Type RM Length L Ch R = 1,1637,227,227,227
BEGIN DESCRIPTION:
UNT 036 IN UKCR 3.0
END DESCRIPTION:
XS GIS Cut Line= 3
      3598849.59     10592610.19      3598449.61     10592560.19
      3598117.83     10592585.04
#Sta/Elev= 30
  4624.4  402.36  4634.5  400.89  4644.5  401.09  4667.2  399.60  4694.9  396.68
  4747.8  395.39  4755.4  393.93  4775.5  392.63  4823.4  392.78  4828.5  391.59
  4856.2  392.66  4876.3  391.79  4891.0  387.95  4896.5  385.96  4909.1  385.30
  4916.6  385.45  4936.8  389.64  4956.9  389.12  4984.7  384.38  4994.3  381.35
  4997.0  380.85  5000.3  381.35  5017.4  389.54  5024.8  390.10  5061.7  392.54
  5189.5  402.76  5225.7  405.98  5248.1  406.34  5278.2  406.36  5360.2  404.24
#Mann=7,-1,0
  4624.4    0.05       0  4891.0    0.16       0  4994.3    0.07       0
  5000.3    0.16       0  5024.8    0.12       0  5061.7    0.16       0
  5189.5    0.05       0
Bank Sta=4994.3,5000.3
Exp/Cntr=0.3,0.1

Type RM Length L Ch R = 1,1410,372,372,372
BEGIN DESCRIPTION:
Mapping XS 3d216c4e
END DESCRIPTION:
XS GIS Cut Line= 3
      3599073.56     10592493.91      3598636.04     10592366.29
      3598273.03     10592361.11
#Sta/Elev= 30
  4426.6  406.15  4441.1  406.07  4472.4  403.87  4514.0  402.13  4555.7  402.25
  4568.1  399.96  4628.6  398.79  4668.6  396.16  4701.5  395.40  4795.9  390.55
  4812.9  390.67  4837.0  389.23  4877.9  388.54  4897.4  388.85  4908.8  388.79
  4918.8  387.69  4968.8  388.08  4988.8  383.63  4995.8  380.71  4998.5  380.21
  5001.8  380.71  5008.8  382.69  5028.8  384.76  5038.8  389.33  5078.8  392.57
  5088.8  392.80  5098.8  394.32  5138.8  397.17  5148.8  398.55  5245.4  405.38
#Mann=5,-1,0
  4426.6    0.05       0  4795.9    0.16       0  4897.4    0.12       0
  4995.8    0.07       0  5001.8    0.12       0
Bank Sta=4995.8,5001.8
Exp/Cntr=0.3,0.1

Type RM Length L Ch R = 1,1038,224,224,224
BEGIN DESCRIPTION:
UNT 036 IN UKCR 2.0
END DESCRIPTION:
XS GIS Cut Line= 3
      3598972.01     10592368.92      3598586.56     10592129.32
      3598273.06     10592134.50
#Sta/Elev= 30
  4645.1  401.75  4659.7  400.93  4683.3  400.92  4753.9  397.37  4768.7  397.25
  4784.1  395.30  4826.5  393.73  4878.5  390.09  4935.0  387.27  4951.7  386.76
  4965.8  387.11  4972.9  385.87  4978.8  384.72  4988.3  381.61  4991.2  379.45
  4994.0  378.95  4997.2  379.45  5001.2  381.34  5024.7  383.08  5030.8  385.15
  5036.7  386.31  5048.7  386.46  5105.9  386.03  5125.9  386.58  5165.9  389.46
  5175.9  390.89  5215.9  394.34  5285.9  398.87  5345.9  403.60  5412.5  405.92
#Mann=6,-1,0
  4645.1    0.05       0  4935.0    0.16       0  4972.9    0.12       0
  4991.2    0.07       0  4997.2    0.12       0  5048.7    0.16       0
Bank Sta=4991.2,4997.2
Exp/Cntr=0.3,0.1

Type RM Length L Ch R = 1,814,470,470,470
BEGIN DESCRIPTION:
Mapping XS c2530e03
END DESCRIPTION:
XS GIS Cut Line= 3
      3599227.20     10592032.96      3598612.60     10591983.48
      3598297.45     10592048.60
#Sta/Elev= 30
  4459.1  404.20  4536.9  403.62  4667.4  399.11  4676.5  397.31  4681.5  397.55
  4697.5  395.99  4717.5  395.37  4809.0  389.37  4817.9  387.81  4847.9  385.89
  4884.6  384.90  4898.1  385.04  4918.2  383.70  4926.5  380.85  4931.5  382.27
  4938.2  380.66  4968.3  381.71  4988.4  381.50  4995.4  378.34  4998.2  377.84
  5001.4  378.34  5018.5  385.78  5068.7  385.53  5170.6  389.94  5229.6  395.20
  5234.7  394.25  5252.3  397.23  5272.8  398.03  5330.1  402.78  5397.5  404.64
#Mann=4,-1,0
  4459.1    0.05       0  4884.6    0.16       0  4995.4    0.07       0
  5001.4    0.16       0
Bank Sta=4995.4,5001.4
Exp/Cntr=0.3,0.1

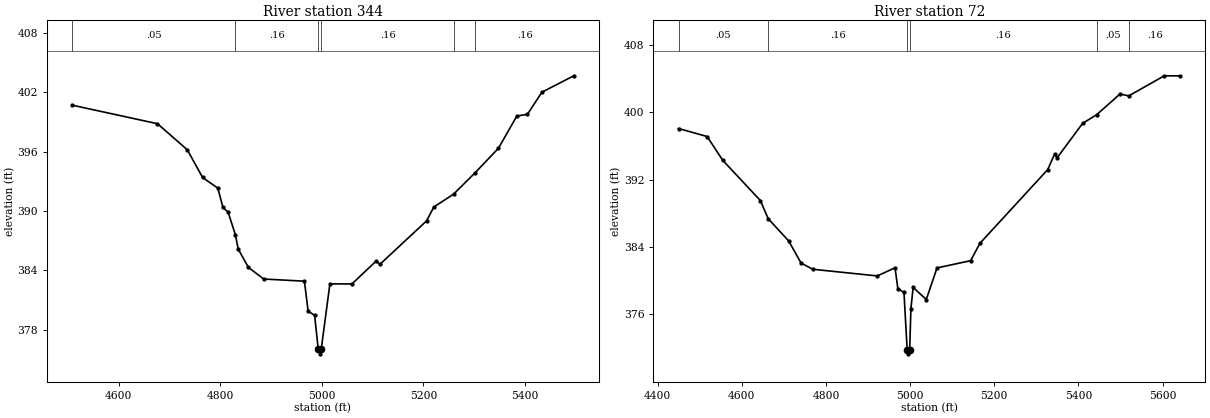
Type RM Length L Ch R = 1,344,272,272,272
BEGIN DESCRIPTION:
Mapping XS 90474b30
END DESCRIPTION:
XS GIS Cut Line= 3
      3599195.90     10591736.08      3598646.45     10591699.63
      3598316.25     10591985.63
#Sta/Elev= 30
  4508.6  400.70  4676.7  398.82  4735.4  396.18  4765.5  393.38  4795.5  392.30
  4805.5  390.35  4815.6  389.88  4830.0  387.59  4835.6  386.13  4855.7  384.28
  4885.7  383.11  4965.9  382.89  4973.1  379.87  4985.9  379.43  4993.0  376.04
  4995.7  375.54  4999.0  376.04  5016.0  382.62  5059.3  382.61  5107.5  384.95
  5114.1  384.58  5206.2  388.99  5220.5  390.39  5259.5  391.70  5302.0  393.87
  5347.7  396.34  5383.9  399.60  5404.7  399.77  5433.2  402.01  5496.1  403.67
#Mann=6,-1,0
  4508.6    0.05       0  4830.0    0.16       0  4993.0    0.07       0
  4999.0    0.16       0  5259.5    0.05       0  5302.0    0.16       0
Bank Sta=4993,4999
Exp/Cntr=0.3,0.1

Type RM Length L Ch R = 1,72,0,0,0
BEGIN DESCRIPTION:
UNT 036 IN UKCR 1.0
END DESCRIPTION:
XS GIS Cut Line= 4
      3599133.40     10591626.69      3598750.62     10591434.00
      3598513.64     10591517.34      3598279.27     10591973.05
#Sta/Elev= 30
  4449.8  398.07  4517.7  397.12  4554.8  394.30  4644.4  389.51  4662.6  387.38
  4711.5  384.72  4740.9  382.10  4768.8  381.36  4921.8  380.57  4964.2  381.53
  4970.9  379.05  4985.4  378.61  4993.0  371.82  4995.8  371.32  4999.0  371.82
  5001.9  376.68  5007.2  379.20  5038.4  377.77  5063.9  381.52  5143.8  382.38
  5166.0  384.45  5326.9  393.19  5343.4  395.04  5349.1  394.58  5410.0  398.69
  5443.3  399.71  5498.7  402.17  5519.4  401.94  5603.9  404.33  5642.0  404.32
#Mann=6,-1,0
  4449.8    0.05       0  4662.6    0.16       0  4993.0    0.07       0
  4999.0    0.16       0  5443.3    0.05       0  5519.4    0.16       0
Bank Sta=4993,4999
Exp/Cntr=0.3,0.1

Chan Stop Cuts=-1