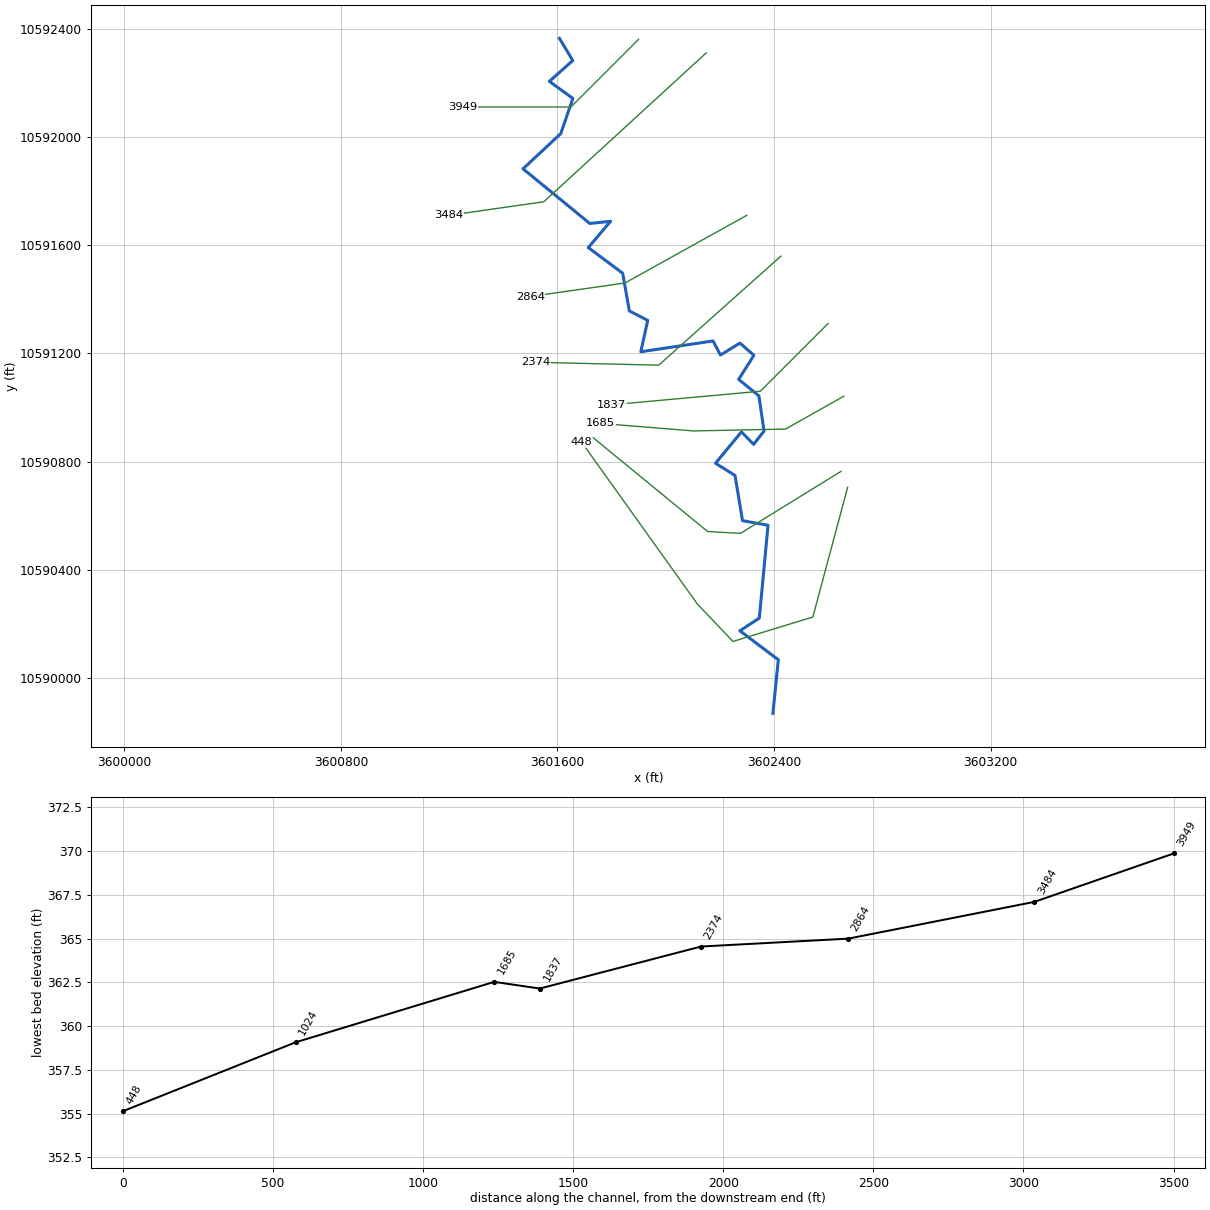
--- UNT 037 IN UKCR.prj (project) ---

Proj Title=UNT 037 IN UKCR Base Level Engineering
Current Plan=p01
Default Exp/Contr=0.3,0.1
English Units
Geom File=g01
Flow File=f01
Plan File=p01
Y Axis Title=Elevation
X Axis Title(PF)=Main Channel Distance
X Axis Title(XS)=Station
BEGIN DESCRIPTION:
UNT 037 IN UKCR
END DESCRIPTION:
DSS Export Rating Curves= 0
DSS Export Rating Curve Sorted= 0
DSS Export Volume Flow Curves= 0
DXF OffsetX= 0
DXF OffsetY= 0
DXF ScaleX= 1
DXF ScaleY= 10

--- UNT 037 IN UKCR.p01 (plan) ---

Plan Title=Multiple Run
Short Identifier=Multiple
Geom File=g01
Flow File=f01
Subcritical Flow
K Sum by GR= 0
Std Step Tol= 0.01
Critical Tol= 0.01
Num of Std Step Trials= 20
Max Error Tol= 0.3
Flow Tol Ratio= 0.001
Split Flow NTrial= 30
Split Flow Tol= 0.02
Split Flow Ratio= 0.02
Log Output Level= 0
Friction Slope Method= 1
Unsteady Friction Slope Method= 2
Unsteady Bridges Friction Slope Method= 1
Parabolic Critical Depth
Global Vel Dist=  1 , 1 , 1
Global Log Level= 0
CheckData=True
Encroach Param= -1, 0, 0, 0
BEGIN DESCRIPTION:
Multiple Run
END DESCRIPTION:

--- UNT 037 IN UKCR.f01 (steady flow) ---

Flow Title=Multiple
Number of Profiles=7
Profile Names=10-year,25-year,50-year,1pct_min,100-year,1pct_plu,500-year
River Rch & RM= UNT 037 IN UKCR,Reach-1,3949
     678     903    1084     951    1286    1739    1800
Boundary for River Rch & Prof#=UNT 037 IN UKCR,Reach-1,1
Up Type=0
Dn Type=3
Dn Slope=0.005
Boundary for River Rch & Prof#=UNT 037 IN UKCR,Reach-1,2
Up Type=0
Dn Type=3
Dn Slope=0.005
Boundary for River Rch & Prof#=UNT 037 IN UKCR,Reach-1,3
Up Type=0
Dn Type=3
Dn Slope=0.005
Boundary for River Rch & Prof#=UNT 037 IN UKCR,Reach-1,4
Up Type=0
Dn Type=3
Dn Slope=0.005
Boundary for River Rch & Prof#=UNT 037 IN UKCR,Reach-1,5
Up Type=0
Dn Type=3
Dn Slope=0.005
Boundary for River Rch & Prof#=UNT 037 IN UKCR,Reach-1,6
Up Type=0
Dn Type=3
Dn Slope=0.005
Boundary for River Rch & Prof#=UNT 037 IN UKCR,Reach-1,7
Up Type=0
Dn Type=3
Dn Slope=0.005

--- UNT 037 IN UKCR.g01 (geometry) ---

Geom Title=Existing Conditions
Program Version=4.10

River Reach=UNT 037 IN UKCR ,Reach-1
Reach XY= 30
      3601607.25       10592364.       3601656.5       10592282.
      3601570.25       10592205.        3601657.       10592142.
      3601612.25       10592012.      3601472.75       10591882.
       3601719.5       10591680.      3601796.25       10591688.
        3601714.       10591591.        3601841.       10591496.
       3601865.5       10591357.       3601933.5       10591322.
        3601908.       10591206.      3602174.75       10591246.
      3602202.25       10591194.      3602274.25       10591238.
      3602325.75       10591193.       3602269.5       10591104.
      3602344.25       10591043.      3602363.25       10590913.
      3602324.75       10590864.      3602279.75       10590910.
        3602184.       10590794.        3602256.       10590749.
      3602283.75       10590582.        3602378.       10590565.
      3602345.75       10590222.        3602274.       10590175.
        3602416.       10590068.        3602396.       10589870.

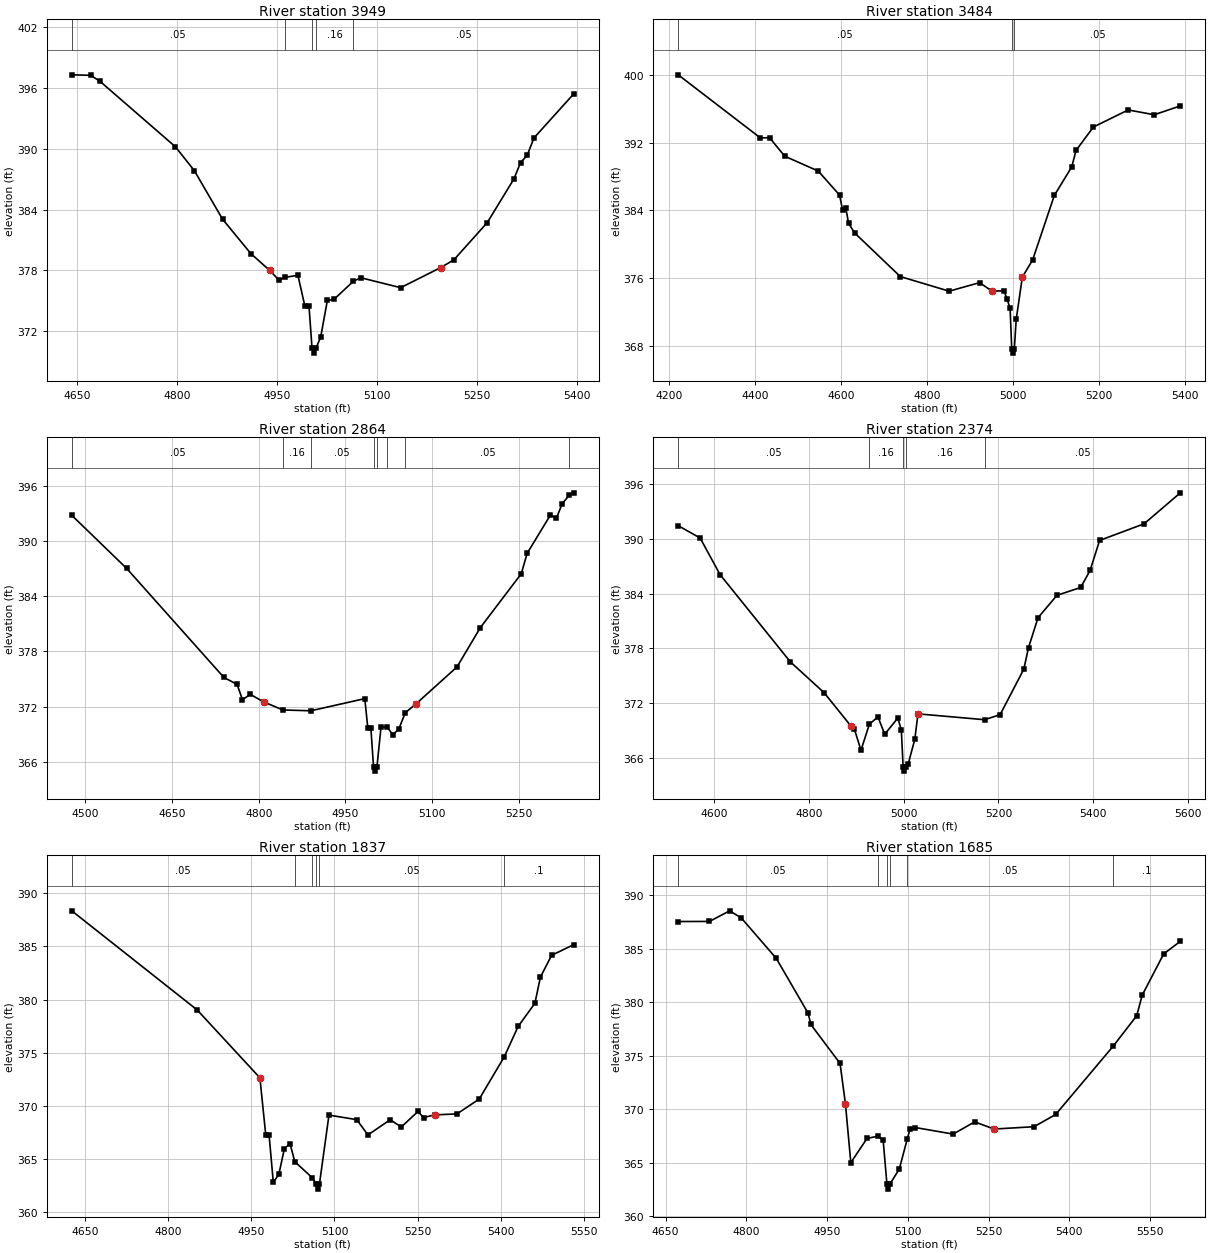
Type RM Length L Ch R = 1 ,3949    ,465,465,465
BEGIN DESCRIPTION:
UNT 037 IN UKCR 5.0
END DESCRIPTION:
XS GIS Cut Line= 3
      3601899.62      10592360.2      3601649.61     10592110.19
      3601249.58     10592110.19
#Sta/Elev= 30
  4641.7  397.25    4670   397.2  4684.1  396.61  4797.3  390.17  4825.6  387.83
    4868  383.05  4910.4  379.67  4938.7  378.01  4952.8  377.05  4961.3  377.32
  4981.1  377.53  4991.7  374.47  4997.8  374.47  5002.3  370.37    5005  369.87
  5008.3  370.37  5015.3  371.44  5025.3  375.05  5035.3  375.16  5064.2  376.93
  5075.3  377.29  5135.3  376.31  5195.3  378.28  5215.3  379.05  5265.3  382.71
  5305.3     387  5315.3  388.62  5325.3  389.33  5335.3  391.03  5395.3  395.39
#Mann= 5 ,-1 , 0
  4641.7     .05       0  4961.3     .16       0  5002.3     .07       0
  5008.3     .16       0  5064.2     .05       0
Bank Sta=4938.7,5195.3
XS Rating Curve= 0 ,0
Exp/Cntr=0.3,0.1

Type RM Length L Ch R = 1 ,3484    ,620,620,620
BEGIN DESCRIPTION:
UNT 037 IN UKCR 4.0
END DESCRIPTION:
XS GIS Cut Line= 3
      3602149.62      10592310.2      3601549.61     10591760.19
      3601199.61     10591710.19
#Sta/Elev= 30
    4221  400.07  4411.9   392.6  4433.4  392.62  4468.6  390.43  4546.6  388.67
  4596.2  385.82    4603  384.08  4610.4  384.34  4617.2  382.46  4631.4  381.33
  4737.4  376.17  4850.9  374.44  4921.8  375.45  4950.2  374.46  4978.5  374.47
  4985.3  373.55  4992.7  372.42  4996.5   367.6  4999.2   367.1  5002.5   367.6
  5006.9  371.09  5021.1   376.1  5045.1  378.14  5095.6  385.79    5136  389.16
  5146.1  391.12  5186.5  393.89  5267.3  395.91  5327.9  395.34  5388.5  396.39
#Mann= 3 ,-1 , 0
    4221     .05       0  4996.5     .03       0  5002.5     .05       0
Bank Sta=4950.2,5021.1
XS Rating Curve= 0 ,0
Exp/Cntr=0.3,0.1

Type RM Length L Ch R = 1 ,2864    ,490,490,490
BEGIN DESCRIPTION:
UNT 037 IN UKCR 3.0
END DESCRIPTION:
XS GIS Cut Line= 3
      3602299.64     10591710.21      3601849.61     10591460.19
      3601499.58     10591410.18
#Sta/Elev= 30
  4476.7  392.77  4571.7     387  4739.8  375.17  4762.7  374.41  4771.9  372.76
  4785.6  373.33  4808.5  372.52  4841.8  371.64  4890.1  371.55  4983.5  372.87
  4988.7  369.71    4994  369.71  4998.6   365.5  5001.4     365  5004.6   365.5
  5011.7  369.82  5022.1  369.79  5031.9  368.96    5042  369.53  5053.6  371.34
  5072.3  372.31    5143  376.31  5183.4  380.58  5254.2  386.43  5264.3  388.64
  5304.7  392.81  5314.8  392.43  5324.9  394.02  5337.5  394.98  5345.1  395.21
#Mann= 8 ,-1 , 0
  4476.7     .05       0  4841.8     .16       0  4890.1     .05       0
  4998.6     .03       0  5004.6     .05       0  5022.1     .16       0
  5053.6     .05       0  5337.5      .1       0
Bank Sta=4808.5,5072.3
XS Rating Curve= 0 ,0
Exp/Cntr=0.3,0.1

Type RM Length L Ch R = 1 ,2374    ,537,537,537
BEGIN DESCRIPTION:
Mapping XS 3c7578b9
END DESCRIPTION:
XS GIS Cut Line= 3
      3602425.48      10591559.3      3601974.12     10591156.55
      3601519.27     10591166.97
#Sta/Elev= 30
  4524.1  391.47  4570.4  390.11  4612.4   386.1    4761  376.52  4832.1  373.15
  4888.9  369.48  4895.6  369.21  4909.9  366.84  4927.6   369.7  4945.8   370.5
    4960  368.59  4987.7  370.38  4995.1  369.05  4998.8  365.05  5001.6  364.55
  5004.8  365.05  5009.3  365.29  5023.5  368.04  5030.2  370.83  5170.7  370.19
  5203.6  370.74  5253.6  375.73  5263.6   378.1  5283.6  381.37  5323.6  383.83
  5373.6  384.69  5393.6  386.56  5413.6  389.85  5507.5  391.67    5584  395.07
#Mann= 5 ,-1 , 0
  4524.1     .05       0  4927.6     .16       0  4998.8     .07       0
  5004.8     .16       0  5170.7     .05       0
Bank Sta=4888.9,5030.2
XS Rating Curve= 0 ,0
Exp/Cntr=0.3,0.1

Type RM Length L Ch R = 1 ,1837    ,152,152,152
BEGIN DESCRIPTION:
UNT 037 IN UKCR 2.0
END DESCRIPTION:
XS GIS Cut Line= 3
      3602599.58     10591310.16      3602349.61     10591060.19
      3601799.59     10591010.19
#Sta/Elev= 30
  4626.1  388.35  4852.3  379.02  4965.5  372.63  4976.1  367.23  4982.1  367.23
  4989.7  362.79  4999.7  363.54  5009.7  365.97  5019.8  366.43  5028.5  364.73
  5059.8  363.23    5067  362.65  5069.7  362.15    5073  362.65  5090.1  369.12
  5140.3  368.69  5160.4  367.25  5200.5  368.68  5220.6     368  5250.7  369.46
  5260.8  368.89  5280.9  369.14    5321  369.23  5361.2  370.63  5406.3   374.6
  5431.5  377.48  5461.6  379.64  5471.6  382.11  5491.7  384.16  5531.9  385.17
#Mann= 6 ,-1 , 0
  4626.1     .05       0  5028.5     .16       0  5059.8     .05       0
    5067     .03       0    5073     .05       0  5406.3      .1       0
Bank Sta=4965.5,5280.9
XS Rating Curve= 0 ,0
Exp/Cntr=0.3,0.1

Type RM Length L Ch R = 1 ,1685    ,661,661,661
BEGIN DESCRIPTION:
Mapping XS df11abcd
END DESCRIPTION:
XS GIS Cut Line= 4
      3602658.15     10591041.97      3602442.87     10590920.44
       3602102.6      10590913.5      3601758.88     10590941.27
#Sta/Elev= 30
  4673.6  387.52  4731.6  387.53  4769.1  388.52  4790.8  387.85  4855.8  384.07
    4915  378.94  4919.8  377.91  4974.1  374.27  4984.1   370.5  4994.1     365
  5024.1  367.26  5044.5  367.48  5054.1  367.12  5061.1  363.03  5063.9  362.53
  5067.1  363.03  5084.1   364.4  5098.8  367.19  5104.1  368.15  5114.1  368.28
  5184.1  367.67  5224.1  368.81  5260.2  368.14  5334.4  368.36  5374.5   369.5
  5481.5  375.89    5525  378.72  5535.3  380.65  5575.2   384.5    5606  385.67
#Mann= 6 ,-1 , 0
  4673.6     .05       0  5044.5     .16       0  5061.1     .03       0
  5067.1     .16       0  5098.8     .05       0  5481.5      .1       0
Bank Sta=4984.1,5260.2
XS Rating Curve= 0 ,0
Exp/Cntr=0.3,0.1

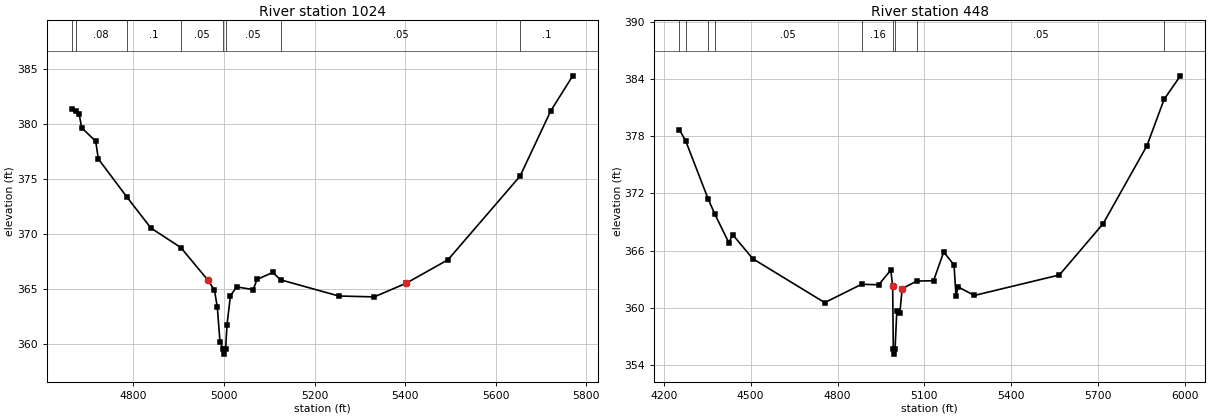
Type RM Length L Ch R = 1 ,1024    ,576,576,576
BEGIN DESCRIPTION:
Mapping XS 0a64a245
END DESCRIPTION:
XS GIS Cut Line= 4
      3602647.71     10590764.17      3602276.21     10590535.02
      3602154.68     10590541.97       3601731.1     10590889.16
#Sta/Elev= 30
  4664.1  381.43  4672.6  381.22  4680.4  380.95  4686.2  379.67    4717  378.46
  4722.9  376.84  4786.1  373.37  4838.8  370.56  4904.9  368.78  4964.2  365.84
  4979.1  364.91  4985.5  363.36  4991.4  360.17  4997.9  359.58  5000.6  359.08
  5003.9  359.58  5006.8   361.7  5014.3  364.38    5028   365.2  5064.7  364.95
  5073.1  365.88  5107.8  366.51  5125.3  365.84  5253.6  364.37  5331.8  364.29
  5402.2  365.53  5494.7  367.67  5653.7  375.28  5721.5  381.22    5770  384.41
#Mann= 8 ,-1 , 0
  4664.1     .05       0  4672.6     .08       0  4786.1      .1       0
  4904.9     .05       0  4997.9     .07       0  5003.9     .05       0
  5125.3     .05       0  5653.7      .1       0
Bank Sta=4964.2,5402.2
XS Rating Curve= 0 ,0
Exp/Cntr=0.3,0.1

Type RM Length L Ch R = 1 ,448     ,0,0,0
BEGIN DESCRIPTION:
UNT 037 IN UKCR 1.0
END DESCRIPTION:
XS GIS Cut Line= 5
      3602672.03     10590705.12      3602543.57       10590226.
      3602248.43     10590135.72      3602116.49     10590274.61
      3601689.39     10590871.85
#Sta/Elev= 30
  4253.6  378.67  4275.3  377.51  4352.7  371.43  4375.8  369.84  4424.4  366.83
  4438.3  367.65  4507.2  365.14  4755.7  360.54  4883.2  362.46    4942  362.41
  4983.9  363.94  4990.4  362.29  4992.6  355.64  4995.4  355.14  4998.6  355.64
  5004.8  359.71  5015.2  359.43  5023.2     362  5073.7   362.8  5131.5  362.83
  5166.7  365.84  5202.3  364.49  5209.2  361.25  5216.2  362.19  5272.7  361.29
  5566.4  363.44  5717.5  368.82  5868.6  376.98    5928  381.85  5984.1  384.31
#Mann= 9 ,-1 , 0
  4253.6     .05       0  4275.3     .08       0  4352.7      .1       0
  4375.8     .05       0  4883.2     .16       0  4992.6     .07       0
  4998.6     .16       0  5073.7     .05       0    5928      .1       0
Bank Sta=4990.4,5023.2
XS Rating Curve= 0 ,0
Exp/Cntr=0.3,0.1

Chan Stop Cuts=-1
Use User Specified Reach Order=0
Composite Channel Slope=5