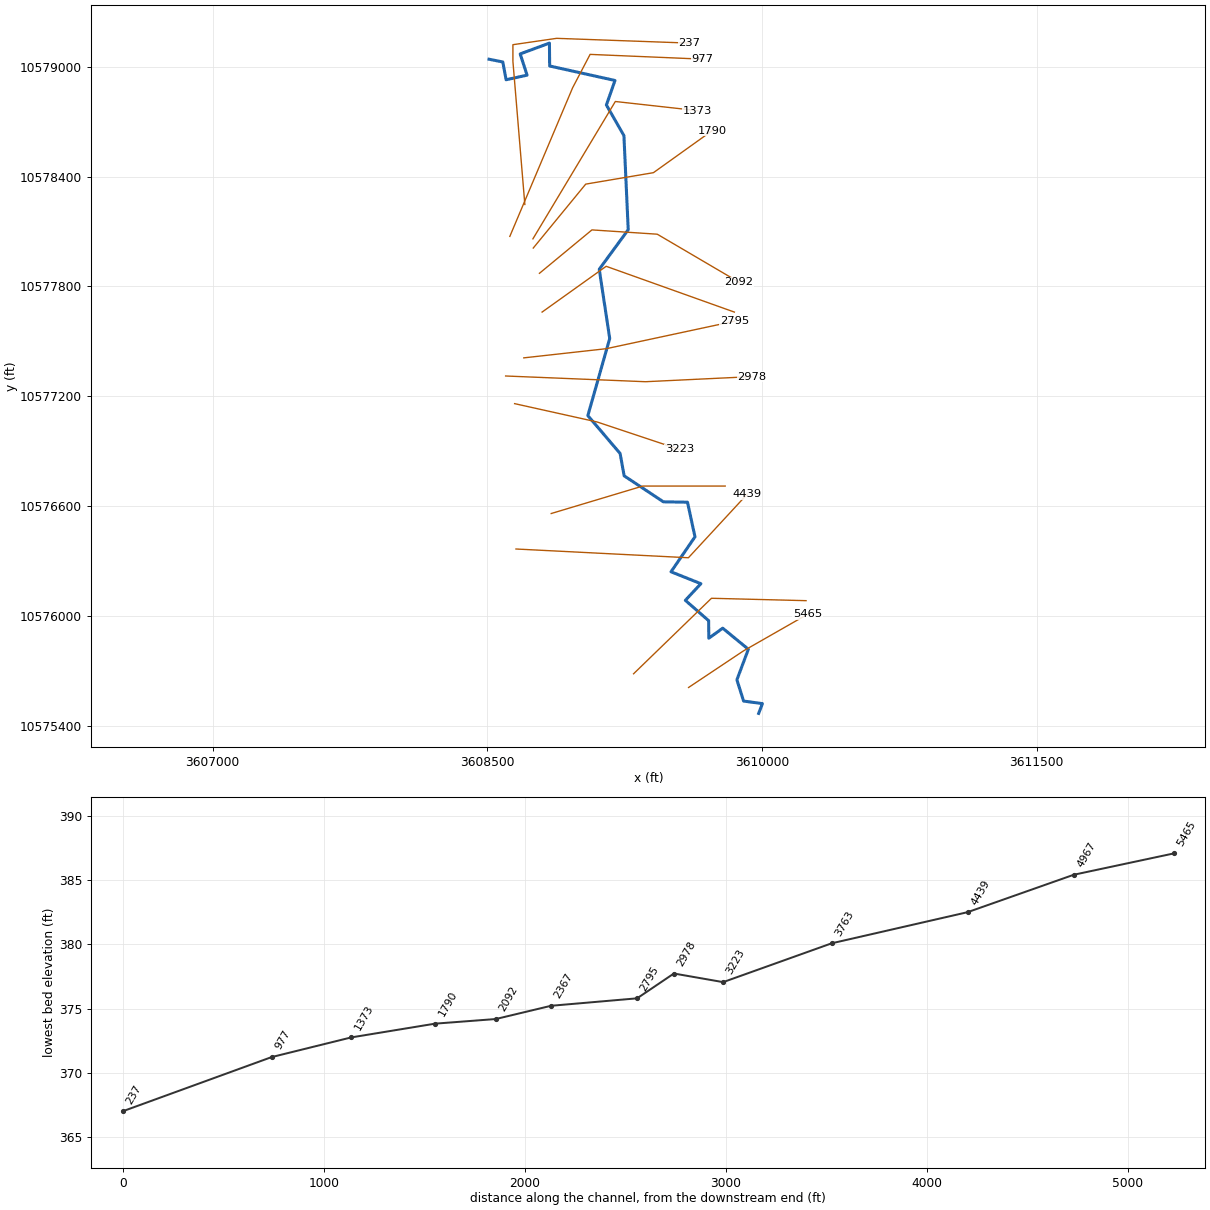
--- UNT 045 IN UKCR.prj (project) ---

Proj Title=UNT 045 IN UKCR Base Level Engineering
Current Plan=p01
Default Exp/Contr=0.3,0.1
English Units
Geom File=g01
Flow File=f01
Plan File=p01
BEGIN DESCRIPTION:
UNT 045 IN UKCR
END DESCRIPTION:

--- UNT 045 IN UKCR.p01 (plan) ---

Plan Title=Multiple Run
Short Identifier=Multiple
Geom File=g01
Flow File=f01
Subcritical Flow
K Sum by GR= 0
Std Step Tol= 0.01
Critical Tol= 0.01
Num of Std Step Trials= 20
Max Error Tol= 0.3
Flow Tol Ratio= 0.001
Split Flow NTrial= 30
Split Flow Tol= 0.02
Split Flow Ratio= 0.02
Log Output Level= 0
Friction Slope Method= 1
Unsteady Friction Slope Method= 2
Unsteady Bridges Friction Slope Method= 1
Parabolic Critical Depth
Global Vel Dist=  1 , 1 , 1
Global Log Level= 0
CheckData=True
Encroach Param= -1, 0, 0, 0
BEGIN DESCRIPTION:
Multiple Run
END DESCRIPTION:

--- UNT 045 IN UKCR.f01 (steady flow) ---

Flow Title=Multiple
Number of Profiles=7
Profile Names=10-year,25-year,50-year,1pct_min,100-year,1pct_plu,500-year
River Rch & RM= UNT 045 IN UKCR,Reach-1,5465
    1187    1649    2035    1833    2479    3353    3667
River Rch & RM= UNT 045 IN UKCR,Reach-1,3763
    1881    2673    3349    3058    4136    5593    6288
Boundary for River Rch & Prof#=UNT 045 IN UKCR,Reach-1,1
Up Type=0
Dn Type=3
Dn Slope=0.005
Boundary for River Rch & Prof#=UNT 045 IN UKCR,Reach-1,2
Up Type=0
Dn Type=3
Dn Slope=0.005
Boundary for River Rch & Prof#=UNT 045 IN UKCR,Reach-1,3
Up Type=0
Dn Type=3
Dn Slope=0.005
Boundary for River Rch & Prof#=UNT 045 IN UKCR,Reach-1,4
Up Type=0
Dn Type=3
Dn Slope=0.005
Boundary for River Rch & Prof#=UNT 045 IN UKCR,Reach-1,5
Up Type=0
Dn Type=3
Dn Slope=0.005
Boundary for River Rch & Prof#=UNT 045 IN UKCR,Reach-1,6
Up Type=0
Dn Type=3
Dn Slope=0.005
Boundary for River Rch & Prof#=UNT 045 IN UKCR,Reach-1,7
Up Type=0
Dn Type=3
Dn Slope=0.005

--- UNT 045 IN UKCR.g01 (geometry) ---

Geom Title=Existing Conditions

River Reach=UNT 045 IN UKCR,Reach-1
Reach XY= 30
      3609982.30     10575468.78      3610003.00     10575522.00
      3609900.00     10575536.00      3609863.50     10575652.00
      3609926.00     10575819.00      3609786.00     10575934.00
      3609710.00     10575879.00      3609709.25     10575975.00
      3609582.00     10576086.00      3609666.75     10576177.00
      3609503.75     10576242.00      3609634.50     10576433.00
      3609593.75     10576622.00      3609462.25     10576624.00
      3609247.75     10576766.00      3609225.75     10576888.00
      3609049.50     10577095.00      3609169.00     10577516.00
      3609111.75     10577894.00      3609270.00     10578110.00
      3609246.50     10578624.00      3609150.75     10578791.00
      3609197.75     10578925.00      3608841.00     10579004.00
      3608839.75     10579129.00      3608680.00     10579070.00
      3608717.75     10578954.00      3608603.00     10578929.00
      3608585.25     10579026.00      3608510.25     10579041.00

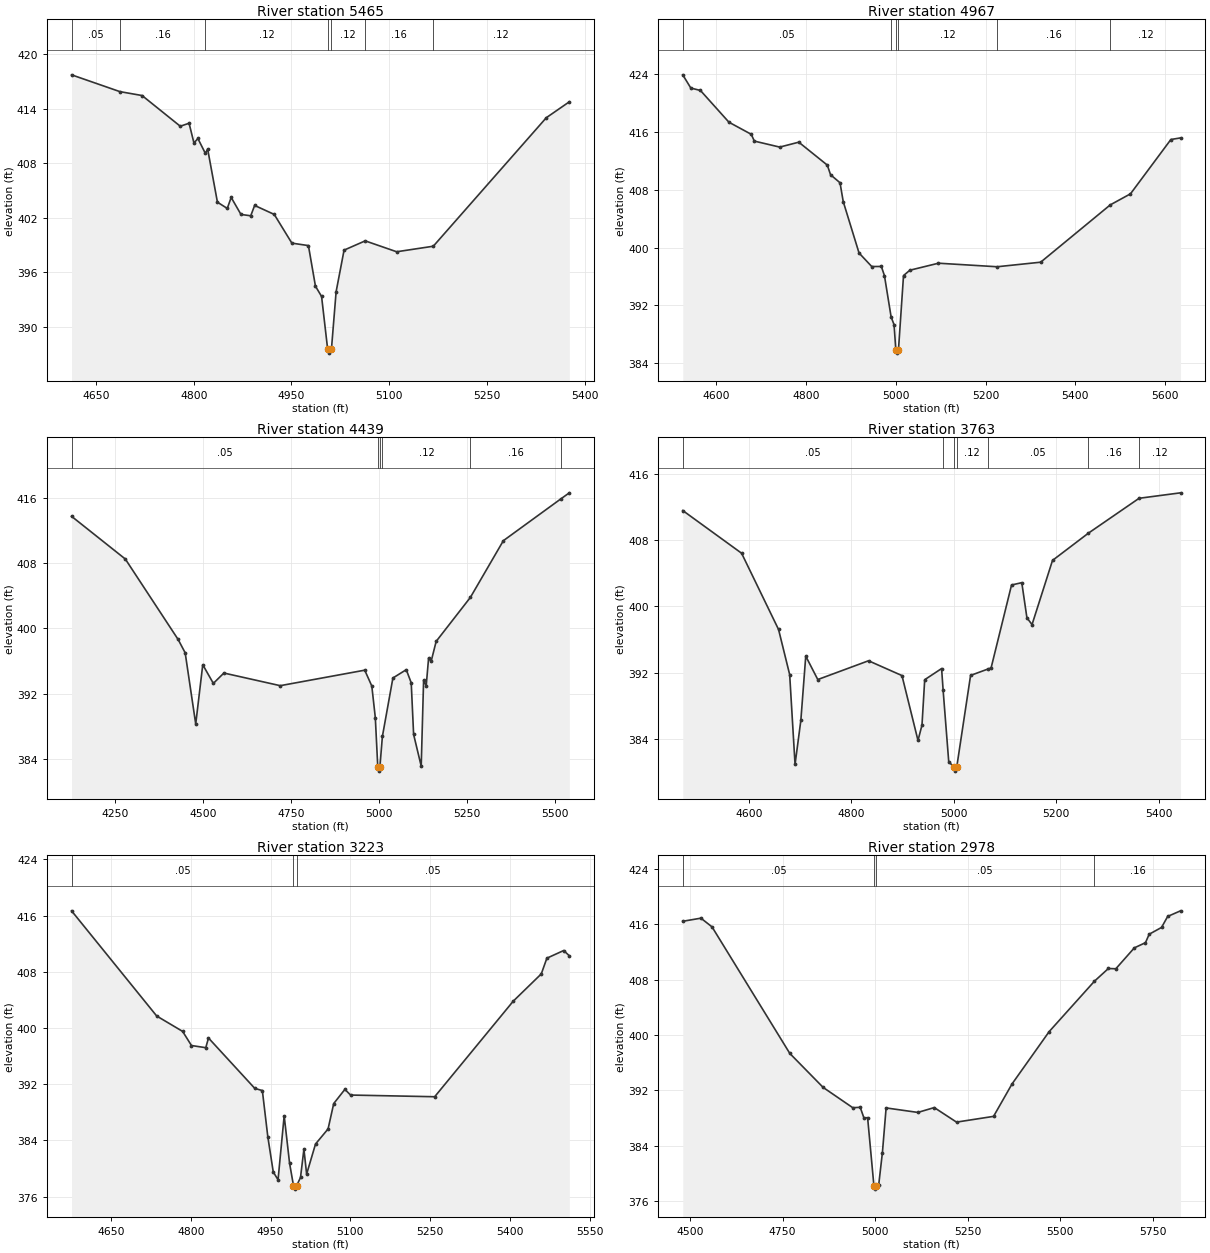
Type RM Length L Ch R = 1,5465,498,498,498
BEGIN DESCRIPTION:
UNT 045 IN UKCR 10.0
END DESCRIPTION:
XS GIS Cut Line= 3
      3609599.61     10575610.19      3609899.61     10575810.19
      3610249.64     10576010.20
#Sta/Elev= 30
  4612.6  417.71  4686.8  415.86  4720.8  415.43  4779.4  412.05  4792.9  412.38
  4800.4  410.20  4806.4  410.70  4817.9  409.06  4821.4  409.54  4836.4  403.69
  4851.5  403.00  4857.5  404.21  4872.5  402.34  4887.5  402.19  4893.5  403.33
  4923.6  402.34  4950.6  399.18  4976.0  398.91  4986.8  394.44  4996.2  393.31
  5005.4  387.57  5008.2  387.07  5011.4  387.57  5018.5  393.83  5030.7  398.41
  5063.1  399.43  5111.4  398.23  5167.6  398.84  5341.0  412.99  5376.3  414.74
#Mann=7,-1,0
  4612.6    0.05       0  4686.8    0.16       0  4817.9    0.12       0
  5005.4    0.07       0  5011.4    0.12       0  5063.1    0.16       0
  5167.6    0.12       0
Bank Sta=5005.4,5011.4
Exp/Cntr=0.3,0.1

Type RM Length L Ch R = 1,4967,528,528,528
BEGIN DESCRIPTION:
UNT 045 IN UKCR 9.0
END DESCRIPTION:
XS GIS Cut Line= 3
      3609299.24     10575684.97      3609724.61     10576097.32
      3610241.12     10576084.29
#Sta/Elev= 30
  4525.1  423.88  4543.1  422.05  4564.5  421.72  4628.0  417.33  4677.7  415.66
  4684.6  414.72  4741.2  413.89  4783.6  414.57  4847.2  411.40  4854.4  410.07
  4875.5  408.96  4882.7  406.35  4917.9  399.25  4946.2  397.38  4967.6  397.39
  4974.5  396.12  4989.4  390.40  4995.9  389.35  4999.8  385.91  5002.6  385.41
  5005.8  385.91  5017.0  396.13  5031.1  396.87  5094.9  397.84  5225.5  397.35
  5322.6  397.98  5477.6  405.90  5522.7  407.43  5612.7  414.94  5634.2  415.16
#Mann=6,-1,0
  4525.1    0.05       0  4989.4    0.12       0  4999.8    0.07       0
  5005.8    0.12       0  5225.5    0.16       0  5477.6    0.12       0
Bank Sta=4999.8,5005.8
Exp/Cntr=0.3,0.1

Type RM Length L Ch R = 1,4439,676,676,676
BEGIN DESCRIPTION:
UNT 045 IN UKCR 8.0
END DESCRIPTION:
XS GIS Cut Line= 3
      3608656.95     10576366.41      3609598.74     10576318.67
      3609919.59     10576665.53
#Sta/Elev= 30
  4126.0  413.75  4278.9  408.51  4429.0  398.65  4449.1  397.01  4479.1  388.28
  4499.1  395.55  4529.2  393.26  4559.2  394.53  4719.4  392.98  4959.7  394.88
  4979.8  392.94  4989.8  389.06  4996.8  383.00  4999.5  382.50  5002.8  383.00
  5009.9  386.75  5039.8  393.92  5077.8  394.94  5091.9  393.33  5098.7  387.00
  5120.3  383.11  5127.1  393.65  5134.5  392.96  5141.3  396.37  5148.6  395.97
  5162.8  398.41  5260.2  403.81  5353.9  410.76  5516.5  415.86  5541.5  416.63
#Mann=6,-1,0
  4126.0    0.05       0  4996.8    0.03       0  5002.8    0.05       0
  5009.9    0.12       0  5260.2    0.16       0  5516.5    0.07       0
Bank Sta=4996.8,5002.8
Exp/Cntr=0.3,0.1

Type RM Length L Ch R = 1,3763,540,540,540
BEGIN DESCRIPTION:
UNT 045 IN UKCR 7.0
END DESCRIPTION:
XS GIS Cut Line= 3
      3608849.57     10576560.18      3609349.61     10576710.19
      3609799.65     10576710.19
#Sta/Elev= 30
  4470.5  411.58  4585.4  406.42  4657.6  397.20  4679.3  391.75  4689.8  380.89
  4701.1  386.20  4710.7  393.98  4734.2  391.15  4833.3  393.42  4898.6  391.63
  4929.9  383.79  4937.7  385.64  4943.0  391.13  4976.0  392.48  4979.0  389.85
  4989.9  381.24  4999.6  380.58  5002.3  380.08  5005.6  380.58  5032.6  391.65
  5066.5  392.42  5072.6  392.54  5112.6  402.58  5132.6  402.86  5142.6  398.62
  5152.6  397.79  5192.6  405.55  5262.8  408.85  5361.7  413.06  5442.6  413.72
#Mann=7,-1,0
  4470.5    0.05       0  4979.0    0.12       0  4999.6    0.07       0
  5005.6    0.12       0  5066.5    0.05       0  5262.8    0.16       0
  5361.7    0.12       0
Bank Sta=4999.6,5005.6
Exp/Cntr=0.3,0.1

Type RM Length L Ch R = 1,3223,245,245,245
BEGIN DESCRIPTION:
UNT 045 IN UKCR 6.0
END DESCRIPTION:
XS GIS Cut Line= 3
      3608649.64     10577160.18      3609099.61     10577060.19
      3609549.63     10576910.18
#Sta/Elev= 30
  4576.0  416.67  4736.0  401.70  4784.7  399.51  4801.3  397.50  4828.2  397.19
  4833.3  398.57  4920.4  391.39  4934.5  391.09  4944.7  384.55  4955.0  379.50
  4964.0  378.39  4975.5  387.50  4985.7  380.72  4993.0  377.56  4995.7  377.06
  4999.0  377.56  5006.2  378.72  5012.6  382.75  5017.7  379.20  5034.4  383.48
  5058.0  385.63  5068.6  389.24  5089.6  391.26  5100.2  390.45  5258.3  390.21
  5405.9  403.81  5458.6  407.69  5469.1  409.93  5500.7  411.02  5511.3  410.27
#Mann=3,-1,0
  4576.0    0.05       0  4993.0    0.03       0  4999.0    0.05       0
Bank Sta=4993,4999
Exp/Cntr=0.3,0.1

Type RM Length L Ch R = 1,2978,183,183,183
BEGIN DESCRIPTION:
Mapping XS fb2927f1
END DESCRIPTION:
XS GIS Cut Line= 3
      3608600.54     10577311.19      3609364.41     10577279.94
      3609944.24     10577307.72
#Sta/Elev= 30
  4480.1  416.42  4529.2  416.87  4559.2  415.61  4769.4  397.33  4859.5  392.42
  4939.5  389.49  4959.6  389.55  4969.6  388.02  4979.6  388.05  4996.6  378.23
  4999.4  377.73  5002.6  378.23  5009.6  378.36  5019.6  383.02  5029.6  389.46
  5115.4  388.81  5159.7  389.51  5219.8  387.41  5319.9  388.24  5369.9  392.93
  5470.1  400.48  5592.6  407.77  5630.2  409.60  5650.3  409.56  5700.3  412.58
  5730.4  413.33  5740.4  414.55  5773.8  415.53  5790.4  417.12  5825.1  417.93
#Mann=4,-1,0
  4480.1    0.05       0  4996.6    0.03       0  5002.6    0.05       0
  5592.6    0.16       0
Bank Sta=4996.6,5002.6
Exp/Cntr=0.3,0.1

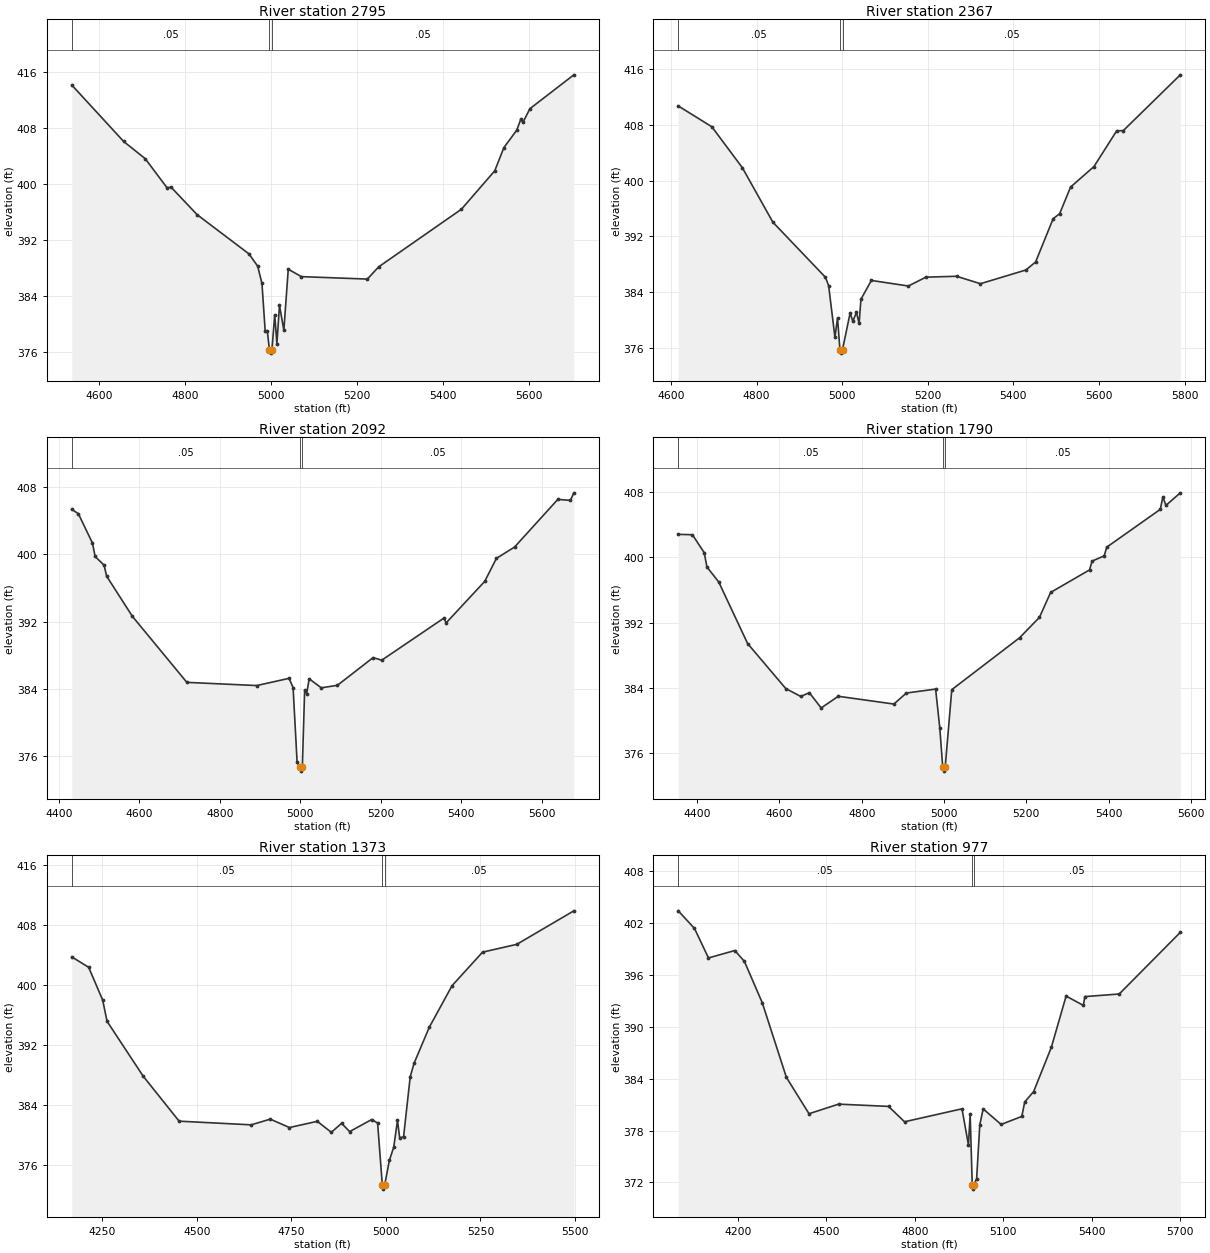
Type RM Length L Ch R = 1,2795,428,428,428
BEGIN DESCRIPTION:
UNT 045 IN UKCR 5.0
END DESCRIPTION:
XS GIS Cut Line= 3
      3608699.58     10577410.19      3609149.61     10577460.19
      3609849.62     10577610.19
#Sta/Elev= 30
  4536.5  414.18  4657.3  406.10  4707.6  403.63  4757.9  399.50  4767.9  399.54
  4828.3  395.62  4949.1  390.00  4969.2  388.25  4979.2  385.78  4986.8  378.91
  4991.9  378.91  4996.5  376.30  4999.3  375.80  5002.5  376.30  5008.9  381.30
  5014.0  377.17  5020.0  382.64  5030.2  379.07  5040.4  387.81  5071.1  386.75
  5224.5  386.40  5250.9  388.15  5443.5  396.40  5521.1  401.90  5542.4  405.23
  5572.2  407.70  5581.6  409.26  5586.7  408.83  5602.9  410.79  5705.2  415.64
#Mann=3,-1,0
  4536.5    0.05       0  4996.5    0.03       0  5002.5    0.05       0
Bank Sta=4996.5,5002.5
Exp/Cntr=0.3,0.1

Type RM Length L Ch R = 1,2367,275,275,275
BEGIN DESCRIPTION:
UNT 045 IN UKCR 4.0
END DESCRIPTION:
XS GIS Cut Line= 3
      3608799.62     10577660.20      3609149.61     10577910.19
      3609849.60     10577660.19
#Sta/Elev= 30
  4616.8  410.76  4695.4  407.76  4766.7  401.87  4838.0  394.04  4960.9  386.12
  4968.3  384.91  4983.0  377.51  4989.1  380.26  4994.7  375.72  4997.5  375.22
  5000.7  375.72  5018.6  381.01  5024.8  379.80  5033.4  381.09  5039.5  379.48
  5043.8  382.96  5068.1  385.67  5154.7  384.87  5195.6  386.14  5267.2  386.27
  5323.0  385.20  5429.2  387.17  5452.0  388.32  5492.9  394.53  5508.3  395.28
  5533.8  399.10  5588.5  402.05  5641.5  407.18  5656.9  407.21  5790.2  415.23
#Mann=3,-1,0
  4616.8    0.05       0  4994.7    0.03       0  5000.7    0.05       0
Bank Sta=4994.7,5000.7
Exp/Cntr=0.3,0.1

Type RM Length L Ch R = 1,2092,302,302,302
BEGIN DESCRIPTION:
Mapping XS 9adc9372
END DESCRIPTION:
XS GIS Cut Line= 4
      3608785.33     10577872.02      3609071.78     10578108.99
      3609428.55     10578085.55      3609875.57     10577823.06
#Sta/Elev= 30
  4432.0  405.36  4448.4  404.84  4483.5  401.34  4490.0  399.75  4512.2  398.72
  4518.7  397.40  4582.5  392.63  4718.0  384.76  4891.8  384.38  4972.0  385.24
  4982.0  384.14  4992.0  375.25  4999.0  374.69  5001.8  374.19  5005.0  374.69
  5010.7  383.81  5015.7  383.42  5022.1  385.18  5052.1  384.11  5092.2  384.41
  5180.9  387.71  5202.3  387.40  5356.7  392.41  5362.5  391.85  5458.3  396.79
  5487.2  399.52  5532.5  400.88  5639.9  406.55  5671.2  406.43  5679.7  407.33
#Mann=3,-1,0
  4432.0    0.05       0  4999.0    0.03       0  5005.0    0.05       0
Bank Sta=4999,5005
Exp/Cntr=0.3,0.1

Type RM Length L Ch R = 1,1790,417,417,417
BEGIN DESCRIPTION:
UNT 045 IN UKCR 3.0
END DESCRIPTION:
XS GIS Cut Line= 4
      3608751.45     10578010.02      3609037.92     10578358.99
      3609407.72     10578421.49      3609728.04     10578650.67
#Sta/Elev= 30
  4353.9  402.81  4388.4  402.76  4417.1  400.56  4423.6  398.82  4452.3  396.98
  4522.6  389.44  4615.2  383.94  4651.7  382.97  4672.6  383.43  4701.3  381.56
  4742.9  382.99  4878.1  382.04  4908.5  383.39  4979.5  383.87  4989.7  379.10
  4996.8  374.33  4999.6  373.83  5002.8  374.33  5018.8  383.80  5183.6  390.15
  5231.9  392.65  5259.1  395.70  5353.7  398.46  5359.8  399.53  5389.3  400.18
  5395.5  401.24  5525.7  405.87  5531.9  407.39  5539.3  406.35  5574.3  407.89
#Mann=3,-1,0
  4353.9    0.05       0  4996.8    0.03       0  5002.8    0.05       0
Bank Sta=4996.8,5002.8
Exp/Cntr=0.3,0.1

Type RM Length L Ch R = 1,1373,396,396,396
BEGIN DESCRIPTION:
UNT 045 IN UKCR 2.0
END DESCRIPTION:
XS GIS Cut Line= 3
      3608749.59     10578060.16      3609199.61     10578810.19
      3609649.57     10578760.19
#Sta/Elev= 30
  4169.4  403.72  4214.1  402.33  4251.1  397.96  4262.7  395.13  4358.0  387.83
  4453.2  381.82  4643.7  381.33  4694.2  382.09  4744.8  380.97  4818.6  381.80
  4855.5  380.33  4882.7  381.53  4904.1  380.43  4962.4  382.04  4978.0  381.57
  4990.5  373.26  4993.3  372.76  4996.5  373.26  5009.1  376.59  5020.7  378.37
  5030.5  381.91  5036.3  379.60  5046.6  379.73  5064.2  387.74  5074.3  389.53
  5114.5  394.33  5174.9  399.89  5255.4  404.35  5345.9  405.39  5496.8  409.86
#Mann=3,-1,0
  4169.4    0.05       0  4990.5    0.03       0  4996.5    0.05       0
Bank Sta=4990.5,4996.5
Exp/Cntr=0.3,0.1

Type RM Length L Ch R = 1,977,740,740,740
BEGIN DESCRIPTION:
Mapping XS a5e75b19
END DESCRIPTION:
XS GIS Cut Line= 4
      3608623.52     10578073.54      3608966.39     10578885.14
      3609061.88     10579067.43      3609676.39     10579041.47
#Sta/Elev= 30
  3997.9  403.42  4053.0  401.38  4100.4  397.97  4189.7  398.83  4222.2  397.57
  4282.6  392.80  4364.6  384.15  4441.2  379.95  4541.4  381.06  4710.7  380.80
  4765.0  379.02  4959.7  380.52  4981.7  376.33  4987.4  379.90  4994.5  371.73
  4997.3  371.23  5000.5  371.73  5009.4  372.45  5020.1  378.66  5031.5  380.51
  5092.5  378.71  5162.5  379.64  5172.5  381.32  5202.6  382.51  5262.6  387.63
  5312.7  393.56  5371.2  392.48  5376.2  393.50  5492.8  393.80  5699.8  400.93
#Mann=3,-1,0
  3997.9    0.05       0  4994.5    0.03       0  5000.5    0.05       0
Bank Sta=4994.5,5000.5
Exp/Cntr=0.3,0.1

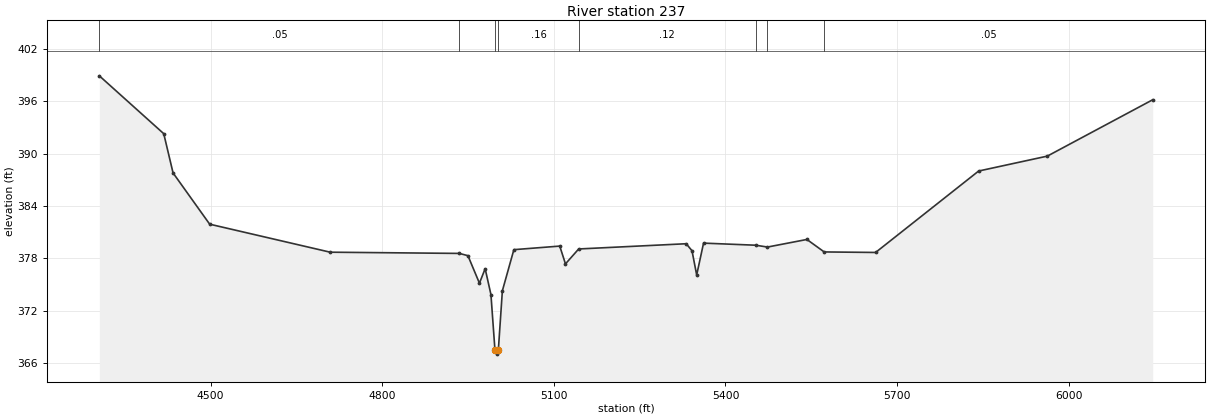
Type RM Length L Ch R = 1,237,0,0,0
BEGIN DESCRIPTION:
UNT 045 IN UKCR 1.0
END DESCRIPTION:
XS GIS Cut Line= 5
      3608705.41     10578247.98      3608640.31     10579029.24
      3608640.31     10579120.39      3608879.03     10579155.11
      3609603.82     10579129.07
#Sta/Elev= 30
  4305.4  398.91  4418.0  392.28  4434.3  387.78  4498.3  381.91  4709.0  378.70
  4934.9  378.56  4949.8  378.30  4969.9  375.15  4979.9  376.81  4990.0  373.85
  4997.0  367.52  4999.8  367.02  5003.0  367.52  5010.0  374.28  5030.1  378.99
  5110.3  379.40  5120.3  377.36  5143.4  379.07  5331.4  379.67  5341.5  378.87
  5349.7  376.09  5361.7  379.74  5452.8  379.50  5473.5  379.29  5542.4  380.16
  5572.6  378.73  5662.5  378.67  5842.6  388.00  5962.7  389.71  6147.0  396.17
#Mann=8,-1,0
  4305.4    0.05       0  4934.9    0.16       0  4997.0    0.07       0
  5003.0    0.16       0  5143.4    0.12       0  5452.8    0.16       0
  5473.5    0.12       0  5572.6    0.05       0
Bank Sta=4997,5003
Exp/Cntr=0.3,0.1

Chan Stop Cuts=-1