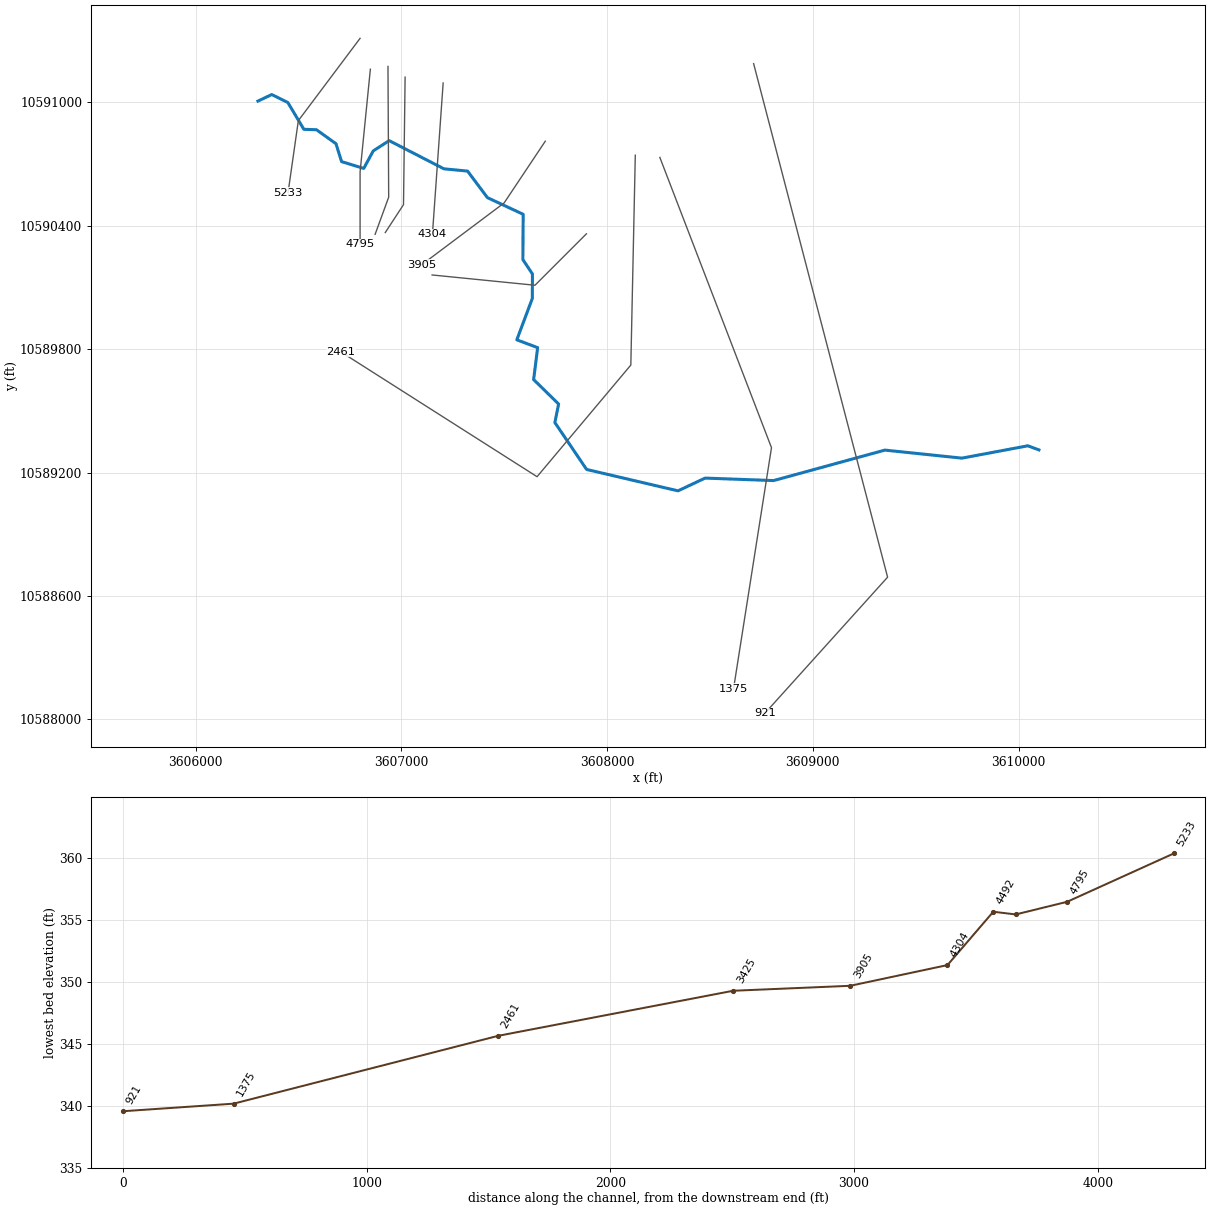
--- UNT 049 IN UKCR.prj (project) ---

Proj Title=UNT 049 IN UKCR Base Level Engineering
Current Plan=p01
Default Exp/Contr=0.3,0.1
English Units
Geom File=g01
Flow File=f01
Plan File=p01
Y Axis Title=Elevation
X Axis Title(PF)=Main Channel Distance
X Axis Title(XS)=Station
BEGIN DESCRIPTION:
UNT 049 IN UKCR
END DESCRIPTION:
DSS Export Rating Curves= 0
DSS Export Rating Curve Sorted= 0
DSS Export Volume Flow Curves= 0
DXF OffsetX= 0
DXF OffsetY= 0
DXF ScaleX= 1
DXF ScaleY= 10

--- UNT 049 IN UKCR.p01 (plan) ---

Plan Title=Multiple Run
Short Identifier=Multiple
Geom File=g01
Flow File=f01
Subcritical Flow
K Sum by GR= 0
Std Step Tol= 0.01
Critical Tol= 0.01
Num of Std Step Trials= 20
Max Error Tol= 0.3
Flow Tol Ratio= 0.001
Split Flow NTrial= 30
Split Flow Tol= 0.02
Split Flow Ratio= 0.02
Log Output Level= 0
Friction Slope Method= 1
Unsteady Friction Slope Method= 2
Unsteady Bridges Friction Slope Method= 1
Parabolic Critical Depth
Global Vel Dist=  1 , 1 , 1
Global Log Level= 0
CheckData=True
Encroach Param= -1, 0, 0, 0
BEGIN DESCRIPTION:
Multiple Run
END DESCRIPTION:

--- UNT 049 IN UKCR.f01 (steady flow) ---

Flow Title=Multiple
Number of Profiles=7
Profile Names=10-year,25-year,50-year,1pct_min,100-year,1pct_plu,500-year
River Rch & RM= UNT 049 IN UKCR,Reach-1,5233
     746     999    1202    1057    1430    1934    2013
Boundary for River Rch & Prof#=UNT 049 IN UKCR,Reach-1,1
Up Type=0
Dn Type=3
Dn Slope=0.005
Boundary for River Rch & Prof#=UNT 049 IN UKCR,Reach-1,2
Up Type=0
Dn Type=3
Dn Slope=0.005
Boundary for River Rch & Prof#=UNT 049 IN UKCR,Reach-1,3
Up Type=0
Dn Type=3
Dn Slope=0.005
Boundary for River Rch & Prof#=UNT 049 IN UKCR,Reach-1,4
Up Type=0
Dn Type=3
Dn Slope=0.005
Boundary for River Rch & Prof#=UNT 049 IN UKCR,Reach-1,5
Up Type=0
Dn Type=3
Dn Slope=0.005
Boundary for River Rch & Prof#=UNT 049 IN UKCR,Reach-1,6
Up Type=0
Dn Type=3
Dn Slope=0.005
Boundary for River Rch & Prof#=UNT 049 IN UKCR,Reach-1,7
Up Type=0
Dn Type=3
Dn Slope=0.005

--- UNT 049 IN UKCR.g01 (geometry) ---

Geom Title=Existing Conditions
Program Version=4.10

River Reach=UNT 049 IN UKCR ,Reach-1
Reach XY= 30
        3606303.       10591005.      3606370.25       10591037.
      3606448.75       10590998.      3606526.25       10590868.
      3606587.75       10590866.       3606682.5       10590798.
      3606709.75       10590711.       3606817.5       10590678.
       3606863.5       10590763.        3606941.       10590813.
      3607207.25       10590676.        3607322.       10590665.
       3607418.5       10590536.      3607592.25       10590455.
      3607590.75       10590235.      3607637.25       10590165.
      3607636.75       10590046.      3607561.25       10589845.
       3607662.5       10589807.        3607643.       10589652.
       3607764.5       10589533.      3607746.25       10589443.
       3607900.5       10589215.      3608344.75       10589111.
      3608476.25       10589173.       3608809.5       10589161.
        3609350.       10589309.       3609724.5       10589270.
      3610044.75       10589330.      3610098.75       10589310.

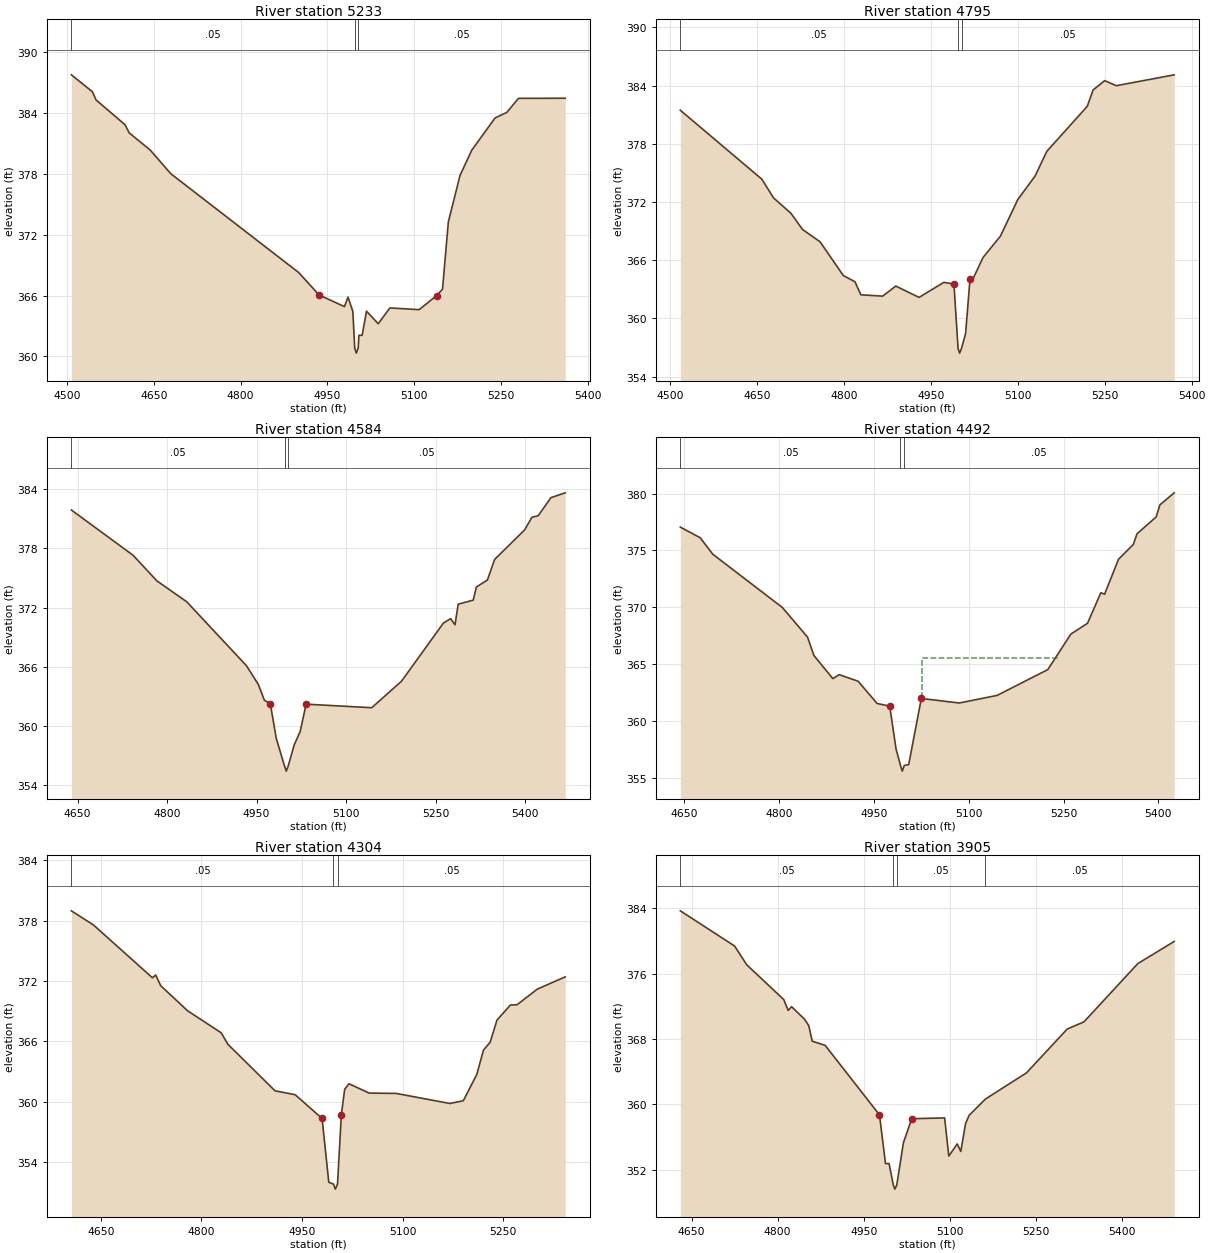
Type RM Length L Ch R = 1 ,5233    ,438,438,438
BEGIN DESCRIPTION:
UNT 049 IN UKCR 8.0
END DESCRIPTION:
XS GIS Cut Line= 3
       3606799.6     10591310.17      3606499.61     10590910.19
      3606449.61     10590560.22
#Sta/Elev= 30
  4507.7  387.79  4544.1  386.12  4550.4  385.31  4600.4  382.87  4607.7  382.06
  4644.1  380.36  4679.6  378.03  4900.4  368.29  4935.8  366.07  4979.6  364.92
  4985.8  365.86  4994.1  364.45  4997.4  360.83  5000.1  360.33  5003.4  360.83
  5004.6  362.09  5010.2  362.09  5017.8  364.47    5038  363.23  5058.2  364.79
  5108.7  364.62    5139  366.01  5149.1  366.64  5159.2  373.28  5179.4  377.87
  5199.6  380.35    5240  383.54  5260.2  384.08  5280.4  385.47  5361.2  385.48
#Mann= 3 ,-1 , 0
  4507.7     .05       0  4997.4     .03       0  5003.4     .05       0
Bank Sta=4935.8,5139
XS Rating Curve= 0 ,0
Exp/Cntr=0.3,0.1

Type RM Length L Ch R = 1 ,4795    ,211,211,211
BEGIN DESCRIPTION:
UNT 049 IN UKCR 7.0
END DESCRIPTION:
XS GIS Cut Line= 3
      3606849.61     10591160.19      3606799.61     10590660.19
      3606799.61     10590310.19
#Sta/Elev= 30
  4517.4  381.45  4658.1  374.35  4678.2  372.43  4708.4  370.83  4728.5  369.16
  4758.6   367.9  4798.8  364.42  4818.9  363.78    4829  362.44  4866.6   362.3
  4889.3  363.34  4929.5  362.17  4972.2  363.72  4989.7  363.54  4996.8  356.93
  4999.5  356.43  5002.8  356.93  5009.8  358.44  5017.4  364.06  5022.4  364.06
  5039.9  366.28  5069.9  368.48  5099.9  372.25  5129.9  374.69  5149.9  377.21
  5219.9  381.86  5229.9  383.54  5249.9   384.5  5269.9  383.98  5369.9   385.1
#Mann= 3 ,-1 , 0
  4517.4     .05       0  4996.8     .03       0  5002.8     .05       0
Bank Sta=4989.7,5017.4
XS Rating Curve= 0 ,0
Exp/Cntr=0.3,0.1

Type RM Length L Ch R = 1 ,4584    ,92,92,92
BEGIN DESCRIPTION:
Mapping XS e60aa765
END DESCRIPTION:
XS GIS Cut Line= 3
      3606935.16     10591173.59      3606938.63     10590538.19
      3606872.67     10590357.67
#Sta/Elev= 30
  4639.7  381.89  4743.1   377.3  4783.1   374.7  4833.1  372.58  4933.1   366.1
  4953.1  364.19  4963.1   362.6  4973.1  362.25  4983.1  358.72    4997  355.91
  4999.8  355.41    5003  355.91  5013.1  358.07  5023.1  359.42  5033.1   362.2
  5143.1  361.84  5193.1  364.54  5263.1  370.42  5275.1  370.87  5282.6  370.25
  5287.9  372.34  5313.1  372.75  5318.4  374.08  5336.9  374.79    5349  376.88
  5399.4  379.88  5411.4  381.15    5422  381.31  5443.3  383.14  5467.3  383.63
#Mann= 3 ,-1 , 0
  4639.7     .05       0    4997     .03       0    5003     .05       0
Bank Sta=4973.1,5033.1
XS Rating Curve= 0 ,0
Exp/Cntr=0.3,0.1

Type RM Length L Ch R = 1 ,4492    ,188,188,188
BEGIN DESCRIPTION:
UNT 049 IN UKCR 6.0
END DESCRIPTION:
XS GIS Cut Line= 3
      3607018.44     10591121.61      3607010.62     10590501.86
      3606922.08     10590366.43
#Sta/Elev= 30
  4643.6  377.05    4675  376.12    4695  374.67    4805     370    4845  367.39
    4855  365.78    4885  363.75    4895   364.1    4925  363.52    4955  361.57
    4975  361.33    4985  357.57    4992  356.13  4994.8  355.63    4998  356.13
    5005   356.2    5025  362.01  5085.1  361.61  5145.1  362.28  5225.1  364.54
  5261.7  367.66    5288  368.61  5309.1  371.29    5315  371.16  5337.1  374.23
  5360.4  375.52  5366.4  376.47  5396.6  377.94  5402.5     379  5425.2  380.06
#Mann= 3 ,-1 , 0
  4643.6     .05       0    4992     .03       0    4998     .05       0
#XS Ineff= 1 ,-1
 5025.57 5240.91  365.55
Permanent Ineff=
       F
Bank Sta=4975,5025
XS Rating Curve= 0 ,0
Exp/Cntr=0.3,0.1

Type RM Length L Ch R = 1 ,4304    ,399,399,399
BEGIN DESCRIPTION:
Mapping XS 8e82265f
END DESCRIPTION:
XS GIS Cut Line= 2
      3607203.34     10591093.05      3607151.25      10590358.6
#Sta/Elev= 30
  4606.1  378.98    4639  377.58  4726.9  372.33  4731.9   372.6  4739.3  371.54
  4779.4  369.05  4829.5  366.86  4839.5  365.72  4909.7   361.1  4939.8  360.71
  4979.9  358.35  4989.9  352.01  4996.9  351.83  4999.7  351.33  5002.9  351.83
  5008.6  358.74  5013.6  361.25    5020   361.8  5050.1  360.87  5090.2  360.84
  5170.4  359.84  5190.4  360.11  5210.5  362.72  5220.5  365.14  5230.5  365.93
  5240.6  368.12  5260.6  369.62  5270.6  369.65  5300.7   371.2  5342.4  372.42
#Mann= 3 ,-1 , 0
  4606.1     .05       0  4996.9     .03       0  5002.9     .05       0
Bank Sta=4979.9,5008.6
XS Rating Curve= 0 ,0
Exp/Cntr=0.3,0.1

Type RM Length L Ch R = 1 ,3905    ,480,480,480
BEGIN DESCRIPTION:
UNT 049 IN UKCR 5.0
END DESCRIPTION:
XS GIS Cut Line= 3
       3607699.6     10590810.17      3607499.61     10590510.19
      3607099.64     10590210.21
#Sta/Elev= 30
  4630.4  383.66    4725  379.36  4746.1  377.07  4810.7  372.81  4818.2  371.49
  4824.2  371.95  4846.7  370.43  4854.2  369.63  4860.2  367.74  4882.8  367.22
  4977.4  358.73  4987.9  352.78  4994.1  352.78  5001.5  350.16  5004.2  349.66
  5007.5  350.16  5019.1  355.33  5033.6  358.26  5090.9  358.36  5098.2   353.7
  5112.8  355.18  5119.1  354.27  5127.4  357.67  5133.6  358.68  5161.9  360.66
  5233.6  363.87  5304.5  369.22  5333.6  370.09  5427.4  377.21  5490.9  379.92
#Mann= 4 ,-1 , 0
  4630.4     .05       0  5001.5     .03       0  5007.5     .05       0
  5161.9     .05       0
Bank Sta=4977.4,5033.6
XS Rating Curve= 0 ,0
Exp/Cntr=0.3,0.1

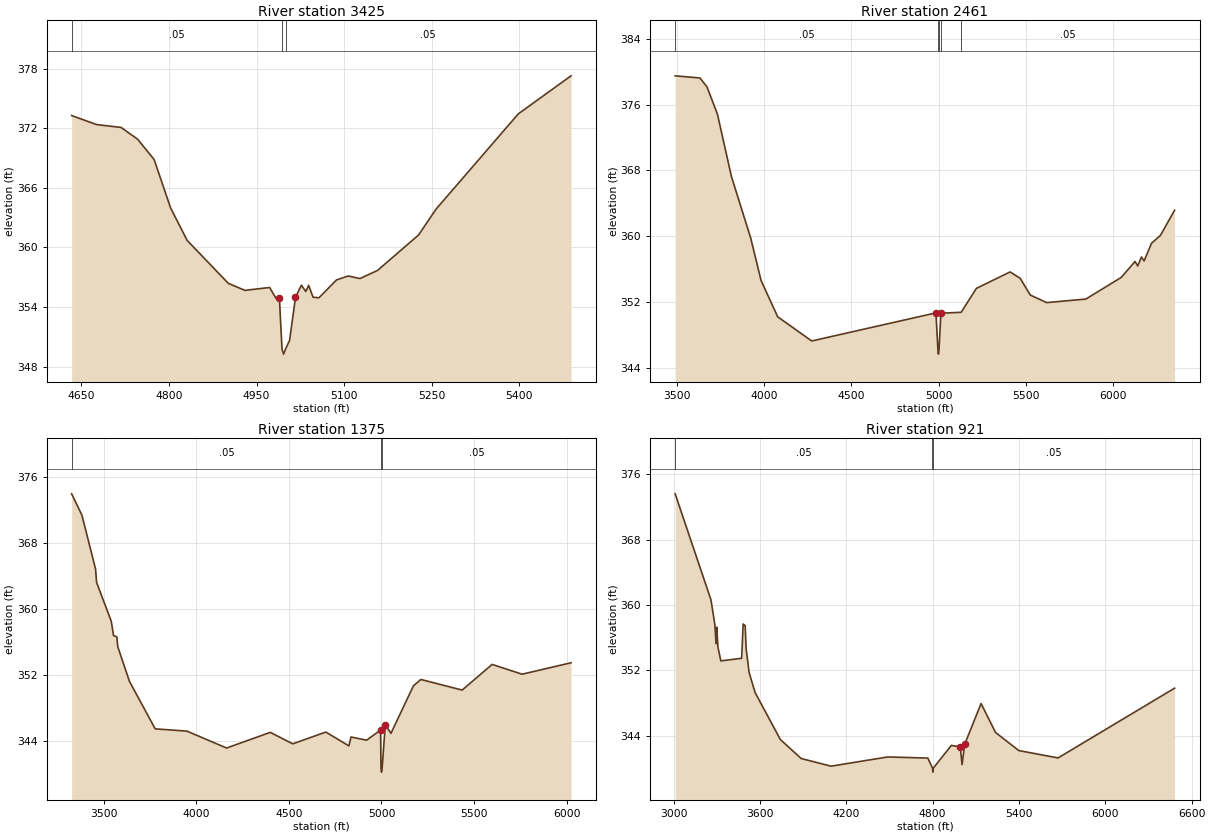
Type RM Length L Ch R = 1 ,3425    ,964,964,964
BEGIN DESCRIPTION:
UNT 049 IN UKCR 4.0
END DESCRIPTION:
XS GIS Cut Line= 3
       3607899.6     10590360.18      3607649.61     10590110.19
      3607149.65     10590160.18
#Sta/Elev= 30
  4633.1  373.28  4675.5  372.38  4717.9  372.08  4746.2   370.9  4774.5  368.85
  4802.8  363.97  4831.1  360.71  4901.8  356.38  4930.1  355.68  4972.5  355.97
  4983.1   354.9  4989.2   354.9  4993.7  349.76  4996.4  349.26  4999.7  349.76
  5006.7  350.65  5016.8  354.97  5026.8   356.2  5034.4  355.57  5039.4  356.18
  5046.9  354.99    5057  354.93  5087.1  356.73  5107.2  357.13  5127.3  356.87
  5157.5  357.69  5227.8  361.26    5258  363.88  5398.7  373.45  5489.1  377.28
#Mann= 3 ,-1 , 0
  4633.1     .05       0  4993.7     .03       0  4999.7     .05       0
Bank Sta=4989.2,5016.8
XS Rating Curve= 0 ,0
Exp/Cntr=0.3,0.1

Type RM Length L Ch R = 1 ,2461    ,1086,1086,1086
BEGIN DESCRIPTION:
UNT 049 IN UKCR 3.0
END DESCRIPTION:
XS GIS Cut Line= 4
      3608137.11     10590742.24       3608115.4      10589722.3
      3607659.68     10589179.76      3606704.84     10589787.39
#Sta/Elev= 30
  3491.1  379.49  3633.2  379.23  3673.2  378.15  3733.2  374.83  3813.2  367.25
  3923.3  359.79  3983.3  354.58  4078.4  350.17  4273.3  347.23  4984.8  350.65
  4996.1  346.13  4998.9  345.63  5002.1  346.13  5013.4  350.61  5015.2  350.61
  5129.3  350.72  5216.3  353.63  5409.5  355.63  5467.5  354.85  5525.1  352.82
    5619   351.9  5843.4  352.33  6046.6  354.97  6125.3  356.91  6140.6  356.35
  6161.7  357.45    6177  356.97  6219.3  359.11    6271  360.09  6351.6  363.14
#Mann= 5 ,-1 , 0
  3491.1     .05       0  4996.1     .03       0  5002.1     .05       0
  5015.2     .16       0  5129.3     .05       0
Bank Sta=4984.8,5013.4
XS Rating Curve= 0 ,0
Exp/Cntr=0.3,0.1

Type RM Length L Ch R = 1 ,1375    ,454,454,454
BEGIN DESCRIPTION:
UNT 049 IN UKCR 2.0
END DESCRIPTION:
XS GIS Cut Line= 3
      3608256.45     10590731.44        3608799.     10589320.82
      3608614.58     10588149.21
#Sta/Elev= 30
  3326.6  373.98    3382   371.4    3456  364.83  3461.3  363.22  3540.6   358.5
  3552.9  356.76  3570.6  356.61    3576  355.39  3638.7   351.2  3777.9  345.42
  3949.4  345.14  4163.6  343.09  4399.4  344.99  4520.9   343.6  4699.4  345.03
  4824.2  343.35  4835.6  344.43  4919.6  344.04  4995.2  345.27  4997.6  340.66
  5000.3  340.16  5003.6  340.66  5020.8  345.92  5051.2  344.87  5172.7  350.65
  5213.2  351.42  5435.9  350.13  5597.8  353.25  5759.8  352.06    6024  353.45
#Mann= 3 ,-1 , 0
  3326.6     .05       0  4997.6     .03       0  5003.6     .05       0
Bank Sta=4995.2,5020.8
XS Rating Curve= 0 ,0
Exp/Cntr=0.3,0.1

Type RM Length L Ch R = 1 ,921     ,0,0,0
BEGIN DESCRIPTION:
UNT 049 IN UKCR 1.0
END DESCRIPTION:
XS GIS Cut Line= 3
      3608712.18     10591187.17      3609363.23     10588691.48
      3608766.46      10588029.6
#Sta/Elev= 30
    3011  373.63  3259.7  360.65  3286.9  357.61    3295  355.27  3300.2   357.3
  3307.6  354.93  3328.3  353.17  3472.9  353.49  3483.3  357.69  3497.4  357.49
  3503.9  354.71  3524.6  351.78    3566  349.31  3741.6  343.55  3886.3  341.22
  4094.2  340.28  4488.7  341.41  4766.8  341.27  4799.1  340.05  4801.9  339.55
  4805.1  340.05  4930.1  342.82  4992.1  342.64  5004.5  340.47  5023.1  342.97
  5136.8  347.95  5237.1  344.41    5399  342.19  5671.9  341.29  6481.4  349.83
#Mann= 3 ,-1 , 0
    3011     .05       0  4799.1     .03       0  4805.1     .05       0
Bank Sta=4992.1,5023.1
XS Rating Curve= 0 ,0
Exp/Cntr=0.3,0.1

Chan Stop Cuts=-1
Use User Specified Reach Order=0
Composite Channel Slope=5