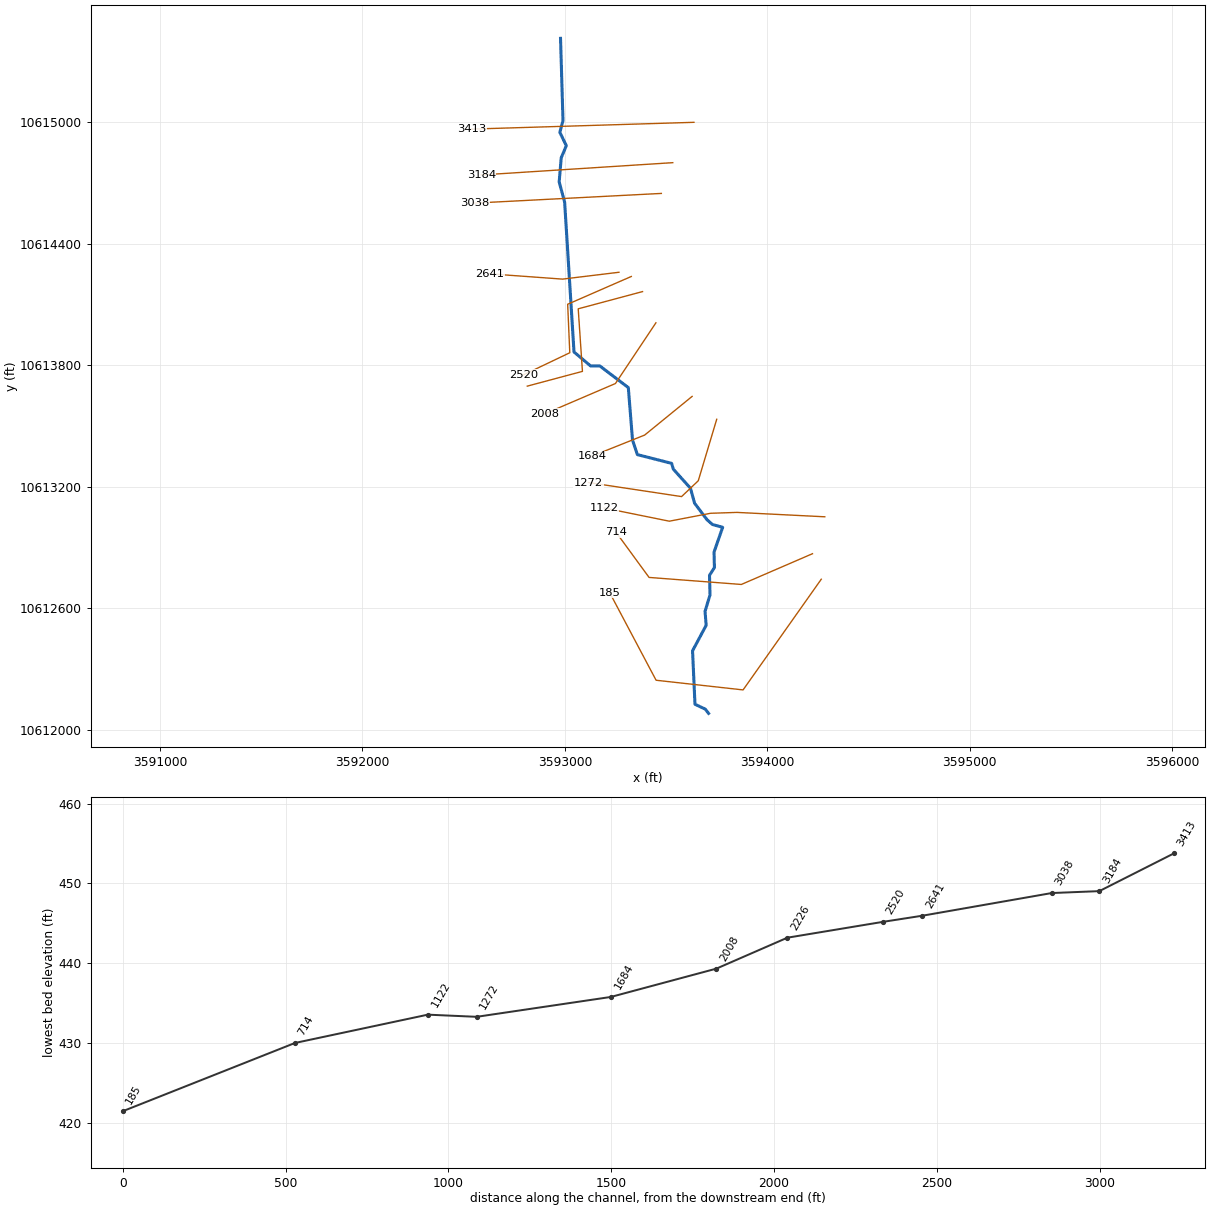
--- UNT 051 IN UKCR.prj (project) ---

Proj Title=UNT 051 IN UKCR Base Level Engineering
Current Plan=p01
Default Exp/Contr=0.3,0.1
English Units
Geom File=g01
Flow File=f01
Plan File=p01
Y Axis Title=Elevation
X Axis Title(PF)=Main Channel Distance
X Axis Title(XS)=Station
BEGIN DESCRIPTION:
UNT 051 IN UKCR
END DESCRIPTION:
DSS Export Rating Curves= 0
DSS Export Rating Curve Sorted= 0
DSS Export Volume Flow Curves= 0
DXF OffsetX= 0
DXF OffsetY= 0
DXF ScaleX= 1
DXF ScaleY= 10

--- UNT 051 IN UKCR.p01 (plan) ---

Plan Title=Multiple Run
Short Identifier=Multiple
Geom File=g01
Flow File=f01
Subcritical Flow
K Sum by GR= 0
Std Step Tol= 0.01
Critical Tol= 0.01
Num of Std Step Trials= 20
Max Error Tol= 0.3
Flow Tol Ratio= 0.001
Split Flow NTrial= 30
Split Flow Tol= 0.02
Split Flow Ratio= 0.02
Log Output Level= 0
Friction Slope Method= 1
Unsteady Friction Slope Method= 2
Unsteady Bridges Friction Slope Method= 1
Parabolic Critical Depth
Global Vel Dist=  1 , 1 , 1
Global Log Level= 0
CheckData=True
Encroach Param= -1, 0, 0, 0
BEGIN DESCRIPTION:
Multiple Run
END DESCRIPTION:

--- UNT 051 IN UKCR.f01 (steady flow) ---

Flow Title=Multiple
Program Version=4.10
Number of Profiles= 7
Profile Names=10-year,25-year,50-year,1pct_min,100-year,1pct_plu,500-year
River Rch & RM=UNT 051 IN UKCR,Reach-1         ,3413
     274     341     392     331     448     605     577
River Rch & RM=UNT 051 IN UKCR,Reach-1         ,3184
     274     341     392     331     448     605     577
River Rch & RM=UNT 051 IN UKCR,Reach-1         ,1122
     440     569     669     577     781    1056    1055
Boundary for River Rch & Prof#=UNT 051 IN UKCR,Reach-1         , 1
Up Type= 0
Dn Type= 3
Dn Slope=0.005
Boundary for River Rch & Prof#=UNT 051 IN UKCR,Reach-1         , 2
Up Type= 0
Dn Type= 3
Dn Slope=0.005
Boundary for River Rch & Prof#=UNT 051 IN UKCR,Reach-1         , 3
Up Type= 0
Dn Type= 3
Dn Slope=0.005
Boundary for River Rch & Prof#=UNT 051 IN UKCR,Reach-1         , 4
Up Type= 0
Dn Type= 3
Dn Slope=0.005
Boundary for River Rch & Prof#=UNT 051 IN UKCR,Reach-1         , 5
Up Type= 0
Dn Type= 3
Dn Slope=0.005
Boundary for River Rch & Prof#=UNT 051 IN UKCR,Reach-1         , 6
Up Type= 0
Dn Type= 3
Dn Slope=0.005
Boundary for River Rch & Prof#=UNT 051 IN UKCR,Reach-1         , 7
Up Type= 0
Dn Type= 3
Dn Slope=0.005
DSS Import GetInterval= 0
DSS Import GetPeak= 0
DSS Import FillOption= 0

--- UNT 051 IN UKCR.g01 (geometry) ---

Geom Title=Existing Conditions
Program Version=4.10

River Reach=UNT 051 IN UKCR ,Reach-1
Reach XY= 30
      3592978.39     10615415.17      3592990.61     10615008.98
        3592975.       10614951.        3593007.       10614885.
      3592981.75       10614825.      3592971.75       10614706.
      3592998.75       10614606.        3593045.       10613866.
        3593127.       10613797.       3593172.5       10613797.
      3593313.25       10613690.        3593334.       10613431.
        3593358.       10613359.        3593527.       10613316.
      3593535.75       10613287.      3593620.25       10613193.
       3593640.5       10613119.       3593702.5       10613037.
       3593728.5       10613014.      3593779.25       10613000.
      3593736.75       10612878.       3593738.5       10612801.
      3593714.25       10612763.      3593716.75       10612666.
      3593692.25       10612585.      3593697.75       10612516.
       3593630.5       10612390.       3593642.5       10612126.
      3593693.25       10612102.      3593709.75       10612081.

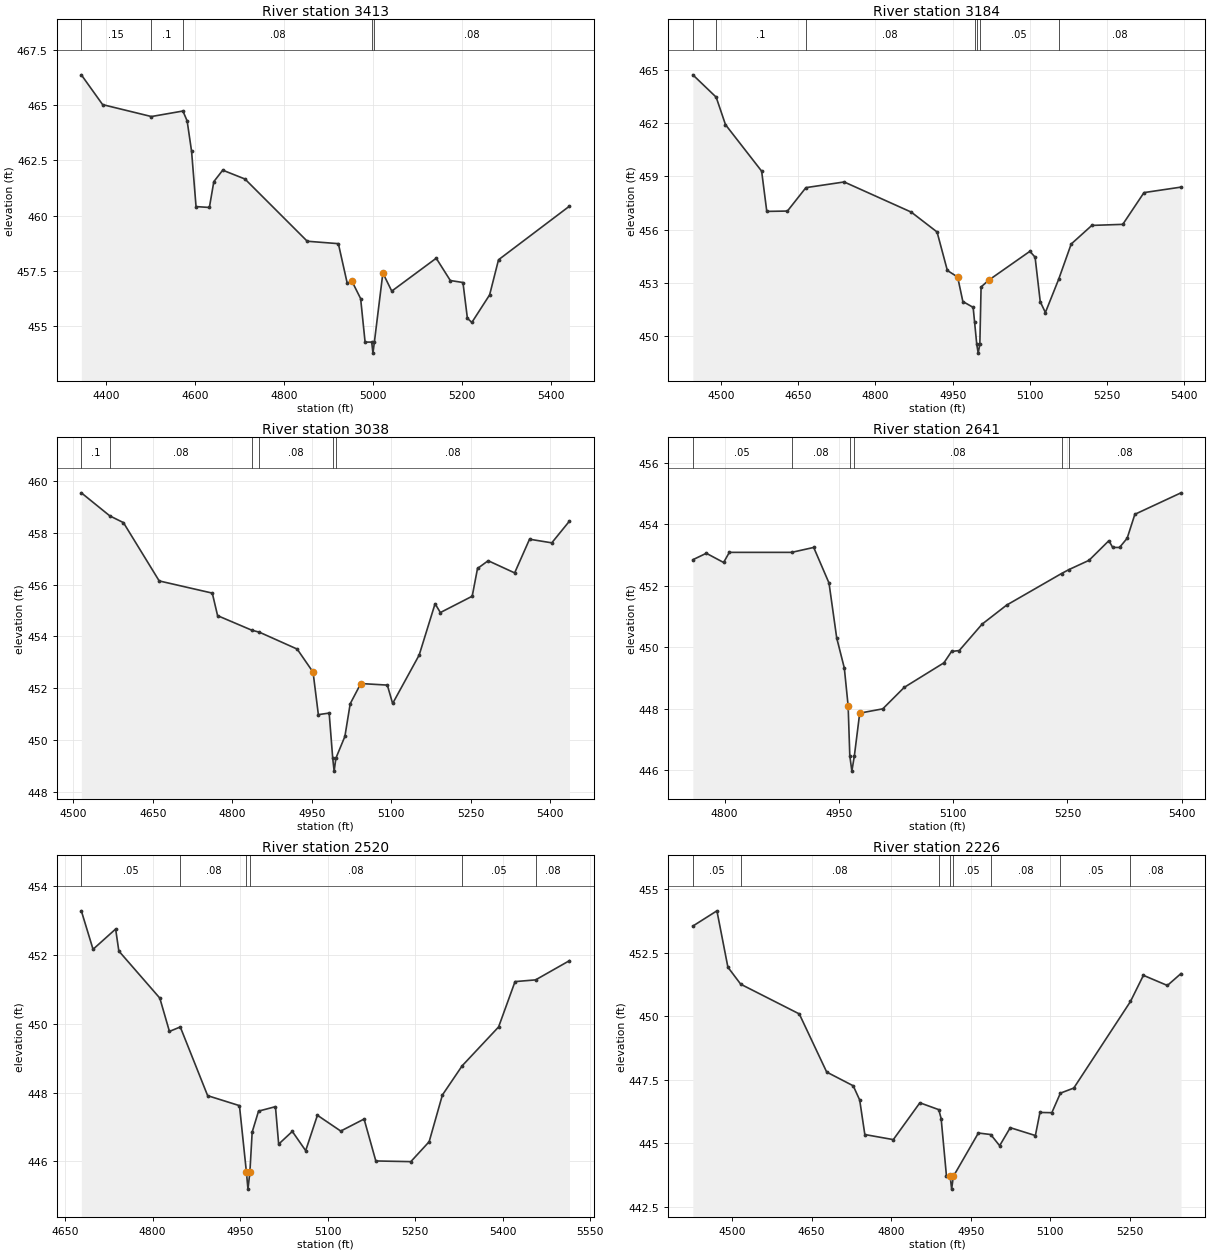
Type RM Length L Ch R = 1 ,3413    ,229,229,229
BEGIN DESCRIPTION:
Mapping XS cf2weki8
END DESCRIPTION:
XS GIS Cut Line= 2
      3593637.48     10615000.37      3592540.09     10614966.92
#Sta/Elev= 30
  4343.9  466.38  4391.8  465.03  4501.5  464.49  4572.4  464.74  4581.9  464.29
  4591.9  462.91  4601.9  460.41  4631.9  460.37  4641.9  461.54  4661.9  462.06
  4711.9  461.66    4852  458.84    4922  458.73    4942  456.93    4952  457.05
  4972.1  456.24  4982.1  454.27    4997  454.27  4999.8  453.77    5003  454.27
  5022.1   457.4  5042.1  456.58  5142.1  458.07  5173.8  457.06  5202.2  456.97
  5212.2  455.35  5222.2  455.16  5262.2  456.41  5282.2     458  5441.8  460.43
#Mann= 5 ,-1 , 0
  4343.9     .15       0  4501.5      .1       0  4572.4     .08       0
    4997     .07       0    5003     .08       0
Bank Sta=4952,5022.1
XS Rating Curve= 0 ,0
Exp/Cntr=0.3,0.1

Type RM Length L Ch R = 1 ,3184    ,146,146,146
BEGIN DESCRIPTION:
UNT 051 IN UKCR 7.0
END DESCRIPTION:
XS GIS Cut Line= 2
      3593532.89     10614801.09      3592586.74     10614740.33
#Sta/Elev= 30
  4445.3  464.73  4490.6  463.47  4508.7  461.92  4578.9   459.3  4588.9  457.03
    4629  457.05  4664.9  458.37  4739.2  458.69  4869.5  456.99  4919.6  455.87
  4939.6   453.7  4959.6  453.33  4969.7  451.95  4989.7  451.62  4992.5  450.79
  4996.7  449.54  4999.5  449.04  5002.7  449.54  5005.1  452.77  5019.8  453.15
  5099.9  454.78    5110  454.45    5120  451.94    5130  451.33    5156  453.22
  5180.1  455.19  5220.2  456.24  5280.3   456.3  5321.5  458.09  5393.4   458.4
#Mann= 7 ,-1 , 0
  4445.3     .15       0  4490.6      .1       0  4664.9     .08       0
  4992.5     .05       0  4996.7     .04       0  5002.7     .05       0
    5156     .08       0
Bank Sta=4959.6,5019.8
XS Rating Curve= 0 ,0
Exp/Cntr=0.3,0.1

Type RM Length L Ch R = 1 ,3038    ,397,397,397
BEGIN DESCRIPTION:
UNT 051 IN UKCR 6.0
END DESCRIPTION:
XS GIS Cut Line= 2
      3593476.45     10614649.18      3592556.28     10614601.44
#Sta/Elev= 30
  4515.1  459.54  4568.9  458.65  4594.6  458.39  4662.1  456.14  4762.3  455.67
  4772.3   454.8  4836.7  454.24  4851.4  454.16  4922.5  453.51  4952.5  452.62
  4962.5  450.98  4982.9  451.04  4989.6   449.3  4992.3   448.8  4995.6   449.3
  5012.6  450.14  5022.6   451.4  5042.6  452.18  5092.7  452.12  5102.7  451.41
  5152.8  453.28  5182.8  455.26  5192.8  454.92  5252.9  455.55  5262.9  456.62
    5283  456.92    5333  456.45  5361.1  457.75  5403.1  457.61  5436.5  458.45
#Mann= 6 ,-1 , 0
  4515.1      .1       0  4568.9     .08       0  4836.7      .1       0
  4851.4     .08       0  4989.6     .07       0  4995.6     .08       0
Bank Sta=4952.5,5042.6
XS Rating Curve= 0 ,0
Exp/Cntr=0.3,0.1

Type RM Length L Ch R = 1 ,2641    ,121,121,121
BEGIN DESCRIPTION:
UNT 051 IN UKCR 5.0
END DESCRIPTION:
XS GIS Cut Line= 3
      3593267.15     10614259.77      3592988.54     10614225.92
      3592629.14     10614251.96
#Sta/Elev= 30
  4758.2  452.85  4775.9  453.06  4798.6  452.76  4806.1  453.09    4888  453.09
  4916.9  453.25    4937  452.09  4947.1   450.3  4957.1  449.32  4962.1  448.09
  4964.3  446.46    4967  445.96  4970.3  446.46  4977.3  447.85  5007.6  447.99
  5035.8  448.69  5087.9  449.49  5097.9  449.86    5108  449.89    5138  450.75
  5170.2  451.37  5242.3   452.4  5252.2  452.53  5278.4  452.83  5304.5  453.47
  5309.5  453.25  5318.5  453.25  5328.5  453.55  5338.6  454.33  5399.2  455.03
#Mann= 6 ,-1 , 0
  4758.2     .05       0    4888     .08       0  4964.3     .07       0
  4970.3     .08       0  5242.3     .05       0  5252.2     .08       0
Bank Sta=4962.1,4977.3
XS Rating Curve= 0 ,0
Exp/Cntr=0.3,0.1

Type RM Length L Ch R = 1 ,2520    ,294,294,294
BEGIN DESCRIPTION:
Mapping XS bef78b8b
END DESCRIPTION:
XS GIS Cut Line= 4
      3593327.99     10614238.96      3593013.71     10614101.78
      3593024.13      10613862.2        3592795.     10613752.85
#Sta/Elev= 30
  4677.8  453.29  4697.9  452.17  4736.6  452.76  4742.1  452.12  4812.3  450.75
  4828.8  449.78  4847.4  449.91  4894.3  447.91  4948.8  447.62  4960.7  445.69
  4963.4  445.19  4966.7  445.69  4970.6  446.85  4981.5  447.46  5010.5  447.59
    5016   446.5  5039.4  446.87  5062.3  446.31  5082.4  447.34  5122.4  446.88
  5162.4  447.23  5182.5  446.01  5242.5  445.99  5273.9  446.57  5296.6  447.93
  5330.5  448.78  5392.9  449.91  5421.1  451.23  5456.3  451.28  5514.4  451.84
#Mann= 6 ,-1 , 0
  4677.8     .05       0  4847.4     .08       0  4960.7     .07       0
  4966.7     .08       0  5330.5     .05       0  5456.3     .08       0
Bank Sta=4960.7,4966.7
XS Rating Curve= 0 ,0
Exp/Cntr=0.3,0.1

Type RM Length L Ch R = 1 ,2226    ,218,218,218
BEGIN DESCRIPTION:
Mapping XS 736e0d51
END DESCRIPTION:
XS GIS Cut Line= 4
      3593383.46     10614164.27      3593065.79     10614079.22
      3593086.63     10613770.19      3592814.29     10613697.33
#Sta/Elev= 30
    4426  453.56  4471.4  454.16  4492.1  451.94  4516.3  451.27  4626.7   450.1
  4678.4  447.81  4728.4  447.27  4740.6  446.71  4750.3  445.35    4804  445.15
  4854.1   446.6  4889.7  446.33  4894.2  445.98  4904.2  443.72  4911.2   443.7
    4914   443.2  4917.2   443.7  4964.4  445.41  4987.7  445.35  5004.5  444.91
  5024.5  445.62  5071.9  445.31  5080.5  446.22  5102.9  446.21  5119.1  446.98
  5144.3  447.18  5251.2  450.59  5275.6  451.62  5320.8  451.22  5346.5  451.69
#Mann= 8 ,-1 , 0
    4426     .05       0  4516.3     .08       0  4889.7     .05       0
  4911.2     .07       0  4917.2     .05       0  4987.7     .08       0
  5119.1     .05       0  5251.2     .08       0
Bank Sta=4911.2,4917.2
XS Rating Curve= 0 ,0
Exp/Cntr=0.3,0.1

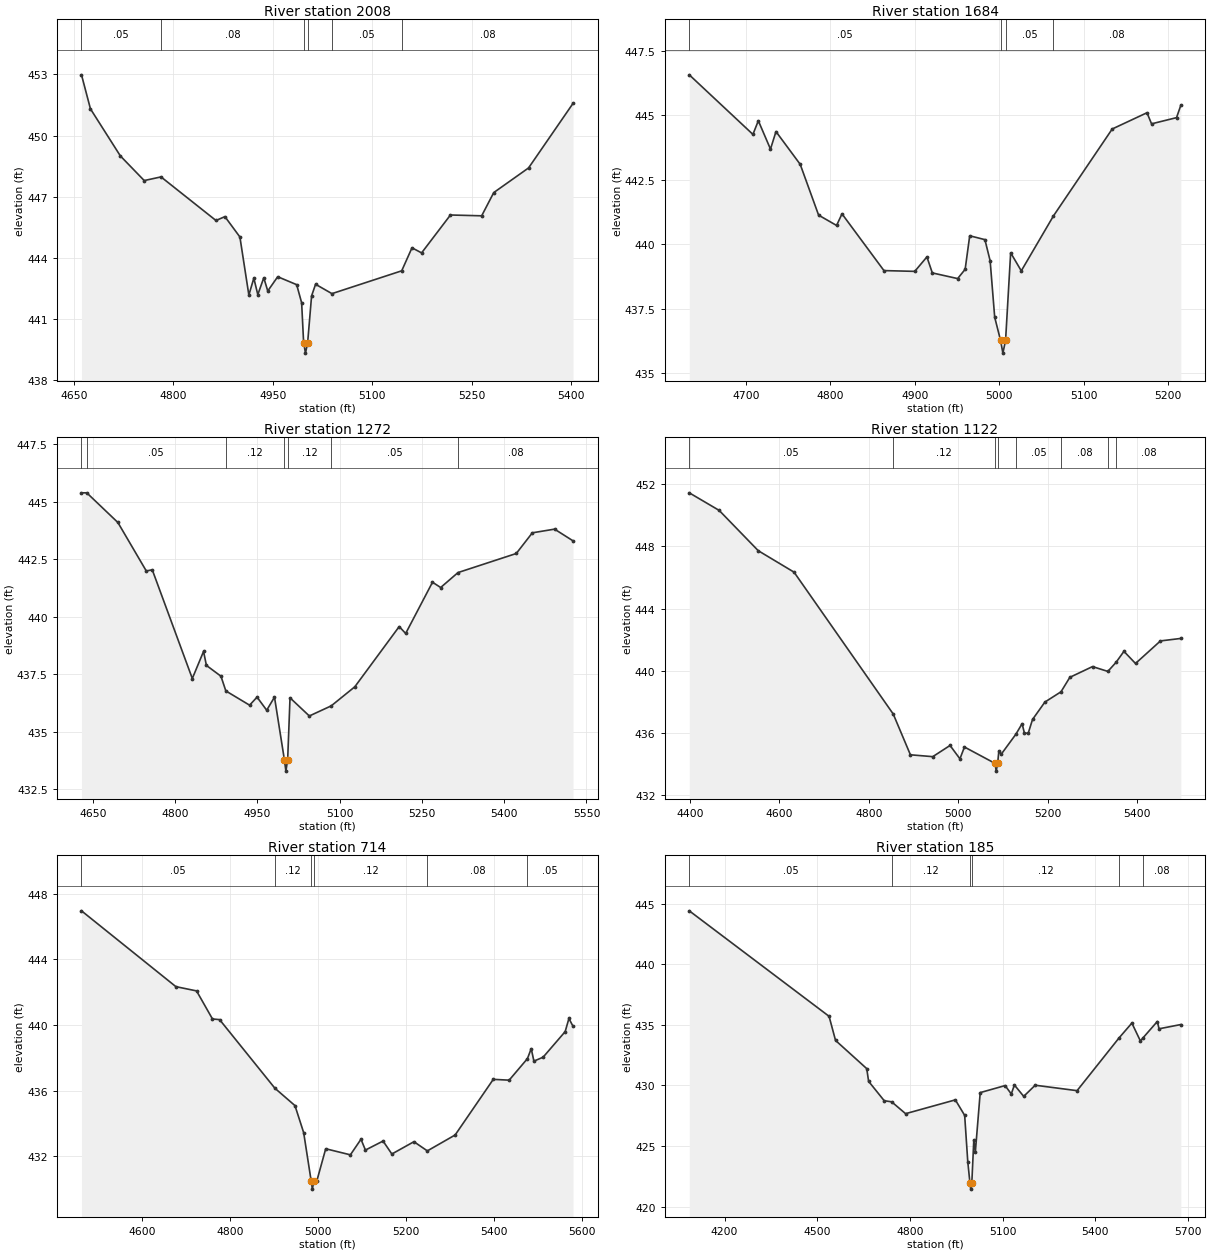
Type RM Length L Ch R = 1 ,2008    ,324,324,324
BEGIN DESCRIPTION:
UNT 051 IN UKCR 4.0
END DESCRIPTION:
XS GIS Cut Line= 3
       3593449.6     10614010.18      3593249.61     10613710.19
      3592899.64      10613560.2
#Sta/Elev= 30
  4661.3  452.98  4674.8  451.31  4719.9     449  4755.9  447.79  4781.2  447.97
  4864.1  445.83  4877.6  446.02  4900.2  445.02  4913.7  442.17  4921.2     443
  4927.2  442.19  4936.2  443.02  4942.2  442.37  4957.2  443.07  4985.8  442.68
  4993.3  441.79  4996.3  439.82  4999.1  439.32  5002.3  439.82  5008.3  442.13
  5014.3   442.7    5039  442.24  5144.2  443.36  5159.7  444.49  5174.2  444.24
  5217.7   446.1  5264.8  446.06    5283   447.2  5335.5  448.41  5402.6  451.58
#Mann= 6 ,-1 , 0
  4661.3     .05       0  4781.2     .08       0  4996.3     .07       0
  5002.3     .08       0    5039     .05       0  5144.2     .08       0
Bank Sta=4996.3,5002.3
XS Rating Curve= 0 ,0
Exp/Cntr=0.3,0.1

Type RM Length L Ch R = 1 ,1684    ,412,412,412
BEGIN DESCRIPTION:
Mapping XS 623b02de
END DESCRIPTION:
XS GIS Cut Line= 3
       3593628.4      10613646.6      3593394.01     10613455.61
      3593134.08     10613351.64
#Sta/Elev= 30
    4633  446.56  4708.4  444.25  4714.8  444.78  4729.2  443.68  4735.7  444.36
  4764.4  443.09  4786.2  441.12  4807.5  440.72  4813.9  441.17  4863.6  438.97
  4900.1  438.94  4914.5   439.5  4920.9  438.88  4950.9  438.66  4959.8  439.02
  4965.2  440.32  4983.2  440.17  4989.4  439.35  4994.8  437.16  5001.7  436.27
  5004.5  435.77  5007.7  436.27  5013.7  439.66  5026.3  438.96  5064.4  441.09
    5134  444.46  5175.2  445.09  5180.6  444.66  5210.2   444.9  5215.3  445.38
#Mann= 4 ,-1 , 0
    4633     .05       0  5001.7     .04       0  5007.7     .05       0
  5064.4     .08       0
Bank Sta=5001.7,5007.7
XS Rating Curve= 0 ,0
Exp/Cntr=0.3,0.1

Type RM Length L Ch R = 1 ,1272    ,150,150,150
BEGIN DESCRIPTION:
UNT 051 IN UKCR 3.0
END DESCRIPTION:
XS GIS Cut Line= 4
       3593749.9      10613533.7      3593658.76     10613229.91
       3593576.3     10613151.79      3593116.27     10613221.23
#Sta/Elev= 30
  4629.5  445.39  4639.1  445.39  4695.8   444.1  4747.6  441.99  4758.5  442.04
  4831.5  437.31    4852  438.49  4857.2  437.88  4883.7  437.41  4892.6  436.77
  4935.9  436.15  4949.5   436.5  4967.1  435.93  4981.3   436.5  4999.3  433.78
  5002.1  433.28  5005.3  433.78  5009.6  436.47  5044.8  435.68  5084.7  436.12
  5127.7  436.95  5208.6  439.57  5220.4  439.27  5269.3   441.5  5284.2  441.27
  5315.8  441.92    5422  442.75  5451.3  443.65  5491.8  443.81  5525.5   443.3
#Mann= 7 ,-1 , 0
  4629.5     .08       0  4639.1     .05       0  4892.6     .12       0
  4999.3     .07       0  5005.3     .12       0  5084.7     .05       0
  5315.8     .08       0
Bank Sta=4999.3,5005.3
XS Rating Curve= 0 ,0
Exp/Cntr=0.3,0.1

Type RM Length L Ch R = 1 ,1122    ,408,408,408
BEGIN DESCRIPTION:
UNT 051 IN UKCR 2.0
END DESCRIPTION:
XS GIS Cut Line= 5
      3594283.73     10613051.96      3593849.74     10613073.66
      3593719.53     10613069.32      3593515.53     10613030.26
      3593194.87     10613095.26
#Sta/Elev= 30
  4398.3  451.44  4465.2  450.31  4552.6  447.72  4632.7  446.34  4854.6  437.22
    4893   434.6    4943  434.48  4981.7   435.2  5003.8  434.34  5013.9   435.1
  5082.2  434.05    5085  433.55  5088.2  434.05  5090.9  434.86    5096  434.63
  5128.9  435.92  5142.9   436.6    5148     436  5156.5  435.98  5166.2  436.87
  5193.9  437.99  5229.9  438.65  5249.7  439.58  5300.4  440.27  5334.7  439.96
    5353  440.54  5370.7  441.25  5396.6  440.47  5452.4  441.92    5498  442.08
#Mann= 8 ,-1 , 0
  4398.3     .05       0  4854.6     .12       0  5082.2     .07       0
  5088.2     .12       0  5128.9     .05       0  5229.9     .08       0
  5334.7     .05       0    5353     .08       0
Bank Sta=5082.2,5088.2
XS Rating Curve= 0 ,0
Exp/Cntr=0.3,0.1

Type RM Length L Ch R = 1 ,714     ,529,529,529
BEGIN DESCRIPTION:
Mapping XS 5ad319ed
END DESCRIPTION:
XS GIS Cut Line= 4
        3594223.     10612869.67      3593871.44     10612717.76
      3593415.71     10612752.48      3593251.88     10612976.67
#Sta/Elev= 30
  4462.8  446.96  4677.4  442.34  4724.4  442.08  4760.6  440.37  4776.8  440.33
  4902.5  436.15  4948.2  435.09    4968  433.44    4985   430.5  4987.8     430
    4991   430.5    4998  430.51  5018.1  432.46  5074.2  432.09  5098.3  433.04
  5108.4  432.38  5148.5  432.93  5168.5  432.14  5218.7  432.89  5249.2  432.33
  5312.4   433.3  5399.1  436.69  5435.2  436.64  5476.7  437.95  5485.4  438.56
  5491.5   437.8  5512.4  438.04  5562.6   439.6  5571.1   440.4  5580.5  439.92
#Mann= 6 ,-1 , 0
  4462.8     .05       0  4902.5     .12       0    4985     .07       0
    4991     .12       0  5249.2     .08       0  5476.7     .05       0
Bank Sta=4985,4991
XS Rating Curve= 0 ,0
Exp/Cntr=0.3,0.1

Type RM Length L Ch R = 1 ,185     ,0,0,0
BEGIN DESCRIPTION:
UNT 051 IN UKCR 1.0
END DESCRIPTION:
XS GIS Cut Line= 4
      3594266.38     10612743.76      3593880.12     10612196.93
      3593450.43     10612244.67      3593221.31     10612676.98
#Sta/Elev= 30
  4085.7  444.42  4538.2  435.71  4559.1  433.72  4660.1  431.39  4666.2  430.34
  4716.7  428.74  4740.7  428.65  4785.9  427.67  4946.9  428.81  4977.1  427.53
  4987.1  423.72  4994.2  421.94  4996.9  421.44  5000.2  421.94  5006.7  425.52
  5011.7  424.52  5027.4  429.41  5107.9  429.99    5128   429.3    5138  430.04
  5168.2   429.1  5205.4  430.02  5340.9  429.57  5476.6  433.92  5518.3  435.15
    5546  433.67    5555  433.95  5600.6  435.28  5606.3  434.68  5676.8  435.03
#Mann= 6 ,-1 , 0
  4085.7     .05       0  4740.7     .12       0  4994.2     .07       0
  5000.2     .12       0  5476.6     .05       0    5555     .08       0
Bank Sta=4994.2,5000.2
XS Rating Curve= 0 ,0
Exp/Cntr=0.3,0.1

Chan Stop Cuts=-1
Use User Specified Reach Order=0
Composite Channel Slope=5