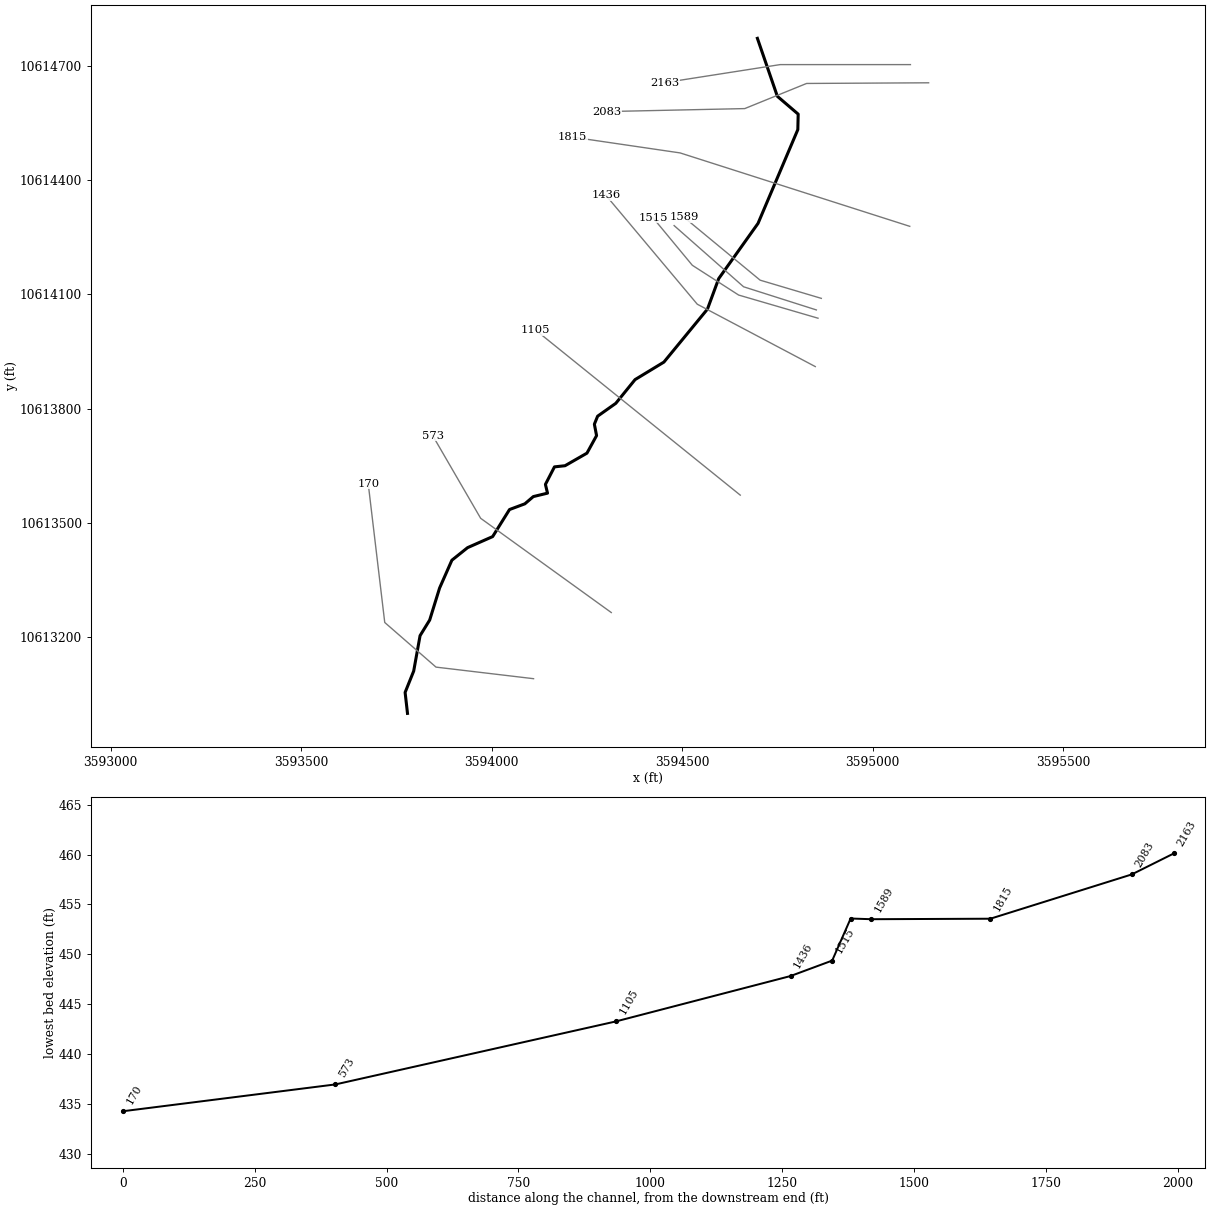
--- UNT 052 IN UKCR.prj (project) ---

Proj Title=UNT 052 IN UKCR Base Level Engineering
Current Plan=p01
Default Exp/Contr=0.3,0.1
English Units
Geom File=g01
Flow File=f01
Plan File=p01
Y Axis Title=Elevation
X Axis Title(PF)=Main Channel Distance
X Axis Title(XS)=Station
BEGIN DESCRIPTION:
UNT 052 IN UKCR
END DESCRIPTION:
DSS Export Rating Curves= 0
DSS Export Rating Curve Sorted= 0
DSS Export Volume Flow Curves= 0
DXF OffsetX= 0
DXF OffsetY= 0
DXF ScaleX= 1
DXF ScaleY= 10

--- UNT 052 IN UKCR.p01 (plan) ---

Plan Title=Multiple Run
Short Identifier=Multiple
Geom File=g01
Flow File=f01
Subcritical Flow
K Sum by GR= 0
Std Step Tol= 0.01
Critical Tol= 0.01
Num of Std Step Trials= 20
Max Error Tol= 0.3
Flow Tol Ratio= 0.001
Split Flow NTrial= 30
Split Flow Tol= 0.02
Split Flow Ratio= 0.02
Log Output Level= 0
Friction Slope Method= 1
Unsteady Friction Slope Method= 2
Unsteady Bridges Friction Slope Method= 1
Parabolic Critical Depth
Global Vel Dist=  1 , 1 , 1
Global Log Level= 0
CheckData=True
Encroach Param= -1, 0, 0, 0
BEGIN DESCRIPTION:
Multiple Run
END DESCRIPTION:

--- UNT 052 IN UKCR.f01 (steady flow) ---

Flow Title=Multiple
Number of Profiles=7
Profile Names=10-year,25-year,50-year,1pct_min,100-year,1pct_plu,500-year
River Rch & RM= UNT 052 IN UKCR,Reach-1,2163
     191     233     263     218     295     399     368
Boundary for River Rch & Prof#=UNT 052 IN UKCR,Reach-1,1
Up Type=0
Dn Type=3
Dn Slope=0.005
Boundary for River Rch & Prof#=UNT 052 IN UKCR,Reach-1,2
Up Type=0
Dn Type=3
Dn Slope=0.005
Boundary for River Rch & Prof#=UNT 052 IN UKCR,Reach-1,3
Up Type=0
Dn Type=3
Dn Slope=0.005
Boundary for River Rch & Prof#=UNT 052 IN UKCR,Reach-1,4
Up Type=0
Dn Type=3
Dn Slope=0.005
Boundary for River Rch & Prof#=UNT 052 IN UKCR,Reach-1,5
Up Type=0
Dn Type=3
Dn Slope=0.005
Boundary for River Rch & Prof#=UNT 052 IN UKCR,Reach-1,6
Up Type=0
Dn Type=3
Dn Slope=0.005
Boundary for River Rch & Prof#=UNT 052 IN UKCR,Reach-1,7
Up Type=0
Dn Type=3
Dn Slope=0.005

--- UNT 052 IN UKCR.g01 (geometry) ---

Geom Title=Existing Conditions

River Reach=UNT 052 IN UKCR,Reach-1
Reach XY= 30
      3594697.62     10614771.75      3594749.98     10614619.65
      3594804.67     10614572.78      3594803.73     10614532.22
      3594699.25     10614286.00      3594596.00     10614141.00
      3594566.50     10614061.00      3594452.25     10613922.00
      3594376.50     10613876.00      3594325.97     10613813.76
      3594278.25     10613780.00      3594269.75     10613759.00
      3594275.50     10613729.00      3594250.25     10613683.00
      3594192.75     10613650.00      3594165.00     10613647.00
      3594141.25     10613601.00      3594146.75     10613578.00
      3594109.50     10613569.00      3594087.25     10613550.00
      3594047.00     10613535.00      3594002.75     10613464.00
      3593937.00     10613435.00      3593895.75     10613402.00
      3593863.50     10613329.00      3593837.50     10613245.00
      3593812.25     10613204.00      3593795.50     10613111.00
      3593773.00     10613055.00      3593779.25     10613000.00

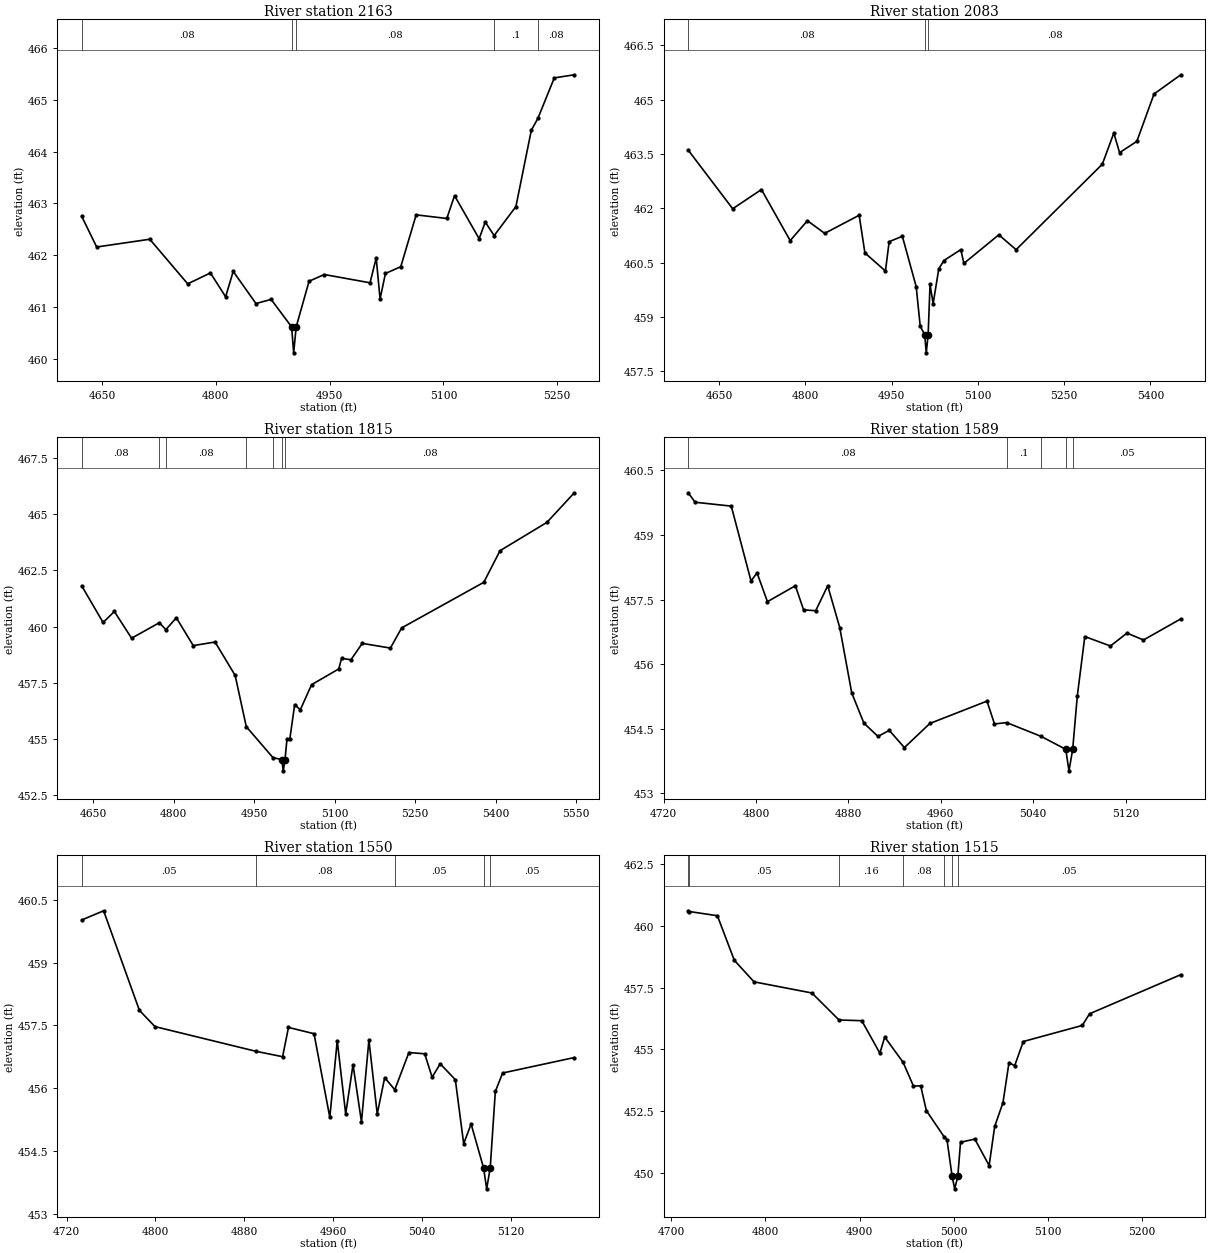
Type RM Length L Ch R = 1,2163,80,80,80
BEGIN DESCRIPTION:
UNT 052 IN UKCR 4.0
END DESCRIPTION:
XS GIS Cut Line= 3
      3595099.29     10614702.80      3594757.28     10614702.80
      3594453.57     10614655.34
#Sta/Elev= 30
  4623.2  462.75  4642.9  462.16  4712.9  462.31  4762.9  461.45  4792.9  461.66
  4812.9  461.20  4822.9  461.69  4852.9  461.07  4872.9  461.15  4899.9  460.62
  4902.6  460.12  4905.9  460.62  4922.9  461.50  4942.9  461.63  5003.3  461.47
  5011.4  461.95  5016.5  461.16  5023.6  461.65  5043.8  461.78  5064.1  462.78
  5104.5  462.71  5114.7  463.15  5147.1  462.32  5155.2  462.64  5166.9  462.38
  5195.6  462.94  5215.9  464.41  5224.6  464.64  5246.2  465.42  5272.6  465.48
#Mann=5,-1,0
  4623.2    0.08       0  4899.9    0.07       0  4905.9    0.08       0
  5166.9     0.1       0  5224.6    0.08       0
Bank Sta=4899.9,4905.9
Exp/Cntr=0.3,0.1

Type RM Length L Ch R = 1,2083,268,268,268
BEGIN DESCRIPTION:
Mapping XS 0fa0114d
END DESCRIPTION:
XS GIS Cut Line= 4
      3595147.04     10614655.06      3594826.73     10614653.32
      3594664.40     10614587.35      3594303.13     10614579.57
#Sta/Elev= 30
  4596.0  463.61  4673.4  461.99  4723.4  462.52  4773.4  461.11  4803.4  461.66
  4833.4  461.31  4893.4  461.81  4903.4  460.77  4939.1  460.27  4945.6  461.08
  4968.5  461.23  4992.6  459.84  4999.6  458.75  5007.4  458.51  5010.1  458.01
  5013.4  458.51  5016.7  459.90  5022.1  459.37  5031.9  460.33  5040.8  460.56
  5070.2  460.86  5075.6  460.48  5136.3  461.27  5166.4  460.86  5316.4  463.22
  5336.4  464.08  5346.4  463.54  5376.4  463.85  5406.4  465.16  5452.9  465.69
#Mann=3,-1,0
  4596.0    0.08       0  5007.4    0.07       0  5013.4    0.08       0
Bank Sta=5007.4,5013.4
Exp/Cntr=0.3,0.1

Type RM Length L Ch R = 1,1815,226,226,226
BEGIN DESCRIPTION:
Mapping XS 21a72cd2
END DESCRIPTION:
XS GIS Cut Line= 3
      3595097.53     10614278.33      3594494.69     10614471.03
      3594212.70     10614512.42
#Sta/Elev= 30
  4628.8  461.81  4668.6  460.18  4689.6  460.67  4721.7  459.48  4773.5  460.17
  4785.5  459.86  4805.1  460.39  4836.6  459.15  4877.3  459.31  4914.7  457.82
  4935.4  455.54  4985.1  454.16  5001.6  454.07  5004.3  453.57  5007.6  454.07
  5011.2  454.97  5016.5  454.98  5025.6  456.52  5036.1  456.29  5057.1  457.41
  5107.7  458.11  5113.0  458.58  5130.5  458.52  5151.5  459.25  5204.0  459.04
  5225.0  459.94  5378.0  461.97  5408.3  463.38  5495.6  464.64  5546.7  465.96
#Mann=7,-1,0
  4628.8    0.08       0  4773.5    0.05       0  4785.5    0.08       0
  4935.4     0.1       0  4985.1    0.08       0  5001.6    0.07       0
  5007.6    0.08       0
Bank Sta=5001.6,5007.6
Exp/Cntr=0.3,0.1

Type RM Length L Ch R = 1,1589,39,39,39
BEGIN DESCRIPTION:
Mapping XS 0c91bebc
END DESCRIPTION:
XS GIS Cut Line= 3
      3594865.38     10614089.28      3594704.77     10614137.03
      3594505.14     10614301.95
#Sta/Elev= 30
  4741.3  459.98  4747.3  459.76  4778.6  459.67  4795.7  457.93  4800.9  458.12
  4809.9  457.45  4834.1  457.82  4841.2  457.26  4851.7  457.24  4862.1  457.82
  4872.5  456.85  4882.9  455.33  4893.4  454.63  4905.6  454.32  4915.4  454.46
  4928.5  454.06  4950.5  454.62  5000.0  455.14  5006.5  454.61  5017.1  454.64
  5046.9  454.32  5068.2  454.02  5071.0  453.52  5074.2  454.02  5078.2  455.26
  5084.7  456.64  5106.9  456.42  5121.2  456.72  5135.5  456.56  5167.8  457.05
#Mann=5,-1,0
  4741.3    0.08       0  5017.1     0.1       0  5046.9    0.05       0
  5068.2    0.07       0  5074.2    0.05       0
Bank Sta=5068.2,5074.2
Exp/Cntr=0.3,0.1

Type RM Length L Ch R = 1,1550,35,35,35
BEGIN DESCRIPTION:
Mapping XS d92d6b4f
END DESCRIPTION:
XS GIS Cut Line= 3
      3594852.36     10614058.90      3594661.37     10614119.67
      3594479.05     10614280.28
#Sta/Elev= 30
  4733.6  460.02  4753.3  460.24  4785.5  457.86  4799.5  457.47  4890.3  456.88
  4914.4  456.75  4919.7  457.45  4942.7  457.30  4956.9  455.30  4963.6  457.13
  4971.2  455.38  4977.8  456.56  4985.4  455.19  4992.1  457.15  4999.6  455.38
  5006.3  456.25  5015.4  455.96  5028.1  456.85  5042.3  456.82  5049.0  456.26
  5056.3  456.58  5069.9  456.20  5077.4  454.67  5084.1  455.14  5095.3  454.09
  5098.1  453.59  5101.3  454.09  5105.9  455.92  5112.5  456.36  5177.0  456.73
#Mann=5,-1,0
  4733.6    0.05       0  4890.3    0.08       0  5015.4    0.05       0
  5095.3    0.07       0  5101.3    0.05       0
Bank Sta=5095.3,5101.3
Exp/Cntr=0.3,0.1

Type RM Length L Ch R = 1,1515,79,79,79
BEGIN DESCRIPTION:
Mapping XS 1c633241
END DESCRIPTION:
XS GIS Cut Line= 4
      3594856.67     10614037.21      3594648.35     10614097.97
      3594526.82     10614176.09      3594423.65     10614300.76
#Sta/Elev= 30
  4718.0  460.60  4719.2  460.57  4749.0  460.40  4767.0  458.60  4787.9  457.73
  4849.4  457.28  4878.2  456.19  4902.4  456.16  4921.6  454.85  4926.8  455.50
  4946.3  454.48  4957.3  453.52  4965.0  453.53  4971.0  452.53  4989.9  451.47
  4992.9  451.36  4998.4  449.87  5001.1  449.37  5004.4  449.87  5007.3  451.25
  5022.5  451.38  5037.7  450.31  5043.6  451.89  5052.4  452.85  5058.8  454.47
  5064.8  454.34  5074.0  455.32  5136.7  455.97  5144.4  456.44  5241.3  458.02
#Mann=7,-1,0
  4718.0    0.08       0  4719.2    0.05       0  4878.2    0.16       0
  4946.3    0.08       0  4989.9    0.05       0  4998.4    0.04       0
  5004.4    0.05       0
Bank Sta=4998.4,5004.4
Exp/Cntr=0.3,0.1

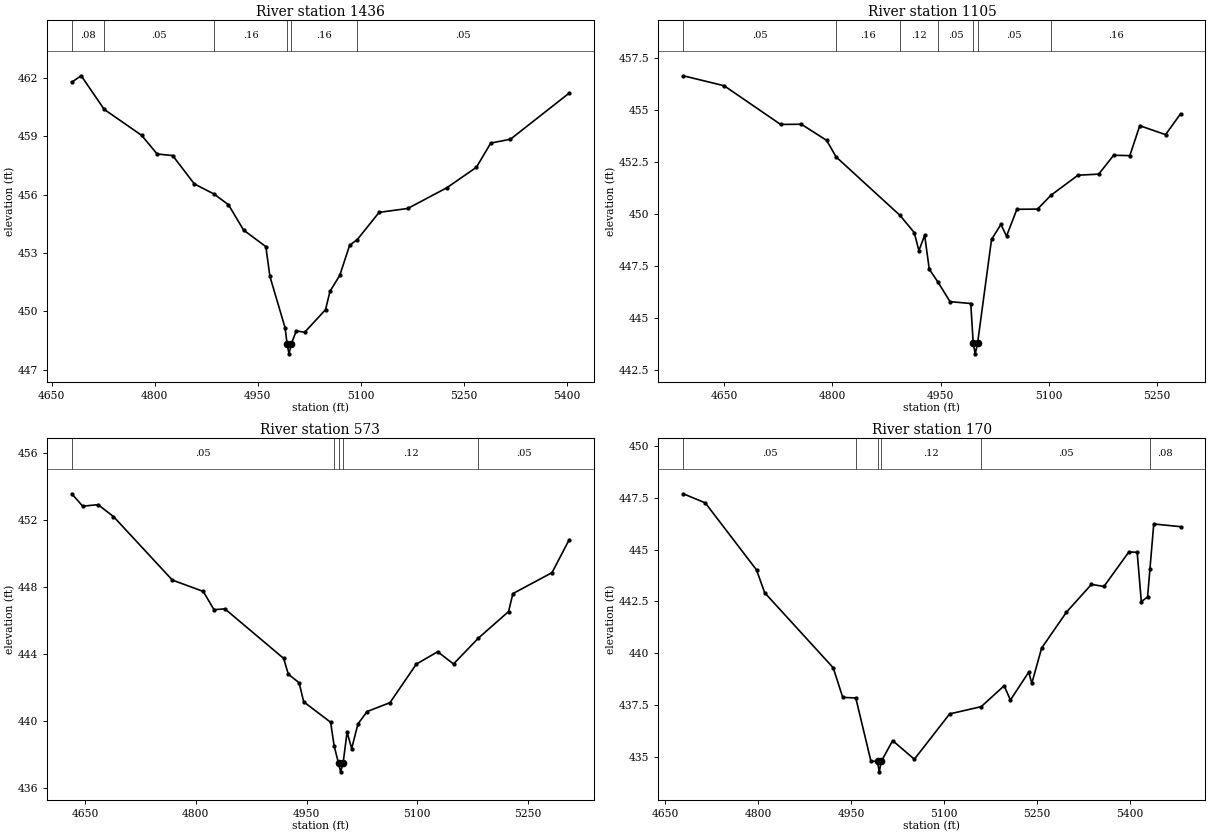
Type RM Length L Ch R = 1,1436,331,331,331
BEGIN DESCRIPTION:
UNT 052 IN UKCR 3.0
END DESCRIPTION:
XS GIS Cut Line= 3
      3594849.58     10613910.20      3594539.84     10614073.89
      3594299.59     10614360.21
#Sta/Elev= 30
  4679.0  461.78  4692.8  462.11  4726.4  460.38  4780.8  459.05  4803.4  458.09
  4826.0  458.01  4857.6  456.55  4886.4  456.03  4907.3  455.48  4929.3  454.18
  4961.7  453.33  4967.6  451.80  4989.7  449.16  4992.7  448.32  4995.4  447.82
  4998.7  448.32  5006.0  449.00  5018.3  448.93  5048.6  450.09  5055.1  451.03
  5069.4  451.86  5083.7  453.40  5094.8  453.69  5126.6  455.09  5168.3  455.29
  5225.5  456.36  5268.4  457.41  5289.2  458.65  5317.9  458.85  5403.1  461.21
#Mann=6,-1,0
  4679.0    0.08       0  4726.4    0.05       0  4886.4    0.16       0
  4992.7    0.07       0  4998.7    0.16       0  5094.8    0.05       0
Bank Sta=4992.7,4998.7
Exp/Cntr=0.3,0.1

Type RM Length L Ch R = 1,1105,532,532,532
BEGIN DESCRIPTION:
Mapping XS a07d17d3
END DESCRIPTION:
XS GIS Cut Line= 2
      3594652.66     10613572.81      3594115.56     10614005.96
#Sta/Elev= 30
  4593.0  456.64  4649.7  456.16  4728.0  454.30  4756.8  454.31  4792.0  453.53
  4805.0  452.74  4893.6  449.93  4913.5  449.10  4919.9  448.23  4927.9  448.97
  4934.3  447.34  4946.4  446.72  4963.1  445.78  4991.9  445.69  4995.3  443.77
  4998.1  443.27  5001.3  443.77  5020.7  448.77  5033.7  449.49  5041.5  448.93
  5055.9  450.22  5084.6  450.23  5103.0  450.89  5140.7  451.86  5169.4  451.91
  5190.2  452.82  5212.6  452.80  5226.4  454.24  5262.2  453.81  5283.0  454.81
#Mann=7,-1,0
  4593.0    0.05       0  4805.0    0.16       0  4893.6    0.12       0
  4946.4    0.05       0  4995.3    0.04       0  5001.3    0.05       0
  5103.0    0.16       0
Bank Sta=4995.3,5001.3
Exp/Cntr=0.3,0.1

Type RM Length L Ch R = 1,573,403,403,403
BEGIN DESCRIPTION:
UNT 052 IN UKCR 2.0
END DESCRIPTION:
XS GIS Cut Line= 3
      3594314.12     10613264.65      3593971.26     10613512.03
      3593845.38     10613729.08
#Sta/Elev= 30
  4631.8  453.55  4646.7  452.81  4667.5  452.90  4688.4  452.19  4768.1  448.40
  4810.0  447.72  4824.6  446.63  4839.3  446.68  4919.0  443.72  4925.2  442.78
  4939.9  442.27  4946.1  441.13  4982.6  439.91  4987.4  438.48  4993.4  437.45
  4996.1  436.95  4999.4  437.45  5004.9  439.32  5011.1  438.34  5019.6  439.81
  5032.0  440.55  5063.0  441.08  5098.7  443.38  5127.6  444.12  5149.1  443.39
  5182.7  444.93  5223.7  446.52  5229.5  447.59  5282.5  448.84  5305.5  450.78
#Mann=5,-1,0
  4631.8    0.05       0  4987.4    0.12       0  4993.4    0.07       0
  4999.4    0.12       0  5182.7    0.05       0
Bank Sta=4993.4,4999.4
Exp/Cntr=0.3,0.1

Type RM Length L Ch R = 1,170,0,0,0
BEGIN DESCRIPTION:
UNT 052 IN UKCR 1.0
END DESCRIPTION:
XS GIS Cut Line= 4
      3594110.12     10613091.03      3593854.08     10613121.41
      3593719.53     10613238.59      3593676.13     10613603.15
#Sta/Elev= 30
  4678.8  447.70  4714.3  447.26  4797.1  444.02  4810.2  442.92  4921.0  439.29
  4936.4  437.86  4957.5  437.83  4981.9  434.78  4992.6  434.76  4995.4  434.26
  4998.6  434.76  5017.0  435.77  5052.1  434.87  5109.1  437.06  5160.1  437.41
  5197.2  438.42  5207.3  437.73  5236.9  439.08  5241.9  438.54  5257.7  440.24
  5297.9  441.98  5338.2  443.32  5358.4  443.22  5398.7  444.89  5412.1  444.87
  5418.8  442.49  5428.9  442.71  5432.7  444.05  5438.9  446.24  5482.2  446.11
#Mann=6,-1,0
  4678.8    0.05       0  4957.5    0.12       0  4992.6    0.07       0
  4998.6    0.12       0  5160.1    0.05       0  5432.7    0.08       0
Bank Sta=4992.6,4998.6
Exp/Cntr=0.3,0.1

Chan Stop Cuts=-1