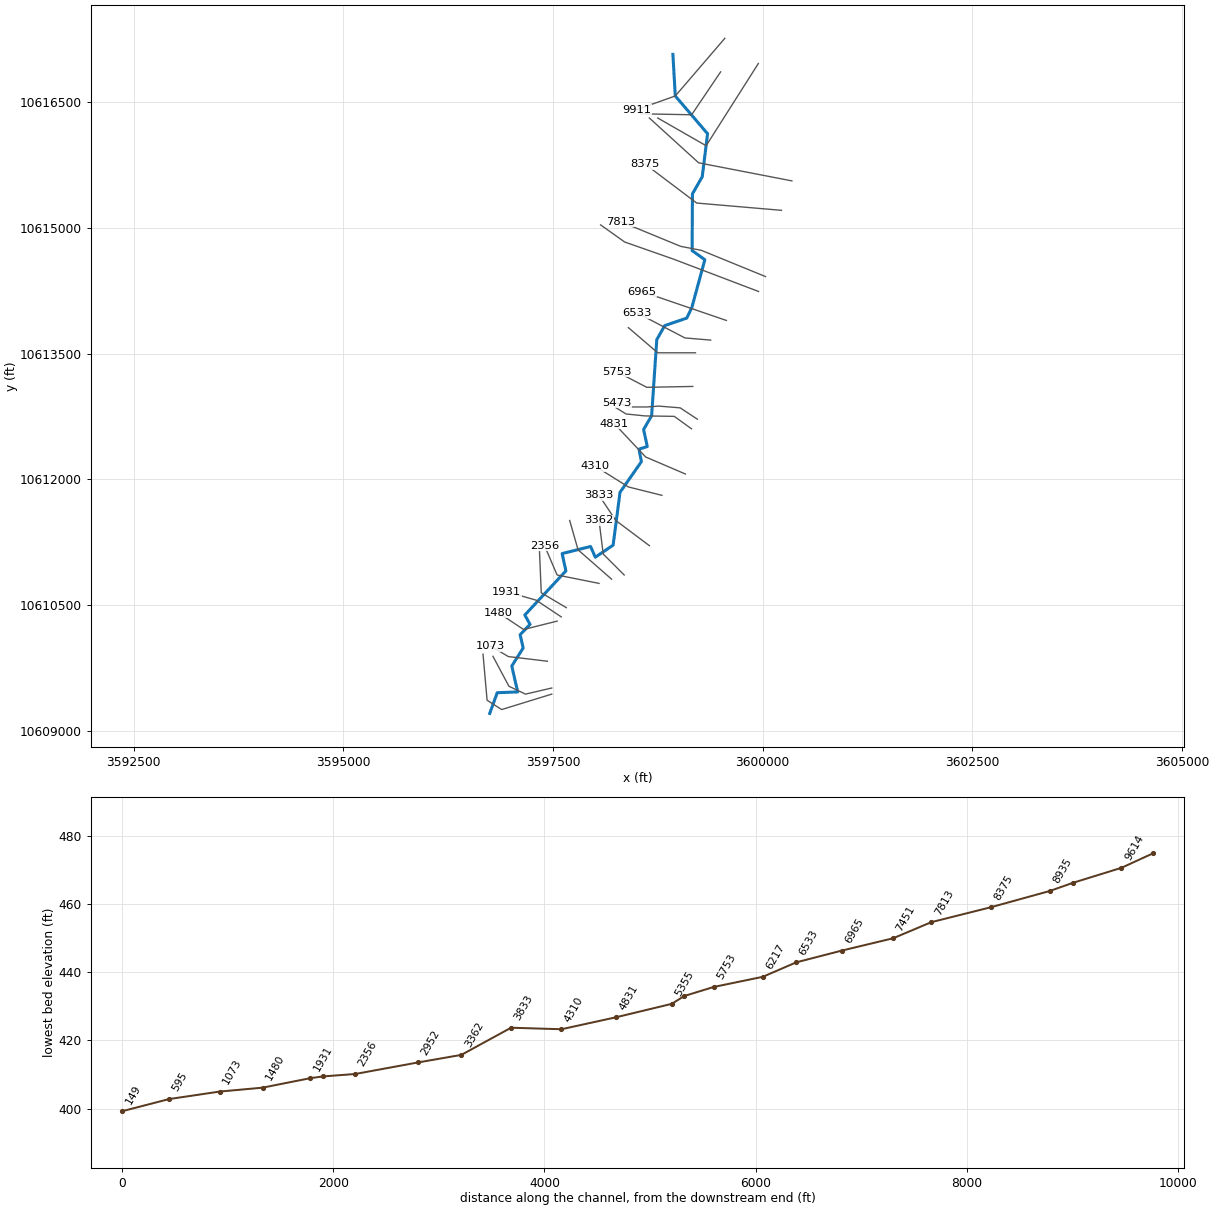
--- UNT 054 IN UKCR.prj (project) ---

Proj Title=UNT 054 IN UKCR Base Level Engineering
Current Plan=p01
Default Exp/Contr=0.3,0.1
English Units
Geom File=g01
Flow File=f01
Plan File=p01
Y Axis Title=Elevation
X Axis Title(PF)=Main Channel Distance
X Axis Title(XS)=Station
BEGIN DESCRIPTION:
UNT 054 IN UKCR
END DESCRIPTION:
DSS Export Rating Curves= 0
DSS Export Rating Curve Sorted= 0
DSS Export Volume Flow Curves= 0
DXF OffsetX= 0
DXF OffsetY= 0
DXF ScaleX= 1
DXF ScaleY= 10

--- UNT 054 IN UKCR.p01 (plan) ---

Plan Title=Multiple Run
Program Version=4.10
Short Identifier=Multiple
Geom File=g01
Flow File=f01
Subcritical Flow
K Sum by GR= 0
Std Step Tol= 0.01
Critical Tol= 0.01
Num of Std Step Trials= 20
Max Error Tol= 0.3
Flow Tol Ratio= 0.001
Split Flow NTrial= 30
Split Flow Tol= 0.02
Split Flow Ratio= 0.02
Log Output Level= 0
Friction Slope Method= 1
Unsteady Friction Slope Method= 2
Unsteady Bridges Friction Slope Method= 1
Parabolic Critical Depth
Global Vel Dist= 1 , 1 , 1
Global Log Level= 0
CheckData=True
Encroach Param=-1 ,0,0, 0
BEGIN DESCRIPTION:
Multiple Run
END DESCRIPTION:
Computation Interval=1HOUR
Output Interval=1HOUR
Run HTab= 0
Run UNet= 0
Run PostProcess= 0
Run WQNet= 0
UNET Theta= 1
UNET Theta Warmup= 1
UNET ZTol= 0.02
UNET ZSATol= 0.05
UNET MxIter= 20
UNET MaxInSteps= 0
UNET DtIC= 0
UNET DtMin= 0
UNET MaxCRTS= 20
UNET WFStab= 2
UNET SFStab= 1
UNET WFX= 1
UNET SFX= 1
UNET DSS MLevel= 4
UNET DZMax Abort= 100
UNET Convert EG Bridges= 0
UNET Use Existing IB Tables=-1
UNET Froude Reduction=False
UNET Froude Limit= 1
UNET Froude Power= 10
UNET Time Slicing=0,0, 5
UNET Junction Losses=0
Instantaneous Interval=1HOUR
Write IC File= 0
Write IC File at Sim End=0
Echo Input=False
Echo Parameters=False
Echo Output=False
Write Detailed= 0
WQ AD Non Conservative
WQ ULTIMATE=-1
WQ Max Comp Step=1HOUR
WQ Output Interval=15MIN
WQ Output Selected Increments= 0
WQ Output face flow=0
WQ Output face velocity=0
WQ Output face area=0
WQ Output face dispersion=0
WQ Output cell volume=0
WQ Output cell surface area=0
WQ Output cell continuity=0
WQ Output cumulative cell continuity=0
WQ Output face conc=0
WQ Output face dconc_dx=0
WQ Output face courant=0
WQ Output face peclet=0
WQ Output face adv mass=0
WQ Output face disp mass=0
WQ Output cell mass=0
WQ Output cell source sink temp=0
WQ Output cell source sink nsm=0
WQ Output MaxMinRange=-1
WQ Daily Max Min Mean=-1
WQ Daily Range=0
WQ Daily Time=0
WQ Create Restart=0
WQ Fixed Restart=0
WQ System Summary=0
WQ Use Fixed Temperature=0
Sorting and Armoring Iterations= 10
XS Update Threshold= 0.02
Hydraulics Update Threshold= 0.02
Energy Slope Method= 1
Volume Change Method= 0
XS Weighting Method= 0
Number of US Weighted Cross Sections= 1
Number of DS Weighted Cross Sections= 1
Upstream XS Weight=0.25
Main XS Weight=0.5
Downstream XS Weight=0.25
Number of DS XS's Weighted with US Boundary= 1
Upstream Boundary Weight= 1
Weight of XSs Associated with US Boundary= 0
Number of US XS's Weighted with DS Boundary= 1
Downstream Boundary Weight= 0.5
Weight of XSs Associated with DS Boundary= 0.5
Sediment Output Level= 4
Mass or Volume Output= 0
Output Increment Type= 1
Profile and TS Output Increment= 10
XS Output Flag= 0
XS Output Increment= 10
Disregard all LS=0
Disregard all Conn=0
Disregard all Breaches=0
Disregard all Pumps=0

--- UNT 054 IN UKCR.f01 (steady flow) ---

Flow Title=Multiple
Program Version=4.10
Number of Profiles= 7
Profile Names=10-year,25-year,50-year,1pct_min,100-year,1pct_plu,500-year
River Rch & RM=UNT 054 IN UKCR,Reach-1         ,9911
     346     439     510     435     588     795     775
River Rch & RM=UNT 054 IN UKCR,Reach-1         ,7451
     598     789     941     821    1110    1501    1537
River Rch & RM=UNT 054 IN UKCR,Reach-1         ,2952
     772    1037    1251    1103    1492    2017    2111
River Rch & RM=UNT 054 IN UKCR,Reach-1         ,1931
     995    1357    1654    1472    1990    2692    2871
River Rch & RM=UNT 054 IN UKCR,Reach-1         ,1480
     995    1357    1654    1472    1990    2692    2871
Boundary for River Rch & Prof#=UNT 054 IN UKCR,Reach-1         , 1
Up Type= 0
Dn Type= 3
Dn Slope=0.005
Boundary for River Rch & Prof#=UNT 054 IN UKCR,Reach-1         , 2
Up Type= 0
Dn Type= 3
Dn Slope=0.005
Boundary for River Rch & Prof#=UNT 054 IN UKCR,Reach-1         , 3
Up Type= 0
Dn Type= 3
Dn Slope=0.005
Boundary for River Rch & Prof#=UNT 054 IN UKCR,Reach-1         , 4
Up Type= 0
Dn Type= 3
Dn Slope=0.005
Boundary for River Rch & Prof#=UNT 054 IN UKCR,Reach-1         , 5
Up Type= 0
Dn Type= 3
Dn Slope=0.005
Boundary for River Rch & Prof#=UNT 054 IN UKCR,Reach-1         , 6
Up Type= 0
Dn Type= 3
Dn Slope=0.005
Boundary for River Rch & Prof#=UNT 054 IN UKCR,Reach-1         , 7
Up Type= 0
Dn Type= 3
Dn Slope=0.005
DSS Import GetInterval= 0
DSS Import GetPeak= 0
DSS Import FillOption= 0

--- UNT 054 IN UKCR.g01 (geometry) ---

Geom Title=Existing Conditions
Program Version=4.10

River Reach=UNT 054 IN UKCR ,Reach-1
Reach XY= 30
      3598930.53     10617068.87      3598958.93     10616572.63
      3599344.07     10616122.44      3599280.25       10615610.
       3599163.5       10615405.      3599159.75       10614729.
       3599311.5       10614620.        3599156.       10614049.
      3599095.75       10613924.      3598832.75       10613834.
      3598738.25       10613667.      3598676.75       10612759.
        3598581.       10612595.      3598625.25       10612392.
      3598526.25       10612361.      3598554.75       10612212.
      3598299.75       10611846.       3598217.5       10611216.
       3598004.5       10611072.       3597949.5       10611200.
       3597609.5       10611116.      3597654.25       10610909.
      3597164.75       10610383.      3597226.75       10610271.
       3597108.5       10610148.        3597145.       10609990.
        3597009.       10609774.      3597079.75       10609466.
       3596835.5       10609456.        3596746.       10609210.

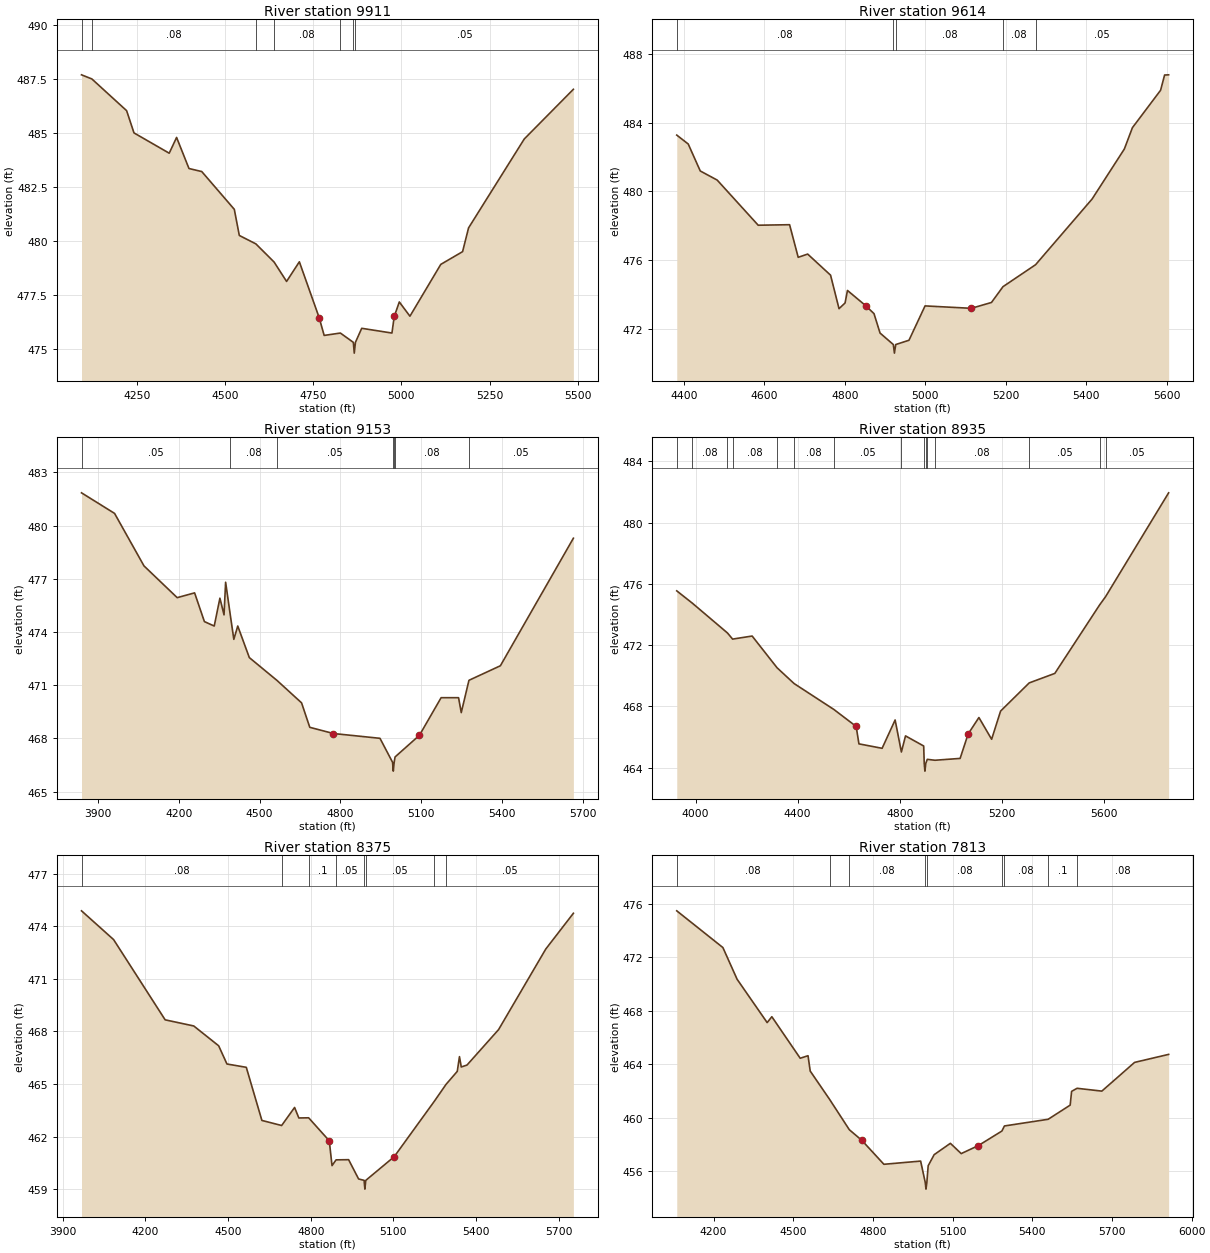
Type RM Length L Ch R = 1 ,9911    ,297,297,297
BEGIN DESCRIPTION:
UNT 054 IN UKCR 21.0
END DESCRIPTION:
XS GIS Cut Line= 3
      3599549.58     10617260.16      3598958.93     10616572.63
      3598499.61     10616410.19
#Sta/Elev= 30
  4093.6  487.68  4122.9  487.49  4221.4  486.02  4242.3  484.99  4342.1  484.05
    4363  484.78  4398.1  483.34  4434.3   483.2  4526.5  481.45  4540.7  480.24
  4587.6  479.85  4639.2  479.01  4674.6  478.11  4710.8  479.02  4766.8  476.44
  4781.1  475.61    4827  475.72  4863.7  475.29  4866.4  474.79  4869.7  475.29
  4887.5  475.94  4973.1  475.72  4979.7  476.49    4994  477.16  5024.1   476.5
  5111.5   478.9  5173.3  479.49  5190.2  480.59  5348.1  484.71  5487.2  487.01
#Mann= 7 ,-1 , 0
  4093.6      .1       0  4122.9     .08       0  4587.6      .1       0
  4639.2     .08       0    4827     .05       0  4863.7     .04       0
  4869.7     .05       0
Bank Sta=4766.8,4979.7
XS Rating Curve= 0 ,0
Exp/Cntr=0.3,0.1

Type RM Length L Ch R = 1 ,9614    ,461,461,461
BEGIN DESCRIPTION:
UNT 054 IN UKCR 20.0
END DESCRIPTION:
XS GIS Cut Line= 3
      3599499.63     10616860.22      3599153.99     10616348.63
       3598549.6     10616360.19
#Sta/Elev= 30
  4382.6  483.27  4411.1  482.75    4441  481.18    4483  480.65  4584.9  478.02
  4662.9  478.05  4684.3  476.15  4707.8  476.34  4764.7  475.11  4785.7  473.16
  4800.7  473.49  4806.7  474.22  4851.6  473.34  4872.6  472.87  4887.6  471.74
  4920.6  471.07  4923.3  470.57  4926.6  471.07  4959.5  471.32  4999.4  473.32
  5114.4  473.18  5164.4  473.52    5193  474.44    5274  475.72  5414.5  479.55
  5494.5  482.46  5514.5   483.7  5584.5  485.88  5594.5  486.77  5604.5  486.78
#Mann= 5 ,-1 , 0
  4382.6     .08       0  4920.6     .04       0  4926.6     .08       0
    5193     .08       0    5274     .05       0
Bank Sta=4851.6,5114.4
XS Rating Curve= 0 ,0
Exp/Cntr=0.3,0.1

Type RM Length L Ch R = 1 ,9153    ,218,218,218
BEGIN DESCRIPTION:
UNT 054 IN UKCR 19.0
END DESCRIPTION:
XS GIS Cut Line= 3
       3599949.6     10616960.17       3599326.8     10615979.41
      3598749.57     10616310.21
#Sta/Elev= 30
  3838.2  481.85    3961  480.69  4070.3  477.73  4193.6  475.94  4258.3  476.21
  4294.7  474.59  4331.2  474.34  4352.3  475.91  4367.6  474.97  4373.5  476.81
  4390.8  474.97    4404  473.59  4418.6  474.34  4461.6  472.56  4564.6  471.27
  4655.6  470.01  4686.1  468.63    4774  468.28  4946.9  468.01  4993.6  466.66
  4996.3  466.16  4999.6  466.66    5003  466.96  5093.4  468.18    5174   470.3
  5238.8   470.3  5248.8  469.46  5277.4  471.28  5394.1   472.1  5665.3  479.29
#Mann= 7 ,-1 , 0
  3838.2     .05       0  4390.8     .08       0  4564.6     .05       0
  4993.6     .04       0  4999.6     .05       0    5003     .08       0
  5277.4     .05       0
Bank Sta=4774,5093.4
XS Rating Curve= 0 ,0
Exp/Cntr=0.3,0.1

Type RM Length L Ch R = 1 ,8935    ,560,560,560
BEGIN DESCRIPTION:
UNT 054 IN UKCR 18.0
END DESCRIPTION:
XS GIS Cut Line= 3
      3600349.65     10615560.18      3599237.33     10615775.71
      3598649.62     10616310.18
#Sta/Elev= 30
  3926.2  475.55  3987.7  474.74  4124.9   472.8    4145   472.4  4221.6   472.6
  4319.2  470.53  4385.8   469.5  4541.5  467.81  4629.1   466.7  4640.1  465.56
  4730.9  465.27  4781.9  467.12  4806.4  465.03  4822.6  466.08  4893.8  465.42
  4895.9  464.28  4898.6  463.78  4901.9  464.28  4907.9  464.55  4937.9  464.49
  5036.5  464.61  5068.1  466.21  5110.2  467.28    5160  465.86  5195.1   467.7
  5307.3  469.54  5407.6  470.16  5583.1  474.63  5606.5  475.17  5853.6  481.95
#Mann= 15 ,-1 , 0
  3926.2     .05       0  3987.7     .08       0  4124.9     .05       0
    4145     .08       0  4319.2      .1       0  4385.8     .08       0
  4541.5     .05       0  4806.4     .08       0  4895.9     .07       0
  4901.9     .08       0  4907.9     .05       0  4937.9     .08       0
  5307.3     .05       0  5583.1     .08       0  5606.5     .05       0
Bank Sta=4629.1,5068.1
XS Rating Curve= 0 ,0
Exp/Cntr=0.3,0.1

Type RM Length L Ch R = 1 ,8375    ,562,562,562
BEGIN DESCRIPTION:
UNT 054 IN UKCR 17.0
END DESCRIPTION:
XS GIS Cut Line= 3
      3600225.56     10615209.08      3599214.32     10615295.89
      3598599.62     10615760.18
#Sta/Elev= 30
  3967.9  474.88  4084.3  473.24  4271.5  468.66  4375.3  468.31  4465.7  467.18
  4495.8  466.14    4566  465.95  4622.6  462.92  4694.3  462.63  4741.3  463.66
  4756.7  463.06  4792.3  463.07  4867.1  461.76  4877.2  460.34  4891.9  460.67
  4937.4  460.68  4973.6  459.58  4993.7   459.5  4996.4     459  4999.7   459.5
  5102.8  460.85  5248.8  464.02  5291.1  464.98  5331.8  465.72  5339.7  466.56
  5346.3  465.97  5367.1  466.08  5481.6   468.1    5653   472.7  5753.2  474.74
#Mann= 8 ,-1 , 0
  3967.9     .08       0  4694.3     .15       0  4792.3      .1       0
  4891.9     .05       0  4993.7     .04       0  4999.7     .05       0
  5248.8     .08       0  5291.1     .05       0
Bank Sta=4867.1,5102.8
XS Rating Curve= 0 ,0
Exp/Cntr=0.3,0.1

Type RM Length L Ch R = 1 ,7813    ,362,362,362
BEGIN DESCRIPTION:
UNT 054 IN UKCR 16.0
END DESCRIPTION:
XS GIS Cut Line= 4
      3600034.67     10614419.13      3599270.74     10614731.65
      3599023.35     10614779.39      3598307.22     10615074.52
#Sta/Elev= 30
  4061.4  475.48  4235.1  472.73  4288.5  470.36  4401.8  467.11  4419.4  467.55
  4526.2  464.44  4555.6  464.63  4563.9  463.48  4636.9  461.36  4711.1  459.09
  4758.4  458.29  4841.3   456.5  4979.6  456.74    4997  455.14  4999.7  454.64
    5003  455.14    5008  456.39  5030.5  457.22  5091.6  458.07  5132.4   457.3
  5196.9   457.9  5285.6  458.99  5295.1  459.37  5459.7  459.87  5542.6  460.93
    5548  461.96  5568.5  462.19  5661.9  461.98  5785.1  464.13  5913.3  464.73
#Mann= 9 ,-1 , 0
  4061.4     .08       0  4636.9     .05       0  4711.1     .08       0
    4997     .07       0    5003     .08       0  5285.6     .05       0
  5295.1     .08       0  5459.7      .1       0  5568.5     .08       0
Bank Sta=4758.4,5196.9
XS Rating Curve= 0 ,0
Exp/Cntr=0.3,0.1

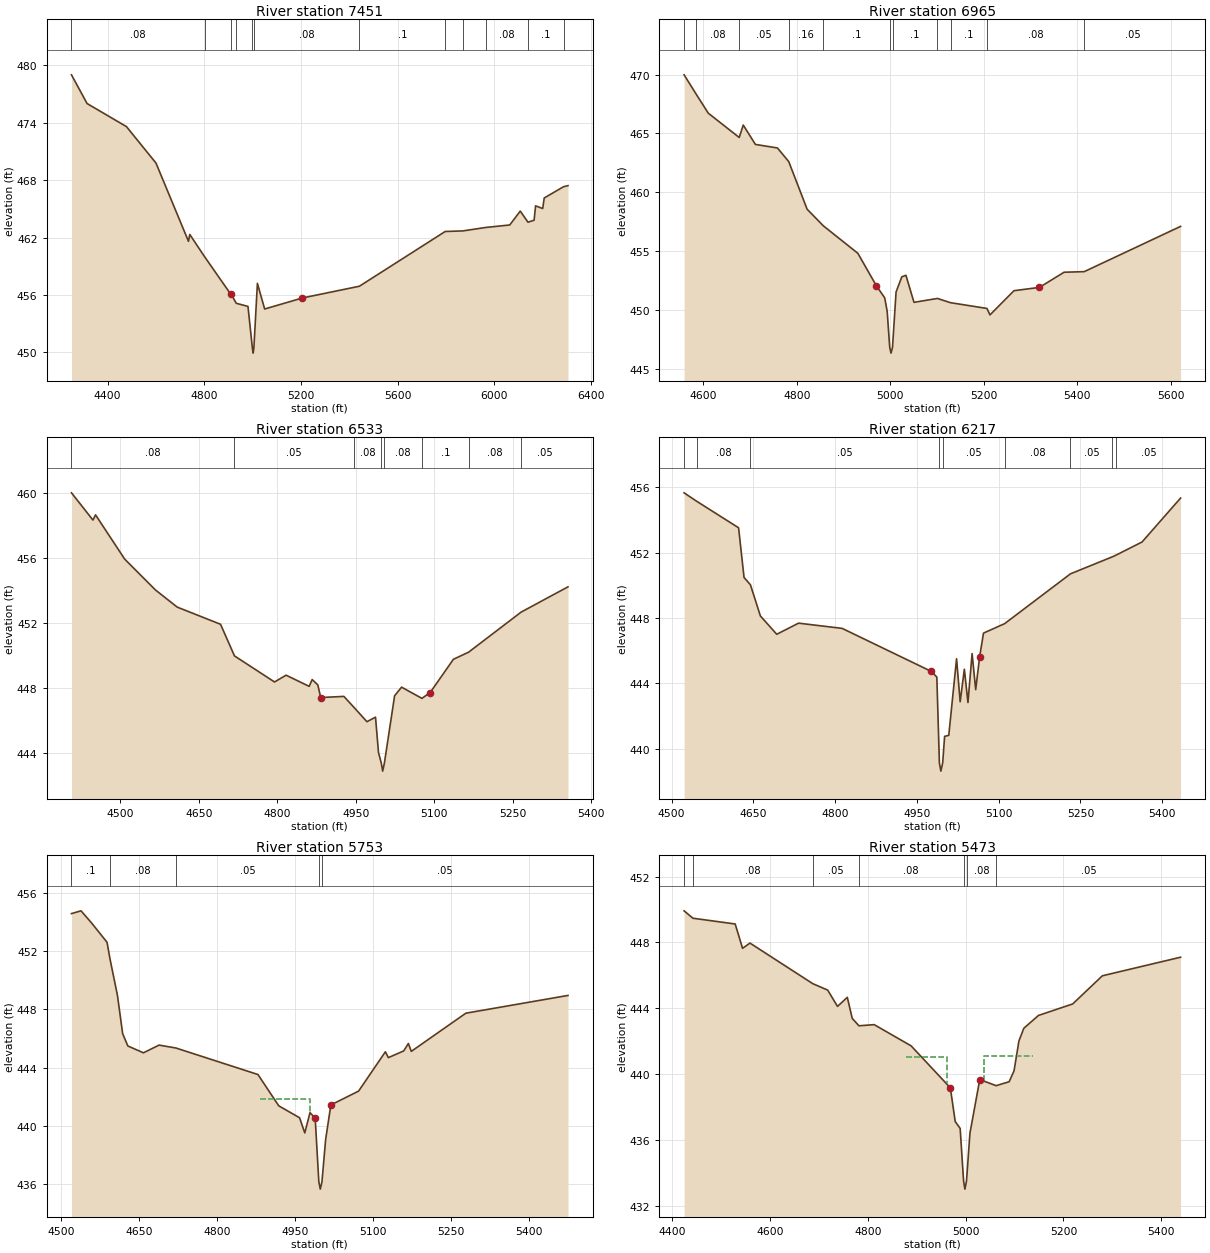
Type RM Length L Ch R = 1 ,7451    ,486,486,486
BEGIN DESCRIPTION:
UNT 054 IN UKCR 15.0
END DESCRIPTION:
XS GIS Cut Line= 4
      3599952.13     10614241.21      3598936.54     10614627.48
      3598354.94     10614831.48      3598068.71     10615035.31
#Sta/Elev= 30
  4250.8     479  4315.3     476  4478.2  473.59  4600.4  469.78  4734.9   461.6
  4740.2  462.32  4801.7  459.99  4909.1   456.1  4910.2  456.14  4932.4  455.13
    4981   454.8  4999.4  450.42  5002.2  449.92  5005.4  450.42    5020  457.21
  5050.1  454.53  5205.7  455.68  5442.1  456.91  5797.1  462.63  5870.3  462.69
  5964.7  463.05  6064.1  463.31  6107.6  464.76  6139.6   463.6  6164.9  463.81
    6171  465.31  6200.5  465.03  6206.7  466.13  6286.9  467.31  6305.1  467.42
#Mann= 12 ,-1 , 0
  4250.8     .08       0  4801.7     .05       0  4909.1      .1       0
  4932.4     .08       0  4999.4     .07       0  5005.4     .08       0
  5442.1      .1       0  5797.1     .08       0  5870.3     .05       0
  5964.7     .08       0  6139.6      .1       0  6286.9     .15       0
Bank Sta=4910.2,5205.7
XS Rating Curve= 0 ,0
Exp/Cntr=0.3,0.1

Type RM Length L Ch R = 1 ,6965    ,432,432,432
BEGIN DESCRIPTION:
UNT 054 IN UKCR 14.0
END DESCRIPTION:
XS GIS Cut Line= 2
      3599568.51      10613895.7      3598563.93     10614239.24
#Sta/Elev= 30
    4559  469.98  4584.8  468.34  4610.7  466.72  4676.9  464.65  4685.5  465.71
  4711.5  464.06  4758.6  463.76  4782.8   462.6  4822.1  458.55  4856.7  457.14
  4930.6   454.8    4970  452.05    4988  451.01  4993.3  449.87  4998.7  446.81
  5001.5  446.31  5004.7  446.81  5012.3  451.51  5024.6   452.8  5033.4  452.93
  5050.6  450.63  5100.8  450.96  5128.7   450.6  5206.7  450.11  5213.1  449.56
  5264.4  451.62  5318.8   451.9  5371.6  453.19  5414.7  453.24  5620.7  457.09
#Mann= 11 ,-1 , 0
    4559      .1       0  4584.8     .08       0  4676.9     .05       0
  4782.8     .16       0  4856.7      .1       0  4998.7     .07       0
  5004.7      .1       0  5100.8     .16       0  5128.7      .1       0
  5206.7     .08       0  5414.7     .05       0
Bank Sta=4970,5318.8
XS Rating Curve= 0 ,0
Exp/Cntr=0.3,0.1

Type RM Length L Ch R = 1 ,6533    ,316,316,316
BEGIN DESCRIPTION:
Mapping XS 783c11f0
END DESCRIPTION:
XS GIS Cut Line= 3
      3599380.94     10613661.34      3599073.69     10613687.38
      3598505.98     10613984.26
#Sta/Elev= 30
  4406.4  460.03  4447.4  458.35  4452.4  458.67  4508.1  455.94  4566.8  454.04
  4608.4  452.98  4691.3  451.92  4717.9  449.97  4794.5  448.36  4816.6  448.78
  4860.7  448.09  4866.4  448.51  4877.2  448.18  4882.8   447.4    4927  447.47
  4945.9  446.81  4971.1  445.91  4987.5  446.19  4993.2  444.01  4998.5  443.36
  5001.2  442.86  5004.5  443.36    5024  447.51  5037.3  448.04  5076.2  447.35
  5091.8   447.7  5136.4  449.76  5165.5   450.2  5265.8  452.67  5355.4  454.23
#Mann= 8 ,-1 , 0
  4406.4     .08       0  4717.9     .05       0  4945.9     .08       0
  4998.5     .07       0  5004.5     .08       0  5076.2      .1       0
  5165.5     .08       0  5265.8     .05       0
Bank Sta=4882.8,5091.8
XS Rating Curve= 0 ,0
Exp/Cntr=0.3,0.1

Type RM Length L Ch R = 1 ,6217    ,464,464,464
BEGIN DESCRIPTION:
UNT 054 IN UKCR 13.0
END DESCRIPTION:
XS GIS Cut Line= 3
      3599199.58     10613510.19      3598749.61     10613510.19
      3598399.65     10613810.16
#Sta/Elev= 30
  4522.8  455.67  4545.6  455.16  4622.8  453.53  4632.8  450.49  4644.5  450.04
  4662.8  448.13  4692.8  447.01  4732.8  447.69  4812.8  447.37  4976.1  444.74
  4986.5  444.39  4991.2  439.13  4993.9  438.63  4997.2  439.13  5000.8  440.76
  5008.4  440.82  5022.7  445.51  5029.3  442.88    5037  444.87  5043.6  442.83
  5051.2  445.83  5057.8  443.62    5065  445.62  5072.1  447.08  5110.9  447.66
  5231.7  450.71  5308.4  451.75  5315.6  451.86    5363  452.66  5433.7  455.35
#Mann= 9 ,-1 , 0
  4522.8     .15       0  4545.6     .08       0  4644.5     .05       0
  4991.2     .04       0  4997.2     .05       0  5110.9     .08       0
  5231.7     .05       0  5308.4      .1       0  5315.6     .05       0
Bank Sta=4976.1,5065
XS Rating Curve= 0 ,0
Exp/Cntr=0.3,0.1

Type RM Length L Ch R = 1 ,5753    ,280,280,280
BEGIN DESCRIPTION:
UNT 054 IN UKCR 12.0
END DESCRIPTION:
XS GIS Cut Line= 3
      3599167.87     10613108.82       3598618.4      10613098.4
      3598259.75     10613285.52
#Sta/Elev= 30
  4520.4  454.58  4538.7  454.77  4558.7  453.95  4588.7  452.61  4594.6  451.43
  4608.7  448.97  4618.7  446.34  4628.7  445.49  4658.7  445.02  4688.7  445.55
  4721.1  445.35  4878.7  443.53  4918.7  441.38  4958.7  440.56  4968.7  439.52
  4978.7  440.91  4988.7  440.54  4995.7  436.16  4998.5  435.66  5001.7  436.16
  5008.8  439.07  5018.8  441.44  5072.1  442.39  5123.6  445.09  5129.3  444.69
  5158.8  445.15  5167.8  445.66  5173.4  445.12  5278.2  447.74  5474.5  448.96
#Mann= 5 ,-1 , 0
  4520.4      .1       0  4594.6     .08       0  4721.1     .05       0
  4995.7     .04       0  5001.7     .05       0
#XS Ineff= 1 ,-1
 4882.05 4979.55  441.88
Permanent Ineff=
       F
Bank Sta=4988.7,5018.8
XS Rating Curve= 0 ,0
Exp/Cntr=0.3,0.1

Type RM Length L Ch R = 1 ,5473    ,118,118,118
BEGIN DESCRIPTION:
Mapping XS f5acc167
END DESCRIPTION:
XS GIS Cut Line= 6
      3599222.59     10612718.18      3599016.84     10612853.61
      3598761.63     10612874.45       3598618.4     10612864.03
      3598417.88     10612864.03       3598256.4     10612913.51
#Sta/Elev= 30
  4424.1  449.92  4442.2  449.47  4528.6  449.12  4543.7  447.64  4558.8  447.96
  4687.4  445.49  4717.8   445.1  4737.9  444.11  4757.9  444.66    4768  443.38
  4781.7  442.93  4812.9     443  4888.4  441.71  4968.6  439.16  4978.6  437.11
  4988.7  436.69  4995.7   433.5  4998.4     433  5001.7   433.5  5008.7   436.4
  5028.8  439.66  5062.3  439.29  5088.9  439.53  5098.9  440.19  5108.9  442.01
  5118.9  442.78  5148.9  443.56  5218.9  444.26  5279.5  445.97  5439.5   447.1
#Mann= 7 ,-1 , 0
  4424.1     .15       0  4442.2     .08       0  4687.4     .05       0
  4781.7     .08       0  4995.7     .07       0  5001.7     .08       0
  5062.3     .05       0
#XS Ineff= 2 ,-1
 4878.63  4962.5441.0598 5036.83 5138.42441.1147
Permanent Ineff=
       F       F
Bank Sta=4968.6,5028.8
XS Rating Curve= 0 ,0
Exp/Cntr=0.3,0.1

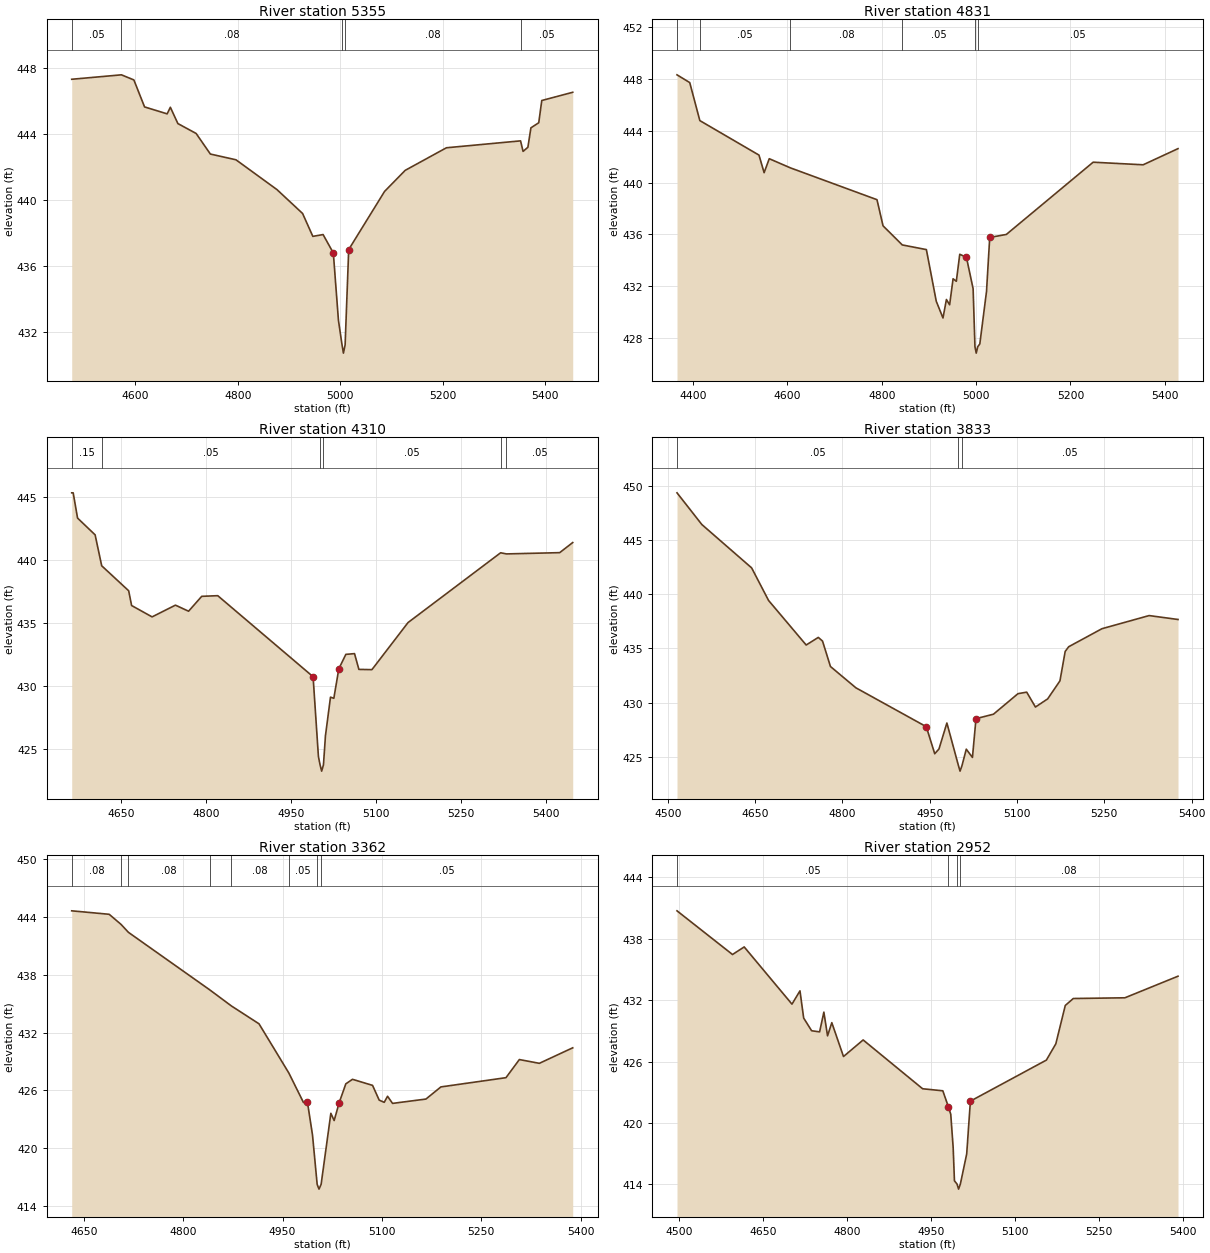
Type RM Length L Ch R = 1 ,5355    ,524,524,524
BEGIN DESCRIPTION:
UNT 054 IN UKCR 11.0
END DESCRIPTION:
XS GIS Cut Line= 5
      3599152.22     10612603.64      3598946.52     10612752.05
      3598597.57     10612757.26        3598371.      10612780.7
      3598246.02     10612858.81
#Sta/Elev= 30
    4476  447.34    4573  447.61  4597.3   447.3  4618.2  445.66  4662.3  445.24
  4668.5  445.64  4683.2  444.65  4718.8  444.05  4746.6   442.8  4796.6  442.45
  4876.6  440.64  4926.6  439.19  4946.6   437.8  4966.6  437.91  4986.6  436.79
  4996.6  432.69  5003.6  431.21  5006.3  430.71  5009.6  431.21  5016.6     437
  5086.6  440.53  5126.9  441.81  5207.3  443.18    5352   443.6  5356.9  442.96
  5366.3  443.21  5372.2  444.39  5387.5   444.7  5393.4  446.05  5453.8  446.55
#Mann= 5 ,-1 , 0
    4476     .05       0    4573     .08       0  5003.6     .07       0
  5009.6     .08       0    5352     .05       0
Bank Sta=4986.6,5016.6
XS Rating Curve= 0 ,0
Exp/Cntr=0.3,0.1

Type RM Length L Ch R = 1 ,4831    ,521,521,521
BEGIN DESCRIPTION:
UNT 054 IN UKCR 10.0
END DESCRIPTION:
XS GIS Cut Line= 3
      3599079.37     10612064.54      3598605.38     10612267.67
      3598230.81     10612665.65
#Sta/Elev= 30
    4366  448.33    4393  447.73  4414.4  444.79  4539.8  442.12  4550.7  440.76
  4561.6  441.84  4606.6  441.13    4790  438.67  4802.8  436.65  4843.6  435.17
  4894.7  434.81  4915.7  430.81  4929.9  429.52  4937.2  430.95    4944  430.54
  4951.3  432.55  4958.2  432.36  4965.5  434.45  4979.7   434.2  4993.8  431.78
  4997.7   427.3  5000.4   426.8  5003.7   427.3    5008  427.51  5022.2  431.57
    5029  435.75  5064.2  435.98  5248.3  441.57  5354.3  441.37  5428.2  442.62
#Mann= 6 ,-1 , 0
    4366      .1       0  4414.4     .05       0  4606.6     .08       0
  4843.6     .05       0  4997.7     .04       0  5003.7     .05       0
Bank Sta=4979.7,5029
XS Rating Curve= 0 ,0
Exp/Cntr=0.3,0.1

Type RM Length L Ch R = 1 ,4310    ,477,477,477
BEGIN DESCRIPTION:
UNT 054 IN UKCR 9.0
END DESCRIPTION:
XS GIS Cut Line= 3
      3598799.64     10611810.18      3598399.61     10611910.19
      3597999.64     10612160.17
#Sta/Elev= 30
  4562.5  445.32  4565.1  445.32  4572.8  443.32  4603.8  441.99  4615.4  439.54
    4663  437.56  4668.2  436.39  4704.3  435.49  4745.5  436.42  4768.7  435.94
  4791.9  437.12  4820.2  437.17  4988.4  430.75  4997.8  424.43  5000.7  423.77
  5003.5  423.27  5006.7  423.77  5010.2  426.07  5019.1  429.13    5025  429.04
  5033.8  431.38  5046.2  432.52  5061.5  432.58  5069.2  431.33  5092.2  431.31
  5155.9  435.04  5319.3  440.57  5329.6  440.48  5423.5  440.58  5446.5  441.38
#Mann= 6 ,-1 , 0
  4562.5     .15       0  4615.4     .05       0  5000.7     .04       0
  5006.7     .05       0  5319.3     .08       0  5329.6     .05       0
Bank Sta=4988.4,5033.8
XS Rating Curve= 0 ,0
Exp/Cntr=0.3,0.1

Type RM Length L Ch R = 1 ,3833    ,471,471,471
BEGIN DESCRIPTION:
UNT 054 IN UKCR 8.0
END DESCRIPTION:
XS GIS Cut Line= 3
      3598649.64     10611210.17      3598249.61     10611510.19
      3598049.61     10611810.19
#Sta/Elev= 30
    4516  449.33  4558.7  446.41  4644.2  442.42  4673.3  439.42  4737.9  435.32
  4758.7  436.02    4766  435.68  4779.6  433.34  4823.3  431.38  4944.2   427.8
  4958.7  425.31    4966  425.75  4979.6  428.14  4999.5  424.21  5002.2  423.71
  5005.5  424.21  5012.9  425.73  5023.5  424.97  5029.6  428.54  5059.6  428.95
  5101.7  430.84  5116.7  430.98  5131.7  429.61  5152.7  430.36  5173.8  432.02
  5182.8  434.73  5188.8  435.16  5245.9  436.82    5327  438.03  5376.6  437.67
#Mann= 3 ,-1 , 0
    4516     .05       0  4999.5     .04       0  5005.5     .05       0
Bank Sta=4944.2,5029.6
XS Rating Curve= 0 ,0
Exp/Cntr=0.3,0.1

Type RM Length L Ch R = 1 ,3362    ,410,410,410
BEGIN DESCRIPTION:
UNT 054 IN UKCR 7.0
END DESCRIPTION:
XS GIS Cut Line= 3
      3598349.62     10610860.17      3598099.61     10611110.19
      3598049.61      10611510.2
#Sta/Elev= 30
  4631.5  444.64  4688.1  444.28  4706.2  443.22  4717.1  442.41  4839.7  436.45
  4872.8  434.76  4914.4  432.91  4959.4  427.81  4981.5  424.75  4987.6  424.75
  4995.2  421.36  5002.2  416.25    5005  415.75  5008.2  416.25  5022.9  423.62
  5027.9  422.87  5035.5  424.73  5045.5  426.68  5055.6  427.15  5085.9  426.52
  5095.9  424.99  5103.5  424.76  5108.5  425.39  5116.1  424.65  5166.5   425.1
  5189.1  426.36  5287.4  427.32  5307.6   429.2  5337.8  428.81  5388.2  430.42
#Mann= 8 ,-1 , 0
  4631.5     .08       0  4706.2     .05       0  4717.1     .08       0
  4839.7     .05       0  4872.8     .08       0  4959.4     .05       0
  5002.2     .04       0  5008.2     .05       0
Bank Sta=4987.6,5035.5
XS Rating Curve= 0 ,0
Exp/Cntr=0.3,0.1

Type RM Length L Ch R = 1 ,2952    ,596,596,596
BEGIN DESCRIPTION:
UNT 054 IN UKCR 6.0
END DESCRIPTION:
XS GIS Cut Line= 3
      3598199.63     10610810.17      3597799.61     10611160.19
      3597699.62     10611510.14
#Sta/Elev= 30
  4495.7  440.74  4594.9  436.47  4615.8  437.21  4701.2  431.62  4715.5  432.92
  4722.1  430.26  4736.3  429.02  4750.6  428.91  4758.2  430.84  4764.8  428.52
  4772.4  429.81  4793.3   426.5  4828.4  428.12  4934.7  423.35  4970.8  423.15
  4980.7   421.6    4985  420.86  4989.3  417.61  4991.6  414.35  4996.2  414.04
    4999  413.54  5002.2  414.04  5013.5  416.98  5020.1  422.14  5155.9  426.15
  5172.8  427.74  5189.7  431.49    5204  432.17  5296.3  432.24  5391.2  434.35
#Mann= 4 ,-1 , 0
  4495.7     .05       0  4980.7     .08       0  4996.2     .07       0
  5002.2     .08       0
Bank Sta=4980.7,5020.1
XS Rating Curve= 0 ,0
Exp/Cntr=0.3,0.1

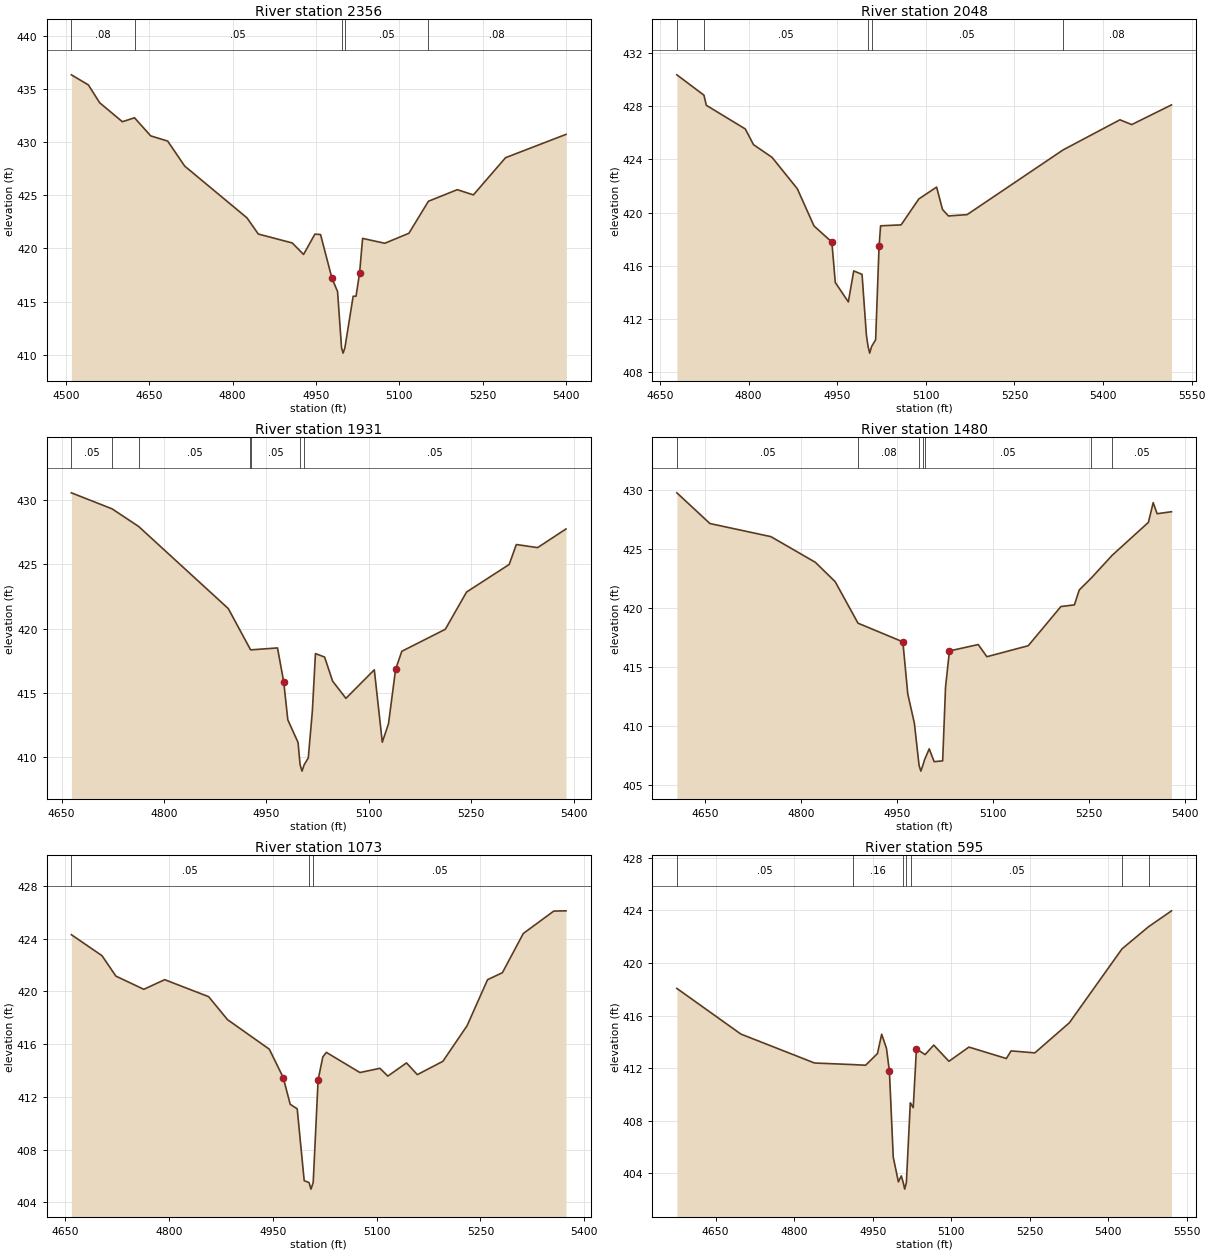
Type RM Length L Ch R = 1 ,2356    ,308,308,308
BEGIN DESCRIPTION:
UNT 054 IN UKCR 5.0
END DESCRIPTION:
XS GIS Cut Line= 3
      3598049.63     10610760.18      3597549.61     10610860.19
      3597399.62     10611210.17
#Sta/Elev= 30
  4509.6  436.32  4540.2  435.37  4560.6  433.69  4601.4  431.91  4623.3  432.28
  4652.4  430.58    4683  430.09  4713.6  427.74  4825.8  422.87  4846.2  421.35
  4907.3  420.51  4927.7  419.43  4948.1  421.34  4958.3   421.3  4978.7  417.21
  4988.9  415.94  4996.1  410.65  4998.9  410.15  5002.1  410.65    5017   415.5
  5022.2   415.5  5028.6   417.7    5034  420.94  5073.9  420.48  5117.4  421.42
  5152.5  424.43  5204.5  425.52  5233.5  425.03  5291.5  428.53  5400.3  430.72
#Mann= 5 ,-1 , 0
  4509.6     .08       0  4623.3     .05       0  4996.1     .04       0
  5002.1     .05       0  5152.5     .08       0
Bank Sta=4978.7,5028.6
XS Rating Curve= 0 ,0
Exp/Cntr=0.3,0.1

Type RM Length L Ch R = 1 ,2048    ,117,117,117
BEGIN DESCRIPTION:
Mapping XS 57c6d3dd
END DESCRIPTION:
XS GIS Cut Line= 3
      3597659.21     10610470.79      3597360.59     10610647.88
      3597339.75     10611137.46
#Sta/Elev= 30
  4678.7  430.35  4724.5  428.82  4728.5  428.06  4794.5  426.28  4808.4   425.1
  4839.7  424.15  4882.5  421.79  4910.8  418.99    4941  417.78  4946.8  414.74
  4968.9  413.28    4978  415.61  4992.1  415.35  4999.5  410.77  5002.3  409.93
    5005  409.43  5008.3  409.93  5015.1  410.44  5020.9  417.46  5023.5     419
  5058.2  419.07  5088.2  421.02  5118.3  421.91  5128.3  420.23  5138.3  419.74
  5169.9  419.84  5332.2   424.7  5428.6  426.97  5448.6  426.61  5515.9  428.09
#Mann= 5 ,-1 , 0
  4678.7     .08       0  4724.5     .05       0  5002.3     .04       0
  5008.3     .05       0  5332.2     .08       0
Bank Sta=4941,5020.9
XS Rating Curve= 0 ,0
Exp/Cntr=0.3,0.1

Type RM Length L Ch R = 1 ,1931    ,451,451,451
BEGIN DESCRIPTION:
UNT 054 IN UKCR 4.0
END DESCRIPTION:
XS GIS Cut Line= 3
      3597599.59      10610360.2      3597299.61     10610560.19
      3596949.65     10610660.18
#Sta/Elev= 30
  4664.4  430.57  4724.2  429.32    4763  427.95  4894.2  421.57  4926.6  418.39
  4927.2  418.36  4966.3  418.51  4975.4  415.88  4981.4  412.92  4996.4  411.16
  4999.4  409.43  5002.2  408.93  5005.4  409.43  5011.4  409.96  5017.4  413.63
  5021.9  418.07  5035.3   417.8    5047  415.93  5066.5  414.59  5108.1  416.81
  5119.8  411.18  5128.9  412.62  5139.3  416.85  5148.4  418.25  5212.1  419.96
  5243.3  422.86  5305.7     425  5316.1  426.55  5347.3  426.31  5388.9  427.76
#Mann= 7 ,-1 , 0
  4664.4     .05       0  4724.2     .08       0    4763     .05       0
  4926.6     .08       0  4927.2     .05       0  4999.4     .04       0
  5005.4     .05       0
Bank Sta=4975.4,5139.3
XS Rating Curve= 0 ,0
Exp/Cntr=0.3,0.1

Type RM Length L Ch R = 1 ,1480    ,407,407,407
BEGIN DESCRIPTION:
UNT 054 IN UKCR 3.0
END DESCRIPTION:
XS GIS Cut Line= 3
      3597549.63     10610310.19      3597149.61     10610210.19
       3596849.6     10610410.19
#Sta/Elev= 30
  4606.2  429.72  4657.8  427.12  4753.1  426.01  4822.7  423.83  4853.6  422.19
  4889.2  418.68  4959.3   417.1    4967  412.68  4977.3  410.21  4984.6  406.65
  4987.4  406.15  4990.6  406.65  4993.4  407.14  5000.5  408.04  5008.2  406.95
  5021.5  407.02    5026  413.27  5032.1  416.33  5077.1  416.87  5090.6  415.84
  5155.2  416.77  5206.3  420.09  5227.4  420.23  5234.9  421.49    5254  422.52
  5286.4  424.43    5343  427.22  5350.5  428.89  5356.6  427.95  5379.1  428.12
#Mann= 7 ,-1 , 0
  4606.2     .05       0  4889.2     .08       0  4984.6     .04       0
  4990.6     .08       0  4993.4     .05       0    5254     .08       0
  5286.4     .05       0
Bank Sta=4959.3,5032.1
XS Rating Curve= 0 ,0
Exp/Cntr=0.3,0.1

Type RM Length L Ch R = 1 ,1073    ,478,478,478
BEGIN DESCRIPTION:
UNT 054 IN UKCR 2.0
END DESCRIPTION:
XS GIS Cut Line= 3
      3597433.49     10609831.91      3596968.23     10609887.47
      3596756.43     10610012.46
#Sta/Elev= 30
  4659.2  424.29  4703.4   422.7  4723.5  421.15  4763.8  420.15    4794  420.88
  4857.5  419.59  4884.7  417.85  4945.1  415.61  4965.2  413.46  4975.3  411.43
  4985.4  411.09  4995.5  405.64  5002.5   405.5  5005.3     405  5008.5   405.5
  5015.6  413.29  5022.4  415.02  5027.5  415.37    5076  413.84  5104.9  414.16
  5116.3  413.57  5143.3  414.57  5158.9  413.68  5195.8  414.69  5230.7  417.38
  5260.4  420.88  5281.8  421.41    5312  424.38    5356  426.08  5373.7   426.1
#Mann= 3 ,-1 , 0
  4659.2     .05       0  5002.5     .03       0  5008.5     .05       0
Bank Sta=4965.2,5015.6
XS Rating Curve= 0 ,0
Exp/Cntr=0.3,0.1

Type RM Length L Ch R = 1 ,595     ,446,446,446
BEGIN DESCRIPTION:
Mapping XS c9974921
END DESCRIPTION:
XS GIS Cut Line= 4
      3597485.61     10609512.47      3597173.09     10609439.55
      3596975.17      10609533.3      3596784.41     10609890.54
#Sta/Elev= 30
    4576  418.07  4698.2   414.6  4838.9   412.4  4911.5  412.28  4936.5  412.23
  4959.2  413.12  4967.2  414.59  4976.4  413.51    4982  411.77  4989.3  405.24
  4999.2  403.36  5004.7  403.82  5008.4  403.31  5011.2  402.81  5014.4  403.31
  5021.9  409.37    5023   409.3  5027.5     409  5033.6  413.47  5050.2  413.04
  5066.7  413.76  5095.7  412.53  5133.9  413.61  5205.4  412.74  5214.4  413.32
  5259.8  413.17  5325.8  415.46  5426.4  421.08    5477  422.76  5520.9  423.97
#Mann= 7 ,-1 , 0
    4576     .05       0  4911.5     .16       0  5008.4     .07       0
  5014.4     .16       0    5023     .05       0  5426.4     .08       0
    5477     .05       0
Bank Sta=4982,5033.6
XS Rating Curve= 0 ,0
Exp/Cntr=0.3,0.1

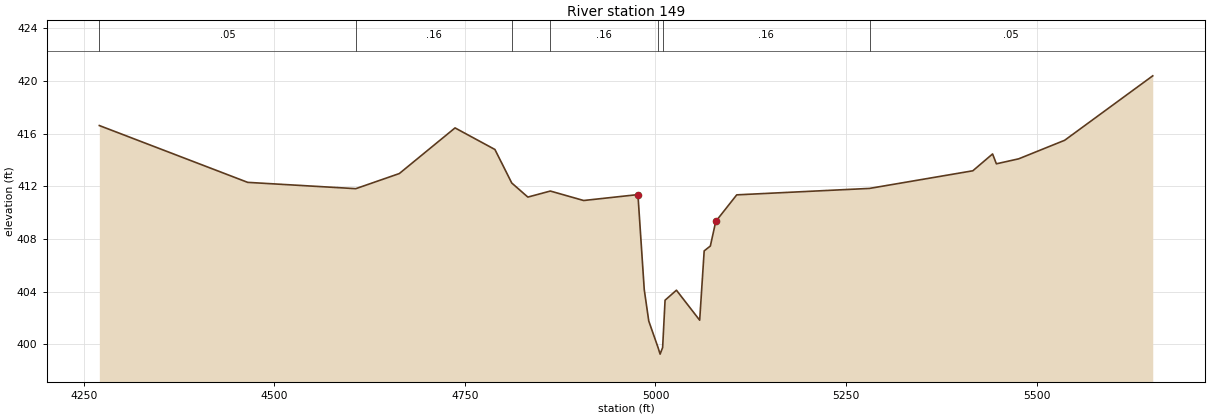
Type RM Length L Ch R = 1 ,149     ,0,0,0
BEGIN DESCRIPTION:
UNT 054 IN UKCR 1.0
END DESCRIPTION:
XS GIS Cut Line= 4
      3597485.55     10609439.54      3596888.36     10609255.52
      3596714.75     10609366.63      3596666.14     10609915.26
#Sta/Elev= 30
  4270.5  416.62  4465.1   412.3  4606.9  411.82    4664  412.97  4737.1  416.44
  4789.4   414.8  4811.5  412.25  4832.6  411.18  4862.1  411.64  4905.8  410.92
    4977  411.37  4985.3  404.14  4991.2  401.76  5003.4  399.74  5006.1  399.24
  5009.4  399.74  5012.6  403.34  5027.5   404.1    5058  401.82  5063.9  407.09
    5072  407.46  5079.1  409.33  5106.6  411.35  5280.8  411.84  5416.3  413.18
  5442.2  414.46  5447.2  413.71  5476.5  414.09  5536.8   415.5  5652.3   420.4
#Mann= 7 ,-1 , 0
  4270.5     .05       0  4606.9     .16       0  4811.5     .05       0
  4862.1     .16       0  5003.4     .07       0  5009.4     .16       0
  5280.8     .05       0
Bank Sta=4977,5079.1
XS Rating Curve= 0 ,0
Exp/Cntr=0.3,0.1

Chan Stop Cuts=-1
Use User Specified Reach Order=0
Composite Channel Slope=5