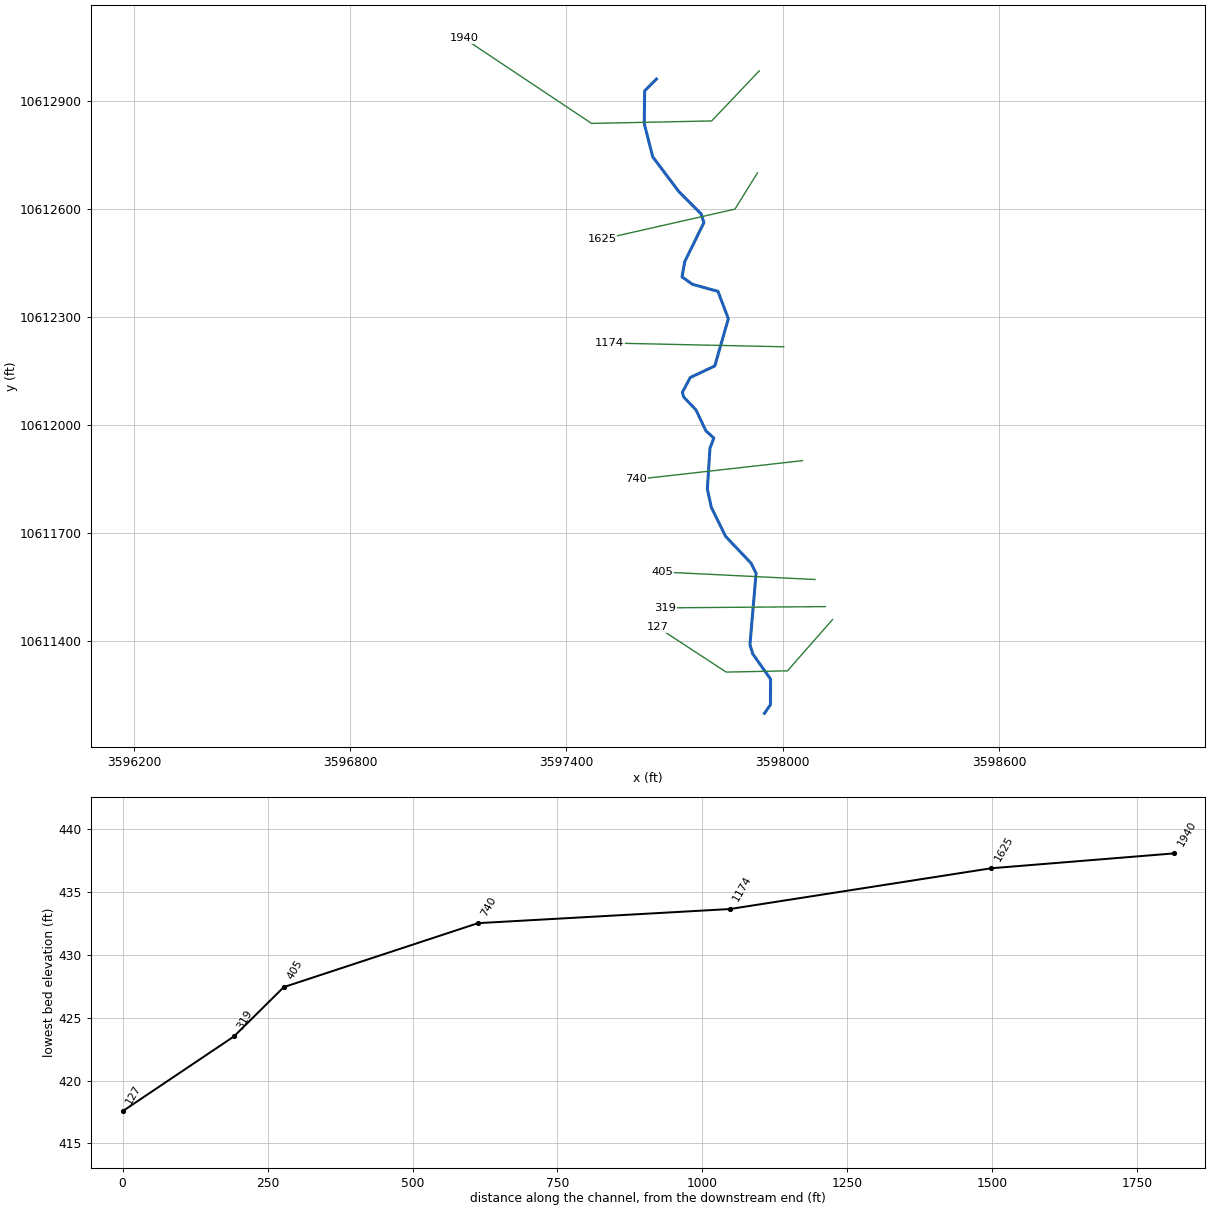
--- UNT 055 IN UKCR.prj (project) ---

Proj Title=UNT 055 IN UKCR Base Level Engineering
Current Plan=p01
Default Exp/Contr=0.3,0.1
English Units
Geom File=g01
Flow File=f01
Plan File=p01
Y Axis Title=Elevation
X Axis Title(PF)=Main Channel Distance
X Axis Title(XS)=Station
BEGIN DESCRIPTION:
UNT 055 IN UKCR
END DESCRIPTION:
DSS Export Rating Curves= 0
DSS Export Rating Curve Sorted= 0
DSS Export Volume Flow Curves= 0
DXF OffsetX= 0
DXF OffsetY= 0
DXF ScaleX= 1
DXF ScaleY= 10

--- UNT 055 IN UKCR.p01 (plan) ---

Plan Title=Multiple Run
Short Identifier=Multiple
Geom File=g01
Flow File=f01
Subcritical Flow
K Sum by GR= 0
Std Step Tol= 0.01
Critical Tol= 0.01
Num of Std Step Trials= 20
Max Error Tol= 0.3
Flow Tol Ratio= 0.001
Split Flow NTrial= 30
Split Flow Tol= 0.02
Split Flow Ratio= 0.02
Log Output Level= 0
Friction Slope Method= 1
Unsteady Friction Slope Method= 2
Unsteady Bridges Friction Slope Method= 1
Parabolic Critical Depth
Global Vel Dist=  1 , 1 , 1
Global Log Level= 0
CheckData=True
Encroach Param= -1, 0, 0, 0
BEGIN DESCRIPTION:
Multiple Run
END DESCRIPTION:

--- UNT 055 IN UKCR.f01 (steady flow) ---

Flow Title=Multiple
Number of Profiles=7
Profile Names=10-year,25-year,50-year,1pct_min,100-year,1pct_plu,500-year
River Rch & RM= UNT 055 IN UKCR,Reach-1,1940
     263     329     378     319     432     584     559
Boundary for River Rch & Prof#=UNT 055 IN UKCR,Reach-1,1
Up Type=0
Dn Type=3
Dn Slope=0.005
Boundary for River Rch & Prof#=UNT 055 IN UKCR,Reach-1,2
Up Type=0
Dn Type=3
Dn Slope=0.005
Boundary for River Rch & Prof#=UNT 055 IN UKCR,Reach-1,3
Up Type=0
Dn Type=3
Dn Slope=0.005
Boundary for River Rch & Prof#=UNT 055 IN UKCR,Reach-1,4
Up Type=0
Dn Type=3
Dn Slope=0.005
Boundary for River Rch & Prof#=UNT 055 IN UKCR,Reach-1,5
Up Type=0
Dn Type=3
Dn Slope=0.005
Boundary for River Rch & Prof#=UNT 055 IN UKCR,Reach-1,6
Up Type=0
Dn Type=3
Dn Slope=0.005
Boundary for River Rch & Prof#=UNT 055 IN UKCR,Reach-1,7
Up Type=0
Dn Type=3
Dn Slope=0.005

--- UNT 055 IN UKCR.g01 (geometry) ---

Geom Title=Existing Conditions
Program Version=4.10

River Reach=UNT 055 IN UKCR ,Reach-1
Reach XY= 30
      3597649.61     10612960.19      3597616.99     10612927.57
      3597615.88      10612836.6      3597639.49     10612744.24
      3597712.66     10612647.13      3597773.82     10612585.92
      3597781.42     10612562.04      3597728.25     10612453.54
      3597720.65     10612411.22      3597749.95      10612390.6
      3597820.48     10612371.07      3597849.25       10612295.
       3597811.5       10612164.       3597743.5       10612132.
      3597721.75       10612091.      3597725.25       10612078.
       3597759.5       10612042.        3597787.       10611984.
        3597809.       10611964.      3597798.25       10611936.
        3597791.       10611822.        3597802.       10611772.
      3597841.75       10611691.        3597912.       10611617.
      3597926.25       10611589.      3597909.25       10611391.
        3597917.       10611365.       3597966.5       10611295.
        3597966.       10611224.       3597949.5       10611200.

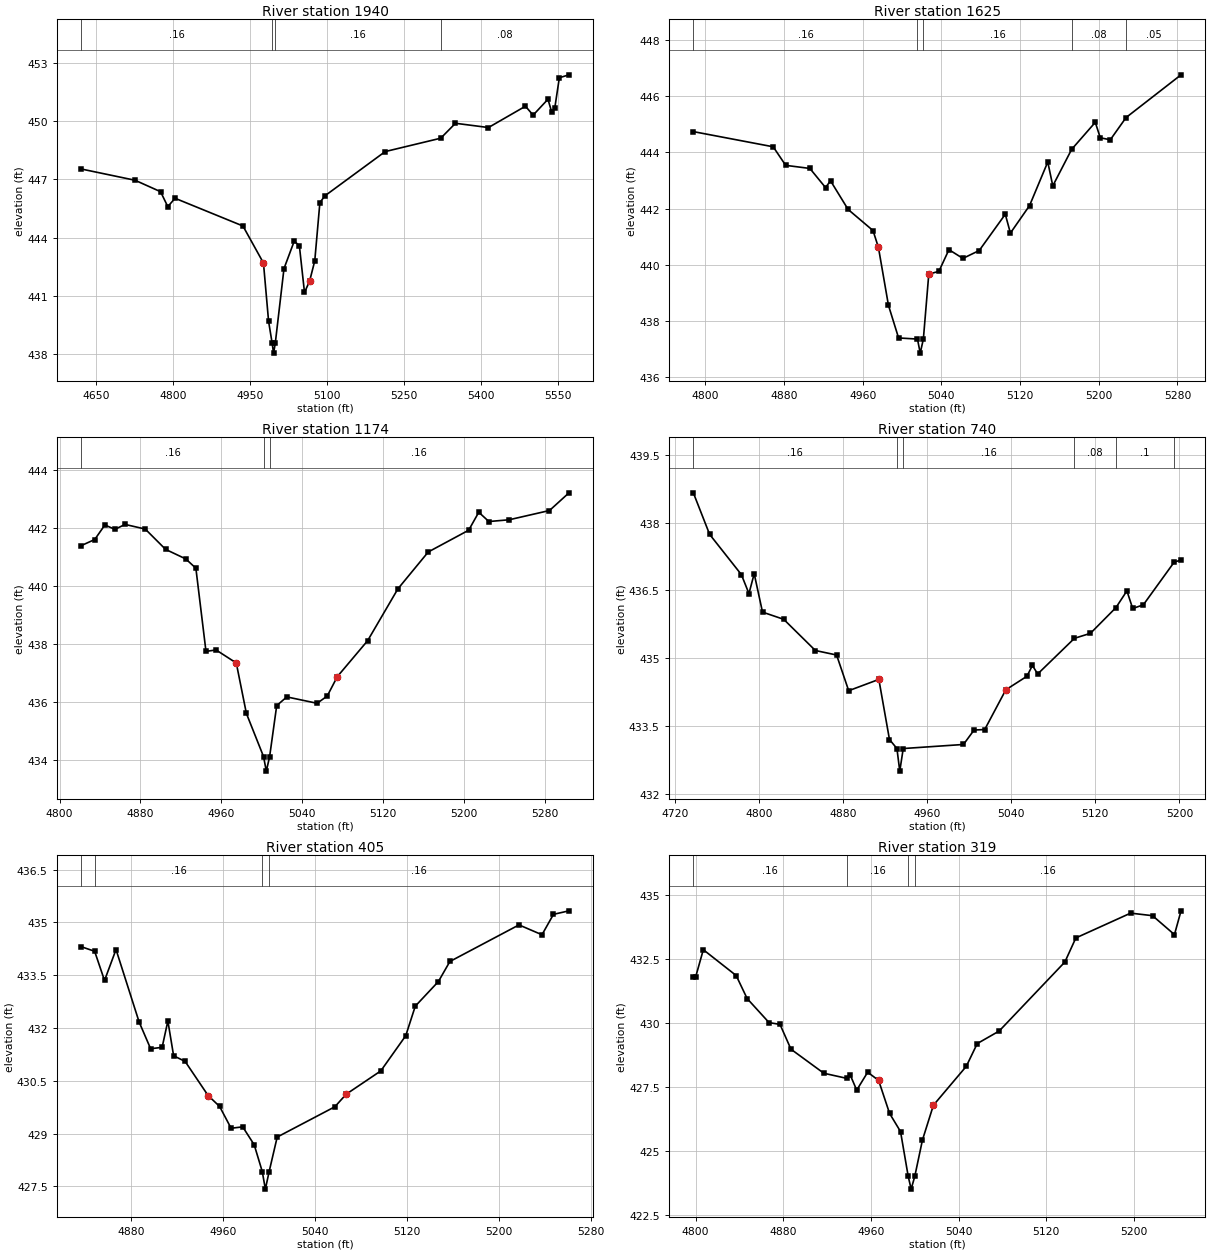
Type RM Length L Ch R = 1 ,1940    ,315,315,315
BEGIN DESCRIPTION:
UNT 055 IN UKCR 2.0
END DESCRIPTION:
XS GIS Cut Line= 4
        3597935.       10612983.      3597803.04     10612844.09
      3597469.71     10612837.15      3597115.51     10613073.28
#Sta/Elev= 30
  4621.2  447.54    4726  446.96  4775.7  446.37  4789.8   445.6    4804  446.03
  4936.3   444.6  4976.3  442.69  4986.3  439.68  4993.3  438.54    4996  438.04
  4999.3  438.54  5016.3   442.4  5036.3  443.82  5046.3  443.58  5056.3  441.17
  5066.3  441.76  5076.3   442.8  5086.3  445.81  5096.3  446.16  5213.6  448.44
  5321.9  449.13  5350.6   449.9  5414.9  449.68    5487  450.78    5502  450.32
  5530.9  451.14  5538.1  450.49  5544.1  450.67  5553.1  452.25  5571.9   452.4
#Mann= 4 ,-1 , 0
  4621.2     .16       0  4993.3     .07       0  4999.3     .16       0
  5321.9     .08       0
Bank Sta=4976.3,5066.3
XS Rating Curve= 0 ,0
Exp/Cntr=0.3,0.1

Type RM Length L Ch R = 1 ,1625    ,451,451,451
BEGIN DESCRIPTION:
Mapping XS 67e9bec6
END DESCRIPTION:
XS GIS Cut Line= 3
      3597930.03     10612699.96      3597867.53     10612599.27
      3597499.46     10612515.93
#Sta/Elev= 30
  4787.8  444.74    4869   444.2  4881.7  443.54  4906.3  443.43  4922.2  442.75
  4927.3  442.99  4945.2  441.97  4970.5  441.22    4976  440.62  4986.2  438.56
  4996.5   437.4  5015.7  437.36  5018.5  436.86  5021.7  437.36  5027.2  439.67
  5037.5  439.77  5047.7  440.54  5061.9  440.23  5078.5  440.51    5105   441.8
  5110.2  441.13  5129.7  442.11  5148.2  443.66  5153.3  442.81  5172.5  444.11
  5196.5  445.07  5201.6  444.52  5211.8  444.45  5227.8  445.24  5283.7  446.76
#Mann= 5 ,-1 , 0
  4787.8     .16       0  5015.7     .07       0  5021.7     .16       0
  5172.5     .08       0  5227.8     .05       0
Bank Sta=4976,5027.2
XS Rating Curve= 0 ,0
Exp/Cntr=0.3,0.1

Type RM Length L Ch R = 1 ,1174    ,434,434,434
BEGIN DESCRIPTION:
Mapping XS 53bd6088
END DESCRIPTION:
XS GIS Cut Line= 2
      3598002.94     10612217.33      3597520.35     10612227.74
#Sta/Elev= 30
  4821.5   441.4  4834.8  441.61  4844.8  442.11  4854.8  441.96  4864.8  442.13
  4884.8  441.97  4904.9  441.27  4924.9  440.94  4934.9  440.62  4944.9  437.75
  4954.9   437.8  4974.9  437.35  4984.9  435.61  5001.9  434.12  5004.6  433.62
  5007.9  434.12  5014.9  435.88  5024.9  436.18  5054.9  435.96  5064.9  436.21
  5074.9  436.88  5104.9  438.12  5134.9  439.91  5164.9  441.18  5204.9  441.93
  5214.9  442.55  5224.9  442.23  5244.9  442.29  5284.9  442.61  5304.2  443.22
#Mann= 3 ,-1 , 0
  4821.5     .16       0  5001.9     .07       0  5007.9     .16       0
Bank Sta=4974.9,5074.9
XS Rating Curve= 0 ,0
Exp/Cntr=0.3,0.1

Type RM Length L Ch R = 1 ,740     ,335,335,335
BEGIN DESCRIPTION:
Mapping XS b1cdd233
END DESCRIPTION:
XS GIS Cut Line= 2
      3598055.02     10611901.35      3597593.95     10611849.35
#Sta/Elev= 30
  4737.5  438.66    4753  437.74  4783.2  436.85  4790.4  436.43  4795.4  436.87
  4803.3  436.02  4823.5  435.86  4853.6  435.17  4873.8  435.07  4885.3  434.28
    4914  434.53  4924.1   433.2  4931.2     433  4933.9   432.5  4937.2     433
  4994.5  433.09  5004.6  433.41  5014.7  433.42  5034.8   434.3  5054.9   434.6
  5060.1  434.84  5065.1  434.65  5100.1  435.44  5115.3  435.55  5139.6  436.12
    5150  436.49  5155.5   436.1  5165.6  436.18  5195.1  437.13  5201.5  437.17
#Mann= 6 ,-1 , 0
  4737.5     .16       0  4931.2     .07       0  4937.2     .16       0
  5100.1     .08       0  5139.6      .1       0  5195.1     .08       0
Bank Sta=4914,5034.8
XS Rating Curve= 0 ,0
Exp/Cntr=0.3,0.1

Type RM Length L Ch R = 1 ,405     ,86,86,86
BEGIN DESCRIPTION:
Mapping XS f215367c
END DESCRIPTION:
XS GIS Cut Line= 2
       3598089.8     10611571.49      3597666.11     10611592.33
#Sta/Elev= 30
  4836.8  434.31  4848.4  434.18    4857  433.35    4867  434.23  4887.1  432.17
  4897.1  431.41  4907.1  431.45  4912.1   432.2  4917.1  431.21  4927.1  431.05
  4947.1  430.08  4957.1  429.77  4967.1  429.15  4977.2  429.19  4987.2  428.68
  4994.2  427.92  4996.9  427.42  5000.2  427.92  5007.2   428.9  5057.3  429.76
  5067.3  430.12  5097.3  430.78    5119  431.78  5127.3  432.62  5147.4  433.32
  5157.4  433.89  5217.5  434.93  5237.5  434.65  5247.5  435.23    5261  435.33
#Mann= 4 ,-1 , 0
  4836.8     .05       0  4848.4     .16       0  4994.2     .07       0
  5000.2     .16       0
Bank Sta=4947.1,5067.3
XS Rating Curve= 0 ,0
Exp/Cntr=0.3,0.1

Type RM Length L Ch R = 1 ,319     ,192,192,192
BEGIN DESCRIPTION:
Mapping XS 72f62837
END DESCRIPTION:
XS GIS Cut Line= 2
      3598118.69      10611496.3       3597673.6     10611492.83
#Sta/Elev= 30
  4797.9  431.78  4799.9  431.78    4807  432.86    4837  431.85    4847  430.95
    4867  430.01    4877  429.94    4887  428.97    4917  428.03    4938  427.83
  4941.2  427.95    4947  427.37    4957  428.07    4967  427.75    4977  426.46
    4987  425.75    4994     424  4996.7   423.5    5000     424    5007  425.42
    5017  426.78    5047   428.3    5057  429.19    5077  429.68    5137  432.38
    5147  433.32    5197  434.29    5217  434.19    5237  433.45    5243  434.38
#Mann= 4 ,-1 , 0
  4797.9     .16       0    4938     .16       0    4994     .07       0
    5000     .16       0
Bank Sta=4967,5017
XS Rating Curve= 0 ,0
Exp/Cntr=0.3,0.1

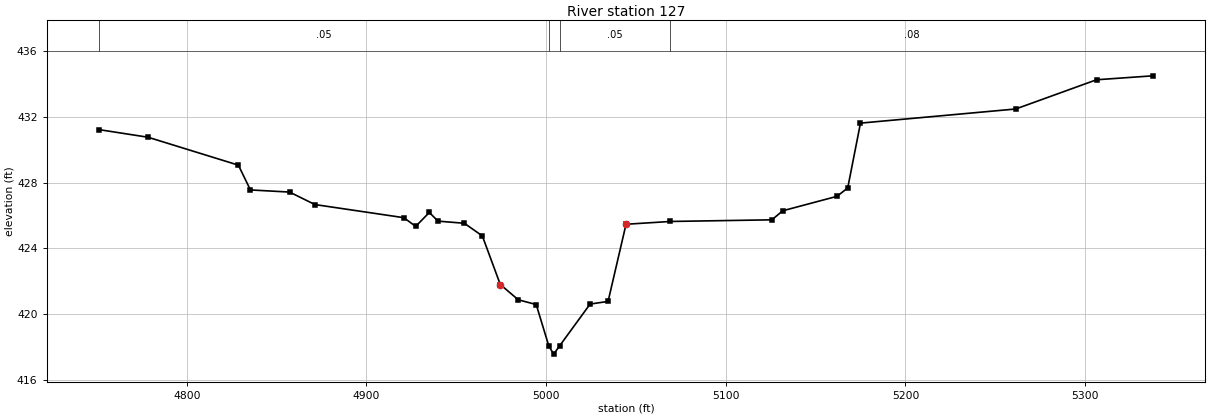
Type RM Length L Ch R = 1 ,127     ,0,0,0
BEGIN DESCRIPTION:
UNT 055 IN UKCR 1.0
END DESCRIPTION:
XS GIS Cut Line= 4
      3598138.34     10611460.35      3598013.36     10611318.02
      3597843.23     10611314.55      3597653.45     10611438.77
#Sta/Elev= 30
  4751.3  431.23  4778.4  430.77  4828.7  429.07  4835.4  427.56  4857.2  427.43
  4871.3  426.67  4920.8  425.87  4927.4  425.34    4935  426.19  4939.8  425.66
  4954.5  425.53  4964.5  424.76  4974.5   421.8  4984.5  420.87  4994.5  420.58
  5001.5  418.06  5004.2  417.56  5007.5  418.06  5024.5  420.61  5034.5  420.77
  5044.5  425.47  5069.2  425.64  5125.7  425.74  5131.7  426.29  5161.9  427.17
  5167.9  427.68    5175  431.63  5261.4  432.49  5306.4  434.27  5337.7  434.51
#Mann= 4 ,-1 , 0
  4751.3     .05       0  5001.5     .04       0  5007.5     .05       0
  5069.2     .08       0
Bank Sta=4974.5,5044.5
XS Rating Curve= 0 ,0
Exp/Cntr=0.3,0.1

Chan Stop Cuts=-1
Use User Specified Reach Order=0
Composite Channel Slope=5