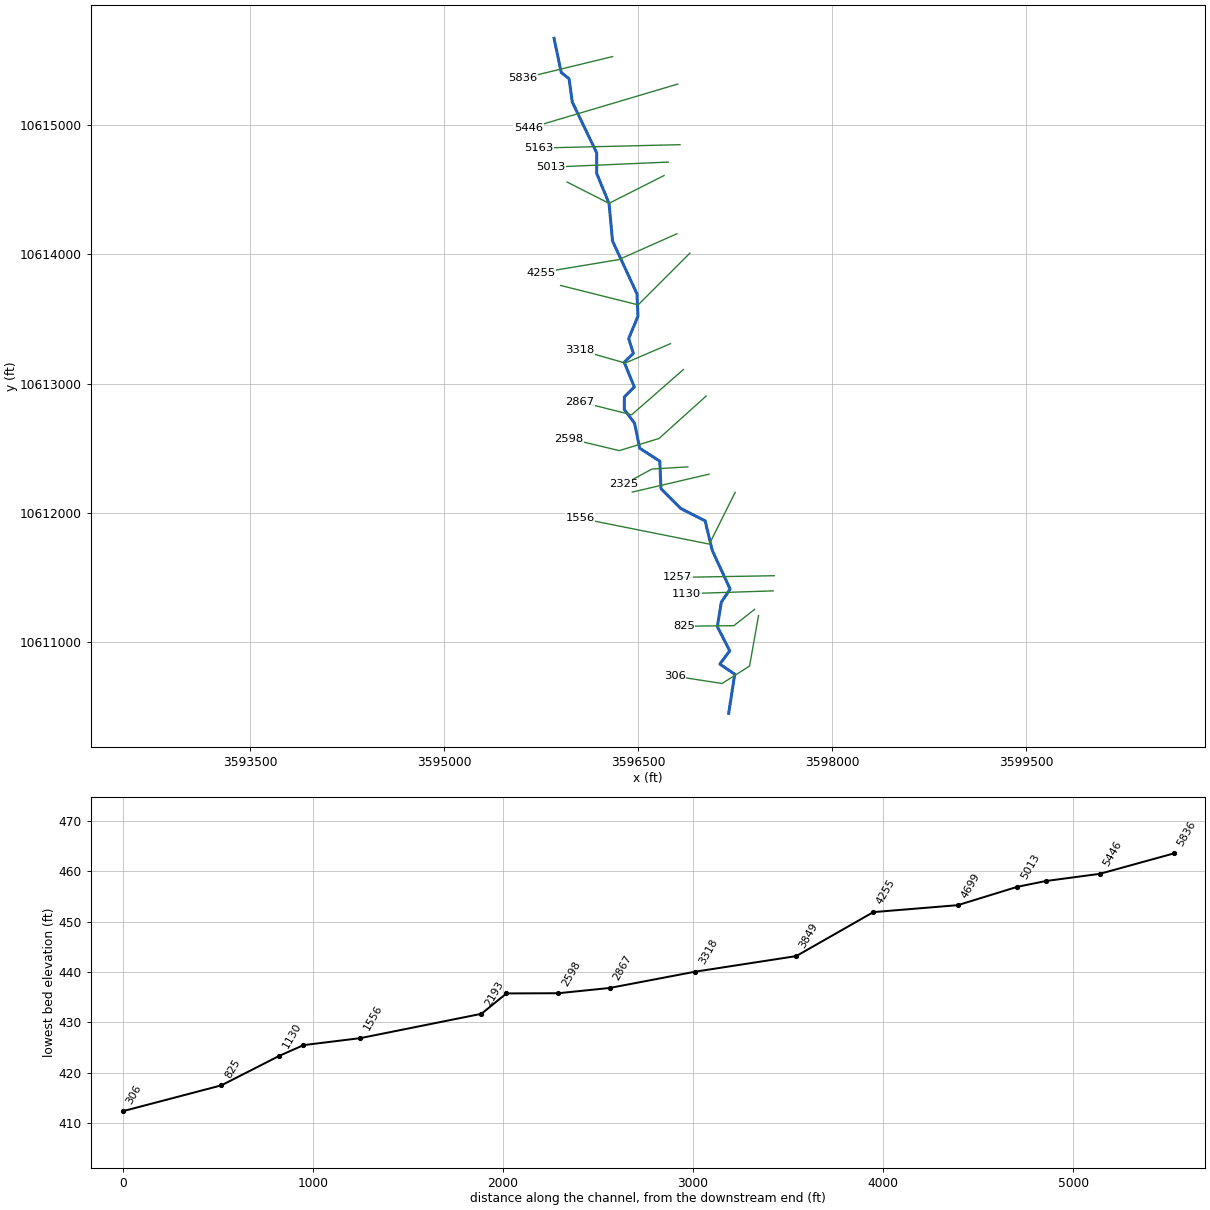
--- UNT 056 IN UKCR.prj (project) ---

Proj Title=UNT 056 IN UKCR Base Level Engineering
Current Plan=p01
Default Exp/Contr=0.3,0.1
English Units
Geom File=g01
Flow File=f01
Plan File=p01
BEGIN DESCRIPTION:
UNT 056 IN UKCR
END DESCRIPTION:

--- UNT 056 IN UKCR.p01 (plan) ---

Plan Title=Multiple Run
Short Identifier=Multiple
Geom File=g01
Flow File=f01
Subcritical Flow
K Sum by GR= 0
Std Step Tol= 0.01
Critical Tol= 0.01
Num of Std Step Trials= 20
Max Error Tol= 0.3
Flow Tol Ratio= 0.001
Split Flow NTrial= 30
Split Flow Tol= 0.02
Split Flow Ratio= 0.02
Log Output Level= 0
Friction Slope Method= 1
Unsteady Friction Slope Method= 2
Unsteady Bridges Friction Slope Method= 1
Parabolic Critical Depth
Global Vel Dist=  1 , 1 , 1
Global Log Level= 0
CheckData=True
Encroach Param= -1, 0, 0, 0
BEGIN DESCRIPTION:
Multiple Run
END DESCRIPTION:

--- UNT 056 IN UKCR.f01 (steady flow) ---

Flow Title=Multiple
Number of Profiles=7
Profile Names=10-year,25-year,50-year,1pct_min,100-year,1pct_plu,500-year
River Rch & RM= UNT 056 IN UKCR,Reach-1,5836
     370     474     554     476     643     870     860
Boundary for River Rch & Prof#=UNT 056 IN UKCR,Reach-1,1
Up Type=0
Dn Type=3
Dn Slope=0.005
Boundary for River Rch & Prof#=UNT 056 IN UKCR,Reach-1,2
Up Type=0
Dn Type=3
Dn Slope=0.005
Boundary for River Rch & Prof#=UNT 056 IN UKCR,Reach-1,3
Up Type=0
Dn Type=3
Dn Slope=0.005
Boundary for River Rch & Prof#=UNT 056 IN UKCR,Reach-1,4
Up Type=0
Dn Type=3
Dn Slope=0.005
Boundary for River Rch & Prof#=UNT 056 IN UKCR,Reach-1,5
Up Type=0
Dn Type=3
Dn Slope=0.005
Boundary for River Rch & Prof#=UNT 056 IN UKCR,Reach-1,6
Up Type=0
Dn Type=3
Dn Slope=0.005
Boundary for River Rch & Prof#=UNT 056 IN UKCR,Reach-1,7
Up Type=0
Dn Type=3
Dn Slope=0.005

--- UNT 056 IN UKCR.g01 (geometry) ---

Geom Title=Existing Conditions

River Reach=UNT 056 IN UKCR,Reach-1
Reach XY= 30
      3595848.94     10615671.30      3595904.79     10615406.90
      3595965.22     10615359.10      3595989.98     10615178.63
      3596178.80     10614785.89      3596178.51     10614627.03
      3596274.28     10614395.26      3596301.49     10614103.81
      3596490.10     10613696.03      3596498.44     10613523.12
      3596426.25     10613350.00      3596462.22     10613235.21
      3596391.75     10613166.00      3596469.75     10612976.00
      3596393.00     10612899.00      3596392.50     10612801.00
      3596471.75     10612694.00      3596511.25     10612502.00
      3596667.00     10612401.00      3596676.00     10612189.00
      3596828.00     10612036.00      3597017.50     10611940.00
      3597072.50     10611711.00      3597210.75     10611412.00
      3597142.75     10611311.00      3597112.00     10611122.00
      3597207.50     10610935.00      3597131.25     10610832.00
      3597246.50     10610754.00      3597199.50     10610451.00

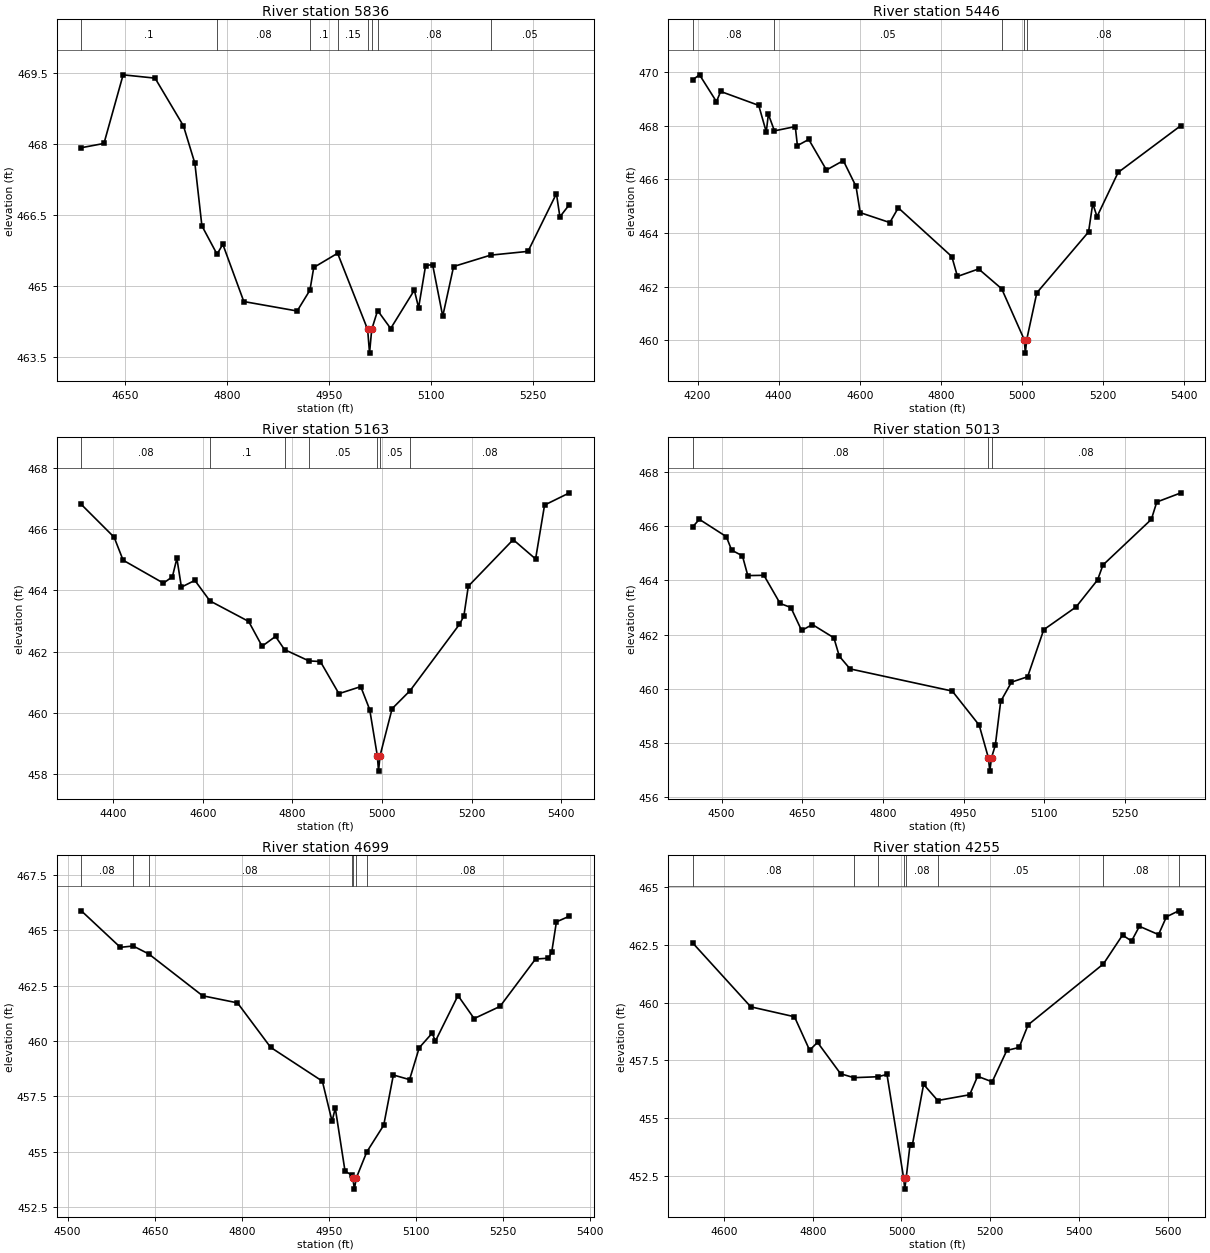
Type RM Length L Ch R = 1,5836,390,390,390
BEGIN DESCRIPTION:
UNT 056 IN UKCR 11.0
END DESCRIPTION:
XS GIS Cut Line= 2
      3596301.99     10615530.26      3595603.88     10615361.15
#Sta/Elev= 30
  4585.7  467.92  4619.0  468.01  4647.2  469.46  4694.2  469.39  4736.0  468.38
  4752.8  467.59  4763.1  466.27  4785.4  465.67  4793.9  465.88  4824.8  464.67
  4903.3  464.47  4922.1  464.91  4927.7  465.39  4962.8  465.69  5007.0  464.08
  5009.8  463.58  5013.0  464.08  5021.7  464.48  5040.9  464.10  5075.7  464.91
  5082.0  464.54  5092.3  465.43  5102.6  465.45  5117.5  464.36  5133.5  465.41
  5187.9  465.65  5243.0  465.73  5284.8  466.95  5289.9  466.46  5304.0  466.72
#Mann=8,-1,0
  4585.7     0.1       0  4785.4    0.08       0  4922.1     0.1       0
  4962.8    0.15       0  5007.0    0.07       0  5013.0    0.15       0
  5021.7    0.08       0  5187.9    0.05       0
Bank Sta=5007,5013
Exp/Cntr=0.3,0.1

Type RM Length L Ch R = 1,5446,283,283,283
BEGIN DESCRIPTION:
Mapping XS 43486812
END DESCRIPTION:
XS GIS Cut Line= 2
      3596805.42     10615317.57      3595650.96     10614974.71
#Sta/Elev= 30
  4188.3  469.72  4204.8  469.90  4246.5  468.90  4256.9  469.28  4350.8  468.76
  4369.4  467.77  4374.6  468.43  4389.6  467.81  4441.0  467.97  4446.2  467.26
  4474.2  467.49  4517.9  466.35  4559.5  466.70  4590.8  465.74  4601.2  464.76
  4674.2  464.39  4695.1  464.94  4827.2  463.12  4841.1  462.38  4893.3  462.66
  4950.2  461.92  5005.9  460.02  5008.6  459.52  5011.9  460.02  5036.9  461.77
  5164.5  464.04  5174.9  465.10  5185.4  464.61  5237.5  466.26  5392.6  468.01
#Mann=5,-1,0
  4188.3    0.08       0  4389.6    0.05       0  4950.2    0.08       0
  5005.9    0.07       0  5011.9    0.08       0
Bank Sta=5005.9,5011.9
Exp/Cntr=0.3,0.1

Type RM Length L Ch R = 1,5163,150,150,150
BEGIN DESCRIPTION:
Mapping XS bc9e26bb
END DESCRIPTION:
XS GIS Cut Line= 2
      3596822.80     10614848.84      3595734.01     10614822.81
#Sta/Elev= 30
  4329.0  466.81  4402.2  465.74  4422.2  464.99  4512.2  464.24  4532.2  464.45
  4542.2  465.05  4552.3  464.11  4582.3  464.33  4615.9  463.66  4702.3  462.99
  4732.3  462.18  4762.3  462.50  4782.3  462.07  4836.8  461.70  4862.3  461.68
  4903.7  460.63  4952.4  460.86  4972.4  460.11  4989.4  458.60  4992.1  458.10
  4995.4  458.60  5022.4  460.14  5062.6  460.73  5172.4  462.89  5182.4  463.16
  5192.4  464.14  5292.5  465.66  5342.5  465.03  5362.5  466.79  5418.1  467.19
#Mann=7,-1,0
  4329.0    0.08       0  4615.9     0.1       0  4782.3    0.08       0
  4836.8    0.05       0  4989.4    0.04       0  4995.4    0.05       0
  5062.6    0.08       0
Bank Sta=4989.4,4995.4
Exp/Cntr=0.3,0.1

Type RM Length L Ch R = 1,5013,314,314,314
BEGIN DESCRIPTION:
UNT 056 IN UKCR 10.0
END DESCRIPTION:
XS GIS Cut Line= 2
      3596731.71     10614714.29      3595824.55     10614675.23
#Sta/Elev= 30
  4446.4  465.99  4458.5  466.26  4508.6  465.62  4518.6  465.12  4538.6  464.91
  4548.6  464.18  4578.6  464.19  4608.7  463.15  4628.7  463.00  4648.7  462.15
  4668.7  462.37  4708.7  461.88  4718.8  461.20  4738.8  460.73  4928.9  459.91
  4979.0  458.65  4996.0  457.45  4998.8  456.95  5002.0  457.45  5009.0  457.91
  5019.0  459.53  5039.1  460.24  5069.1  460.44  5099.1  462.18  5159.2  463.02
  5199.2  464.02  5209.2  464.57  5299.3  466.26  5309.3  466.90  5354.4  467.24
#Mann=3,-1,0
  4446.4    0.08       0  4996.0    0.07       0  5002.0    0.08       0
Bank Sta=4996,5002
Exp/Cntr=0.3,0.1

Type RM Length L Ch R = 1,4699,444,444,444
BEGIN DESCRIPTION:
UNT 056 IN UKCR 9.0
END DESCRIPTION:
XS GIS Cut Line= 3
      3596699.57     10614610.17      3596274.28     10614395.26
      3595949.58     10614560.21
#Sta/Elev= 30
  4523.5  465.88  4590.7  464.23  4612.7  464.29  4639.7  463.93  4732.4  462.04
  4792.4  461.72  4849.5  459.71  4938.6  458.18  4955.3  456.37  4960.9  456.96
  4977.6  454.12  4989.2  453.93  4991.0  453.80  4993.8  453.30  4997.0  453.80
  5015.1  454.98  5044.3  456.19  5060.9  458.46  5088.8  458.25  5105.4  459.69
  5127.7  460.35  5133.3  459.99  5172.2  462.05  5200.0  461.01  5244.6  461.56
  5305.7  463.70  5328.0  463.74  5333.6  464.01  5341.7  465.38  5364.2  465.64
#Mann=7,-1,0
  4523.5    0.08       0  4612.7    0.05       0  4639.7    0.08       0
  4989.2    0.05       0  4991.0    0.04       0  4997.0    0.05       0
  5015.1    0.08       0
Bank Sta=4991,4997
Exp/Cntr=0.3,0.1

Type RM Length L Ch R = 1,4255,406,406,406
BEGIN DESCRIPTION:
UNT 056 IN UKCR 8.0
END DESCRIPTION:
XS GIS Cut Line= 3
      3596799.59     10614160.18      3596349.61     10613960.19
      3595749.61     10613860.19
#Sta/Elev= 30
  4529.6  462.58  4660.2  459.82  4758.7  459.39  4792.9  457.94  4810.7  458.28
  4862.7  456.92  4892.7  456.75  4946.8  456.79  4967.3  456.89  5004.7  452.42
  5007.4  451.92  5010.7  452.42  5019.3  453.84  5024.6  453.84  5049.9  456.46
  5081.7  455.76  5153.8  456.01  5171.6  456.81  5204.5  456.57  5237.5  457.93
  5265.3  458.06  5285.6  459.04  5455.4  461.68  5498.5  462.93  5518.8  462.67
  5536.5  463.31  5579.6  462.95  5597.4  463.72  5625.0  463.98  5630.3  463.90
#Mann=8,-1,0
  4529.6    0.08       0  4892.7     0.1       0  4946.8    0.08       0
  5004.7    0.07       0  5010.7    0.08       0  5081.7    0.05       0
  5455.4    0.08       0  5625.0    0.05       0
Bank Sta=5004.7,5010.7
Exp/Cntr=0.3,0.1

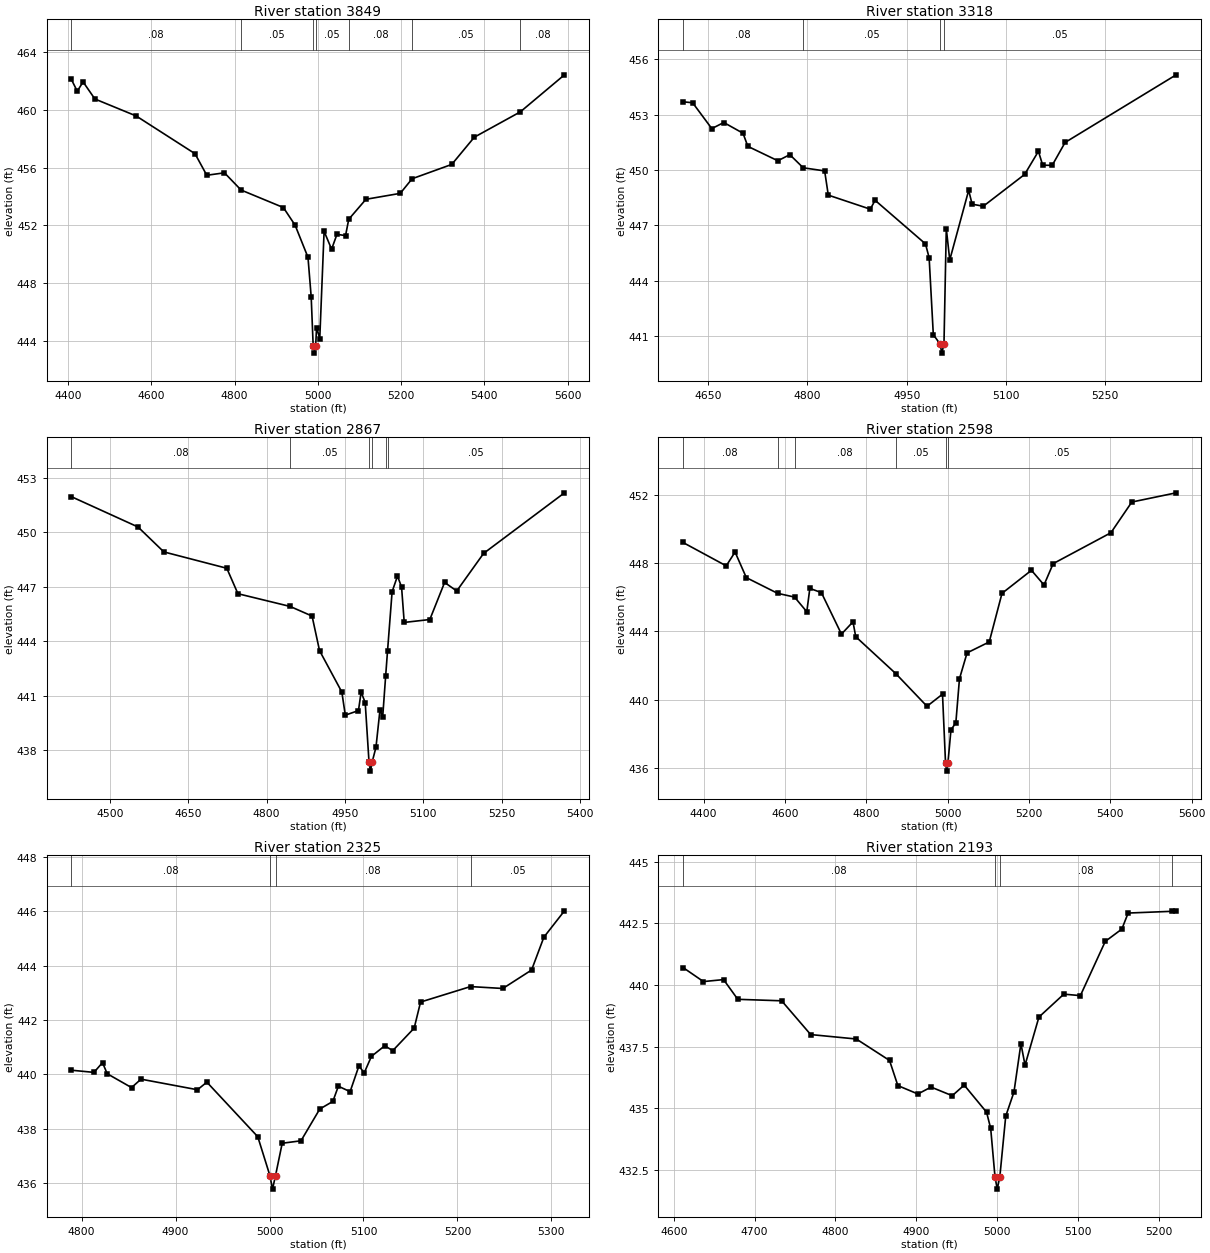
Type RM Length L Ch R = 1,3849,531,531,531
BEGIN DESCRIPTION:
UNT 056 IN UKCR 7.0
END DESCRIPTION:
XS GIS Cut Line= 3
      3596899.64     10614010.22      3596499.61     10613610.19
      3595899.60     10613760.19
#Sta/Elev= 30
  4408.0  462.10  4422.2  461.28  4436.3  461.92  4464.6  460.74  4563.6  459.57
  4705.0  456.96  4733.3  455.47  4775.7  455.64  4815.6  454.45  4917.2  453.24
  4945.4  452.02  4976.3  449.80  4984.0  447.07  4988.8  443.68  4991.5  443.18
  4994.8  443.68  4996.9  444.95  5004.6  444.19  5015.0  451.60  5033.0  450.36
  5045.9  451.39  5066.5  451.30  5074.2  452.43  5115.5  453.81  5197.9  454.22
  5226.4  455.23  5321.6  456.22  5375.7  458.10  5486.2  459.85  5592.2  462.41
#Mann=7,-1,0
  4408.0    0.08       0  4815.6    0.05       0  4988.8    0.04       0
  4994.8    0.05       0  5074.2    0.08       0  5226.4    0.05       0
  5486.2    0.08       0
Bank Sta=4988.8,4994.8
Exp/Cntr=0.3,0.1

Type RM Length L Ch R = 1,3318,451,451,451
BEGIN DESCRIPTION:
UNT 056 IN UKCR 6.0
END DESCRIPTION:
XS GIS Cut Line= 3
      3596749.57     10613310.17      3596399.61     10613160.19
      3596049.66     10613260.18
#Sta/Elev= 30
  4612.3  453.69  4626.8  453.64  4655.8  452.24  4673.9  452.57  4702.9  451.99
  4710.2  451.28  4755.5  450.50  4773.6  450.83  4793.8  450.12  4826.2  449.95
  4831.7  448.64  4895.1  447.88  4902.4  448.36  4978.5  446.00  4984.0  445.25
  4990.3  441.09  5000.4  440.59  5003.2  440.09  5006.4  440.59  5009.9  446.83
  5015.1  445.13  5043.7  448.90  5048.9  448.15  5065.8  448.04  5128.2  449.76
  5149.0  451.01  5155.5  450.26  5169.8  450.25  5189.3  451.49  5357.0  455.15
#Mann=4,-1,0
  4612.3    0.08       0  4793.8    0.05       0  5000.4    0.04       0
  5006.4    0.05       0
Bank Sta=5000.4,5006.4
Exp/Cntr=0.3,0.1

Type RM Length L Ch R = 1,2867,269,269,269
BEGIN DESCRIPTION:
UNT 056 IN UKCR 5.0
END DESCRIPTION:
XS GIS Cut Line= 3
      3596849.64     10613110.22      3596449.61     10612760.19
      3596049.57     10612860.20
#Sta/Elev= 30
  4426.1  451.95  4553.8  450.28  4603.2  448.91  4723.7  448.01  4745.0  446.61
  4844.9  445.91  4886.9  445.38  4901.2  443.48  4943.9  441.20  4950.5  439.93
  4975.7  440.18  4980.8  441.20  4988.6  440.62  4995.9  437.35  4998.6  436.85
  5001.9  437.35  5009.2  438.16  5016.9  440.22  5022.1  439.84  5027.8  442.10
  5031.4  443.48  5040.1  446.72  5050.4  447.58  5058.2  446.98  5063.3  445.03
  5112.3  445.19  5140.6  447.23  5163.8  446.76  5215.3  448.83  5370.0  452.16
#Mann=6,-1,0
  4426.1    0.08       0  4844.9    0.05       0  4995.9    0.04       0
  5001.9    0.05       0  5027.8    0.08       0  5031.4    0.05       0
Bank Sta=4995.9,5001.9
Exp/Cntr=0.3,0.1

Type RM Length L Ch R = 1,2598,273,273,273
BEGIN DESCRIPTION:
Mapping XS 1637e5bd
END DESCRIPTION:
XS GIS Cut Line= 4
      3597025.28     10612904.87      3596660.68     10612576.73
      3596353.39     10612482.98      3595963.65     10612576.52
#Sta/Elev= 30
  4349.3  449.21  4455.6  447.84  4477.3  448.65  4505.0  447.15  4581.9  446.23
  4623.6  446.01  4653.7  445.15  4661.2  446.52  4689.6  446.27  4738.9  443.84
  4767.3  444.56  4774.0  443.69  4872.3  441.53  4949.3  439.61  4987.4  440.32
  4994.8  436.31  4997.5  435.81  5000.8  436.31  5008.2  438.23  5020.2  438.64
  5029.1  441.22  5047.8  442.74  5102.3  443.38  5133.7  446.23  5206.1  447.58
  5237.0  446.72  5259.5  447.97  5401.5  449.78  5452.9  451.58  5561.9  452.12
#Mann=6,-1,0
  4349.3    0.08       0  4581.9     0.1       0  4623.6    0.08       0
  4872.3    0.05       0  4994.8    0.04       0  5000.8    0.05       0
Bank Sta=4994.8,5000.8
Exp/Cntr=0.3,0.1

Type RM Length L Ch R = 1,2325,132,132,132
BEGIN DESCRIPTION:
UNT 056 IN UKCR 4.0
END DESCRIPTION:
XS GIS Cut Line= 3
      3596883.62     10612357.52      3596605.81     10612340.16
      3596388.79     10612222.96
#Sta/Elev= 30
  4789.0  440.15  4813.1  440.07  4822.2  440.43  4827.2  440.02  4853.1  439.51
  4863.2  439.82  4923.3  439.43  4933.3  439.71  4987.5  437.70  5000.4  436.27
  5003.2  435.77  5006.4  436.27  5013.5  437.46  5033.5  437.55  5053.5  438.72
  5067.4  439.00  5073.3  439.56  5085.8  439.36  5095.2  440.31  5100.8  440.05
  5108.5  440.66  5122.7  441.05  5131.2  440.87  5154.0  441.70  5160.8  442.66
  5214.0  443.23  5248.4  443.16  5279.0  443.84  5292.1  445.05  5314.0  446.02
#Mann=4,-1,0
  4789.0    0.08       0  5000.4    0.07       0  5006.4    0.08       0
  5214.0    0.05       0
Bank Sta=5000.4,5006.4
Exp/Cntr=0.3,0.1

Type RM Length L Ch R = 1,2193,637,637,637
BEGIN DESCRIPTION:
UNT 056 IN UKCR 3.0
END DESCRIPTION:
XS GIS Cut Line= 2
      3597048.52     10612301.09      3596454.22     10612162.28
#Sta/Elev= 30
  4611.5  440.71  4636.8  440.14  4661.7  440.22  4679.3  439.42  4733.6  439.36
  4769.5  437.99  4826.0  437.81  4867.1  436.94  4877.4  435.92  4902.2  435.58
  4918.5  435.86  4944.7  435.51  4959.5  435.94  4987.2  434.84  4992.3  434.18
  4997.6  432.22  5000.4  431.72  5003.6  432.22  5010.9  434.68  5021.1  435.66
  5029.7  437.62  5034.8  436.75  5052.0  438.70  5082.8  439.63  5103.3  439.57
  5134.1  441.77  5154.6  442.27  5162.4  442.92  5216.4  442.99  5221.8  443.01
#Mann=4,-1,0
  4611.5    0.08       0  4997.6    0.07       0  5003.6    0.08       0
  5216.4    0.05       0
Bank Sta=4997.6,5003.6
Exp/Cntr=0.3,0.1

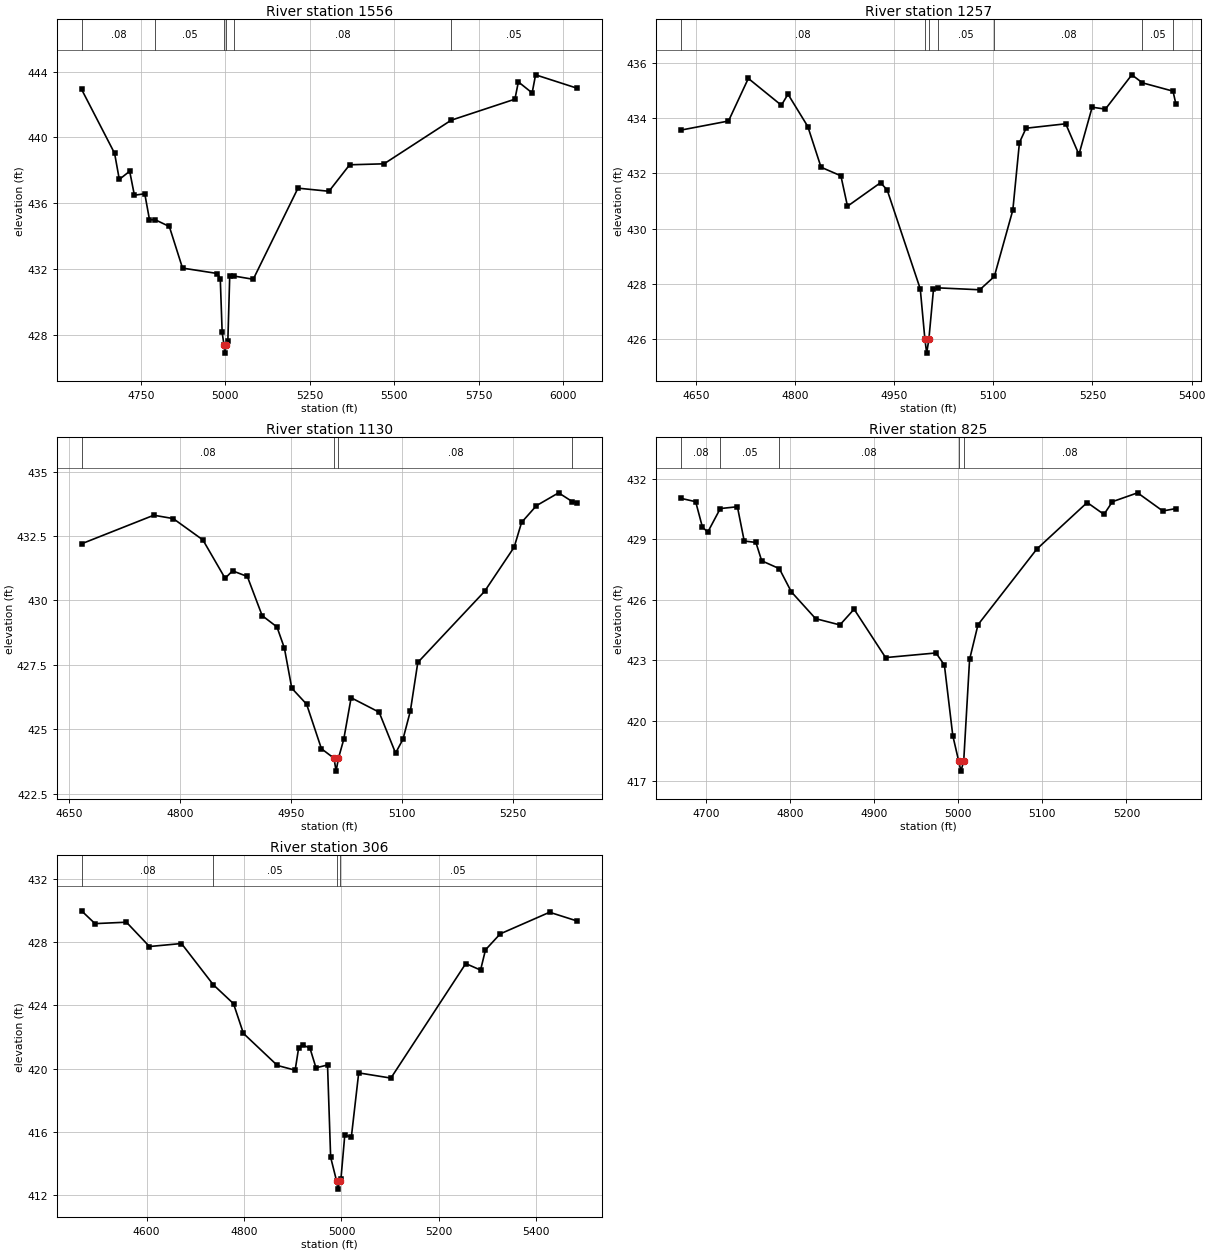
Type RM Length L Ch R = 1,1556,299,299,299
BEGIN DESCRIPTION:
UNT 056 IN UKCR 2.0
END DESCRIPTION:
XS GIS Cut Line= 3
      3597249.60     10612160.16      3597049.61     10611760.19
      3596049.60     10611960.19
#Sta/Elev= 30
  4574.4  442.93  4672.2  439.04  4686.2  437.45  4716.9  437.95  4730.9  436.49
  4761.6  436.58  4775.6  435.00  4792.3  435.00  4834.3  434.59  4873.4  432.06
  4976.9  431.73  4985.2  431.41  4990.8  428.15  4996.2  427.39  4999.0  426.89
  5002.2  427.39  5007.6  427.61  5013.2  431.57  5024.9  431.58  5082.8  431.38
  5215.3  436.92  5307.1  436.73  5368.3  438.34  5470.3  438.40  5669.0  441.05
  5857.8  442.33  5868.0  443.38  5908.8  442.71  5919.0  443.81  6041.4  443.00
#Mann=6,-1,0
  4574.4    0.08       0  4792.3    0.05       0  4996.2    0.04       0
  5002.2    0.05       0  5024.9    0.08       0  5669.0    0.05       0
Bank Sta=4996.2,5002.2
Exp/Cntr=0.3,0.1

Type RM Length L Ch R = 1,1257,127,127,127
BEGIN DESCRIPTION:
Mapping XS 63d52e2e
END DESCRIPTION:
XS GIS Cut Line= 2
      3597552.01     10611515.50      3596802.82     10611502.51
#Sta/Elev= 30
  4627.0  433.56  4699.4  433.89  4729.4  435.43  4779.4  434.46  4789.4  434.86
  4819.4  433.69  4839.4  432.22  4869.4  431.91  4879.4  430.81  4929.4  431.66
  4939.4  431.40  4989.5  427.82  4996.5  426.00  4999.2  425.50  5002.5  426.00
  5009.5  427.81  5015.8  427.86  5079.5  427.79  5101.5  428.27  5129.5  430.67
  5139.5  433.11  5149.5  433.63  5209.5  433.79  5229.5  432.68  5249.5  434.39
  5269.5  434.32  5309.5  435.56  5325.6  435.27  5371.8  434.97  5376.3  434.49
#Mann=7,-1,0
  4627.0    0.08       0  4996.5    0.07       0  5002.5    0.08       0
  5015.8    0.05       0  5101.5    0.08       0  5325.6    0.05       0
  5371.8    0.08       0
Bank Sta=4996.5,5002.5
Exp/Cntr=0.3,0.1

Type RM Length L Ch R = 1,1130,305,305,305
BEGIN DESCRIPTION:
Mapping XS 9320efe9
END DESCRIPTION:
XS GIS Cut Line= 2
      3597543.27     10611398.32      3596874.93     10611376.62
#Sta/Elev= 30
  4667.3  432.20  4764.8  433.31  4791.0  433.18  4831.1  432.35  4861.1  430.86
  4871.1  431.15  4891.1  430.93  4911.1  429.41  4931.1  428.97  4941.1  428.15
  4951.1  426.59  4971.1  425.97  4991.1  424.24  5008.1  423.87  5010.9  423.37
  5014.1  423.87  5021.2  424.60  5031.2  426.22  5069.0  425.66  5091.2  424.07
  5101.2  424.61  5111.2  425.71  5121.2  427.59  5211.3  430.35  5251.3  432.07
  5261.3  433.03  5281.3  433.68  5311.3  434.18  5329.7  433.84  5336.0  433.80
#Mann=4,-1,0
  4667.3    0.08       0  5008.1    0.07       0  5014.1    0.08       0
  5329.7    0.05       0
Bank Sta=5008.1,5014.1
Exp/Cntr=0.3,0.1

Type RM Length L Ch R = 1,825,519,519,519
BEGIN DESCRIPTION:
Mapping XS 976ed8f8
END DESCRIPTION:
XS GIS Cut Line= 3
      3597400.12     10611255.11      3597239.49     10611129.22
      3596853.90     10611124.89
#Sta/Elev= 30
  4669.3  431.04  4687.2  430.87  4695.3  429.60  4701.7  429.37  4716.5  430.53
  4736.9  430.62  4745.0  428.92  4758.9  428.85  4765.8  427.94  4786.8  427.55
  4801.1  426.40  4830.0  425.07  4858.9  424.76  4875.8  425.54  4913.3  423.14
  4973.3  423.37  4983.3  422.77  4993.3  419.27  5000.3  418.01  5003.0  417.51
  5006.3  418.01  5013.3  423.05  5023.3  424.77  5093.3  428.52  5153.3  430.83
  5173.3  430.24  5183.3  430.87  5213.3  431.31  5243.3  430.41  5259.0  430.53
#Mann=5,-1,0
  4669.3    0.08       0  4716.5    0.05       0  4786.8    0.08       0
  5000.3    0.07       0  5006.3    0.08       0
Bank Sta=5000.3,5006.3
Exp/Cntr=0.3,0.1

Type RM Length L Ch R = 1,306,0,0,0
BEGIN DESCRIPTION:
UNT 056 IN UKCR 1.0
END DESCRIPTION:
XS GIS Cut Line= 4
      3597430.47     10611207.39      3597361.02     10610816.72
      3597148.35     10610682.17      3596784.14     10610738.54
#Sta/Elev= 30
  4466.4  429.99  4494.0  429.18  4558.5  429.27  4605.8  427.73  4671.5  427.92
  4736.9  425.31  4778.4  424.11  4798.7  422.23  4868.4  420.20  4904.9  419.90
  4912.2  421.33  4920.1  421.51  4935.4  421.29  4947.7  420.05  4971.4  420.23
  4977.8  414.39  4990.1  412.87  4992.8  412.37  4996.1  412.87  4999.0  413.04
  5006.9  415.82  5020.2  415.64  5035.4  419.73  5101.5  419.40  5255.2  426.65
  5285.6  426.24  5295.7  427.52  5325.9  428.53  5427.3  429.90  5483.4  429.35
#Mann=4,-1,0
  4466.4    0.08       0  4736.9    0.05       0  4990.1    0.04       0
  4996.1    0.05       0
Bank Sta=4990.1,4996.1
Exp/Cntr=0.3,0.1

Chan Stop Cuts=-1