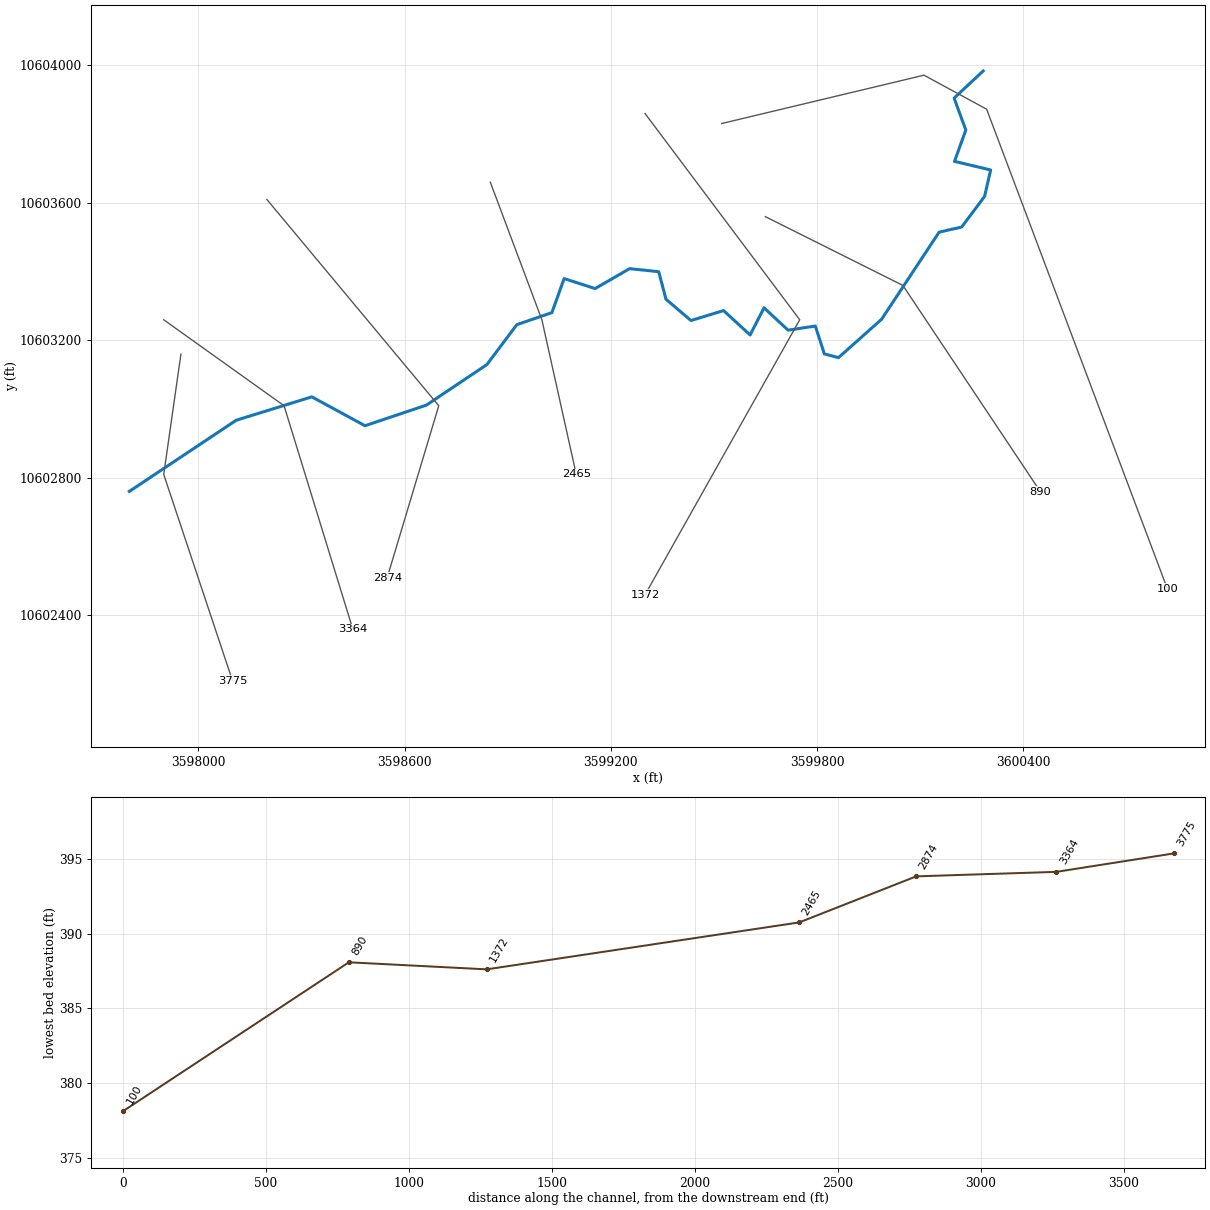
--- UNT 058 IN UKCR.prj (project) ---

Proj Title=UNT 058 IN UKCR Base Level Engineering
Current Plan=p01
Default Exp/Contr=0.3,0.1
English Units
Geom File=g01
Flow File=f01
Plan File=p01
BEGIN DESCRIPTION:
UNT 058 IN UKCR
END DESCRIPTION:

--- UNT 058 IN UKCR.p01 (plan) ---

Plan Title=Multiple Run
Short Identifier=Multiple
Geom File=g01
Flow File=f01
Subcritical Flow
K Sum by GR= 0
Std Step Tol= 0.01
Critical Tol= 0.01
Num of Std Step Trials= 20
Max Error Tol= 0.3
Flow Tol Ratio= 0.001
Split Flow NTrial= 30
Split Flow Tol= 0.02
Split Flow Ratio= 0.02
Log Output Level= 0
Friction Slope Method= 1
Unsteady Friction Slope Method= 2
Unsteady Bridges Friction Slope Method= 1
Parabolic Critical Depth
Global Vel Dist=  1 , 1 , 1
Global Log Level= 0
CheckData=True
Encroach Param= -1, 0, 0, 0
BEGIN DESCRIPTION:
Multiple Run
END DESCRIPTION:

--- UNT 058 IN UKCR.f01 (steady flow) ---

Flow Title=Multiple
Number of Profiles=7
Profile Names=10-year,25-year,50-year,1pct_min,100-year,1pct_plu,500-year
River Rch & RM= UNT 058 IN UKCR,Reach-1,3775
    1161    1605    1975    1775    2401    3247    3532
River Rch & RM= UNT 058 IN UKCR,Reach-1,3364
    1423    1986    2459    2221    3003    4061    4464
Boundary for River Rch & Prof#=UNT 058 IN UKCR,Reach-1,1
Up Type=0
Dn Type=3
Dn Slope=0.005
Boundary for River Rch & Prof#=UNT 058 IN UKCR,Reach-1,2
Up Type=0
Dn Type=3
Dn Slope=0.005
Boundary for River Rch & Prof#=UNT 058 IN UKCR,Reach-1,3
Up Type=0
Dn Type=3
Dn Slope=0.005
Boundary for River Rch & Prof#=UNT 058 IN UKCR,Reach-1,4
Up Type=0
Dn Type=3
Dn Slope=0.005
Boundary for River Rch & Prof#=UNT 058 IN UKCR,Reach-1,5
Up Type=0
Dn Type=3
Dn Slope=0.005
Boundary for River Rch & Prof#=UNT 058 IN UKCR,Reach-1,6
Up Type=0
Dn Type=3
Dn Slope=0.005
Boundary for River Rch & Prof#=UNT 058 IN UKCR,Reach-1,7
Up Type=0
Dn Type=3
Dn Slope=0.005

--- UNT 058 IN UKCR.g01 (geometry) ---

Geom Title=Existing Conditions

River Reach=UNT 058 IN UKCR,Reach-1
Reach XY= 30
      3597799.58     10602761.01      3598110.50     10602968.00
      3598330.50     10603036.00      3598485.00     10602952.00
      3598663.75     10603012.00      3598839.75     10603130.00
      3598926.75     10603246.00      3599028.75     10603281.00
      3599064.25     10603380.00      3599154.50     10603351.00
      3599255.00     10603409.00      3599339.50     10603400.00
      3599360.50     10603320.00      3599433.25     10603258.00
      3599528.00     10603287.00      3599605.25     10603216.00
      3599645.75     10603295.00      3599715.75     10603230.00
      3599795.00     10603242.00      3599821.25     10603161.00
      3599862.25     10603150.00      3599988.00     10603262.00
      3600155.00     10603515.00      3600220.75     10603530.00
      3600287.25     10603619.00      3600305.00     10603696.00
      3600199.75     10603721.00      3600232.75     10603812.00
      3600198.75     10603905.00      3600283.25     10603984.00

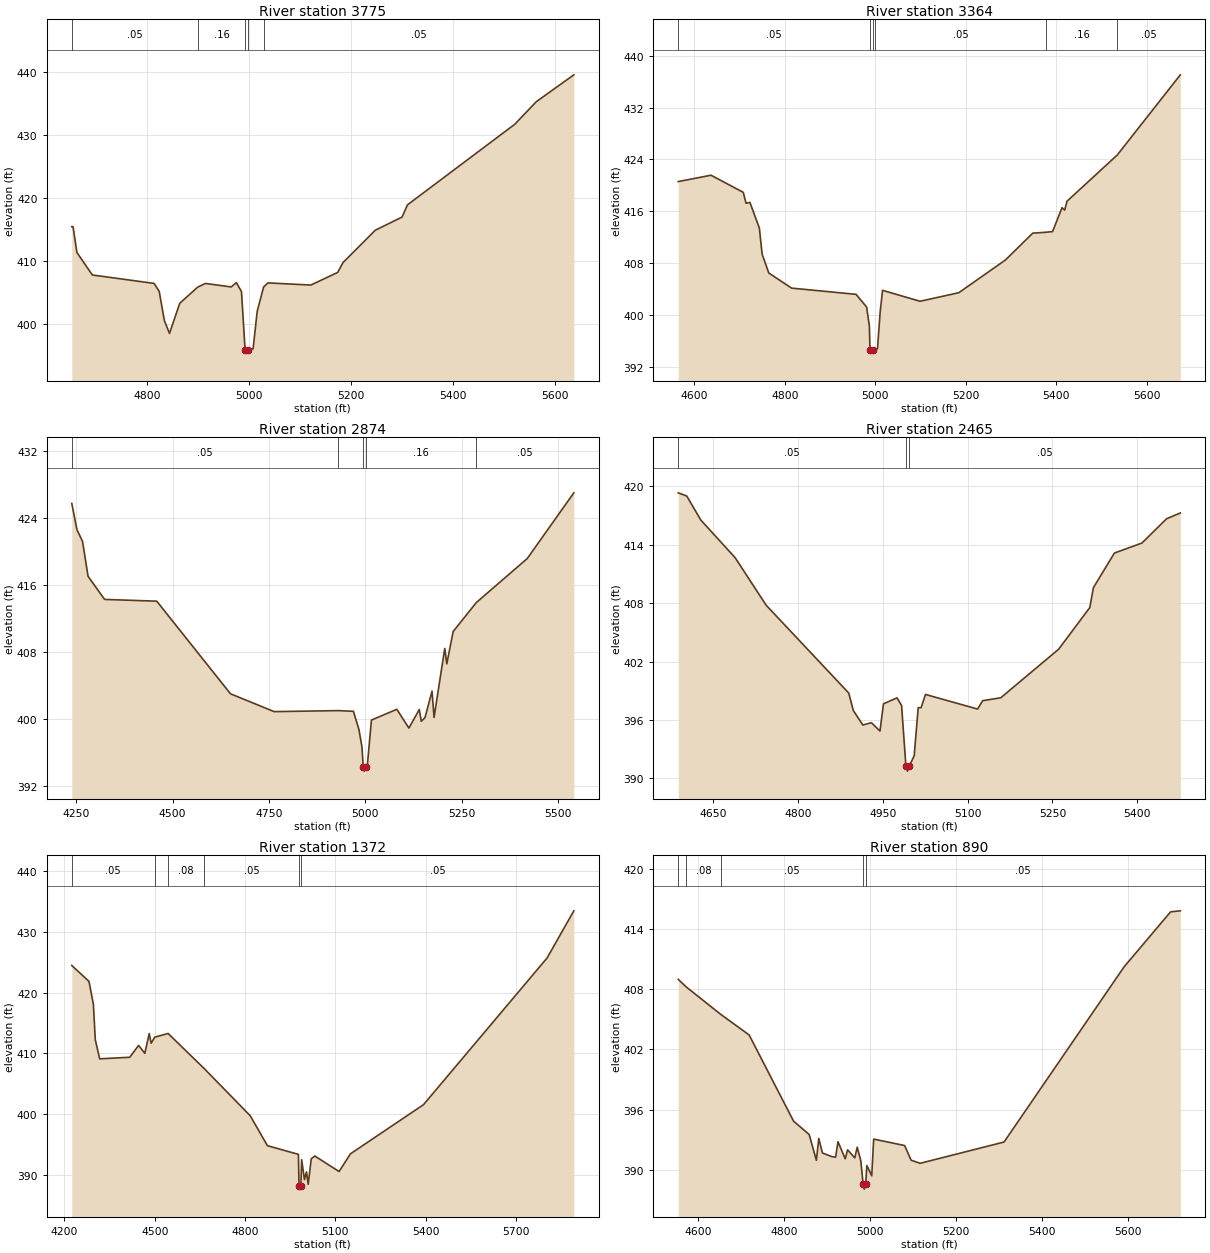
Type RM Length L Ch R = 1,3775,411,411,411
BEGIN DESCRIPTION:
UNT 058 IN UKCR 7.0
END DESCRIPTION:
XS GIS Cut Line= 3
      3597949.60     10603160.15      3597899.61     10602810.19
      3598099.62     10602210.16
#Sta/Elev= 30
  4651.5  415.42  4654.0  415.42  4661.6  411.32  4691.9  407.75  4813.1  406.41
  4823.2  405.15  4833.3  400.53  4843.4  398.47  4863.6  403.26  4898.8  405.82
  4914.1  406.40  4964.6  405.85  4974.7  406.54  4984.8  405.11  4991.9  395.84
  4994.7  395.34  4997.9  395.84  5007.6  396.02  5015.6  401.95  5028.2  405.83
  5036.6  406.49  5121.0  406.15  5173.7  408.15  5184.2  409.72  5247.5  414.85
  5300.2  416.95  5310.7  418.88  5521.5  431.68  5563.7  435.26  5637.5  439.53
#Mann=5,-1,0
  4651.5    0.05       0  4898.8    0.16       0  4991.9    0.07       0
  4997.9    0.16       0  5028.2    0.05       0
Bank Sta=4991.9,4997.9
Exp/Cntr=0.3,0.1

Type RM Length L Ch R = 1,3364,490,490,490
BEGIN DESCRIPTION:
UNT 058 IN UKCR 6.0
END DESCRIPTION:
XS GIS Cut Line= 3
      3597899.62     10603260.18      3598249.61     10603010.19
      3598449.62     10602360.16
#Sta/Elev= 30
  4564.3  420.58  4636.8  421.56  4708.1  418.92  4714.2  417.24  4722.8  417.37
  4743.7  413.40  4749.8  409.38  4764.6  406.47  4815.0  404.14  4957.5  403.18
  4980.9  401.22  4987.0  398.24  4988.3  394.61  4991.1  394.11  4994.3  394.61
  4999.7  394.67  5004.9  394.79  5010.7  400.37  5016.0  403.80  5099.0  402.11
  5184.7  403.43  5288.0  408.49  5348.2  412.62  5377.3  412.76  5392.0  412.86
  5412.9  416.55  5418.8  416.18  5424.0  417.55  5535.1  424.68  5674.5  437.05
#Mann=6,-1,0
  4564.3    0.05       0  4988.3    0.03       0  4994.3    0.05       0
  4999.7    0.05       0  5377.3    0.16       0  5535.1    0.05       0
Bank Sta=4988.3,4994.3
Exp/Cntr=0.3,0.1

Type RM Length L Ch R = 1,2874,409,409,409
BEGIN DESCRIPTION:
UNT 058 IN UKCR 5.0
END DESCRIPTION:
XS GIS Cut Line= 3
      3598199.64     10603610.15      3598699.61     10603010.19
      3598549.61     10602510.18
#Sta/Elev= 30
  4238.5  425.76  4252.1  422.60  4266.4  421.23  4280.8  417.06  4323.7  414.30
  4459.1  414.09  4650.4  403.04  4763.7  400.91  4930.5  401.03  4969.4  400.95
  4983.7  398.79  4991.5  396.72  4995.0  394.31  4997.7  393.81  5001.0  394.31
  5005.8  394.62  5016.2  399.90  5082.1  401.19  5113.4  398.95  5140.4  401.16
  5145.6  399.76  5155.2  400.19  5173.5  403.36  5178.7  400.21  5206.5  408.45
  5211.8  406.61  5228.3  410.47  5288.5  413.93  5420.6  419.18  5541.5  427.02
#Mann=5,-1,0
  4238.5    0.05       0  4930.5    0.16       0  4995.0    0.07       0
  5001.0    0.16       0  5288.5    0.05       0
Bank Sta=4995,5001
Exp/Cntr=0.3,0.1

Type RM Length L Ch R = 1,2465,1093,1093,1093
BEGIN DESCRIPTION:
UNT 058 IN UKCR 4.0
END DESCRIPTION:
XS GIS Cut Line= 3
      3598849.62     10603660.17      3598999.61     10603260.19
      3599099.62     10602810.15
#Sta/Elev= 30
  4588.0  419.34  4603.1  419.01  4628.0  416.54  4688.6  412.68  4743.7  407.78
  4889.7  398.76  4897.7  396.97  4914.6  395.48  4929.7  395.72  4944.9  394.86
  4951.1  397.66  4975.1  398.27  4983.1  397.49  4990.8  391.24  4993.6  390.74
  4996.8  391.24  5005.4  392.32  5012.5  397.26  5017.7  397.26  5025.4  398.62
  5117.6  397.12  5126.6  397.98  5158.6  398.28  5261.0  403.27  5316.1  407.55
  5322.5  409.60  5359.6  413.15  5408.3  414.18  5451.8  416.67  5476.2  417.27
#Mann=3,-1,0
  4588.0    0.05       0  4990.8    0.03       0  4996.8    0.05       0
Bank Sta=4990.8,4996.8
Exp/Cntr=0.3,0.1

Type RM Length L Ch R = 1,1372,482,482,482
BEGIN DESCRIPTION:
UNT 058 IN UKCR 3.0
END DESCRIPTION:
XS GIS Cut Line= 3
      3599299.60     10603860.20      3599749.61     10603260.19
      3599299.61     10602460.19
#Sta/Elev= 30
  4224.4  424.47  4281.7  421.83  4296.3  418.03  4302.5  412.24  4317.1  409.08
  4417.1  409.34  4446.3  411.29  4467.1  409.99  4481.7  413.24  4488.0  411.65
  4499.9  412.65  4544.4  413.26  4663.5  407.52  4817.1  399.71  4874.4  394.77
  4977.3  393.34  4979.4  388.11  4982.1  387.61  4985.4  388.11  4988.1  392.45
  4997.4  389.19  5004.1  390.45  5009.8  388.41  5020.0  392.61  5031.8  393.07
  5112.4  390.51  5150.0  393.42  5392.9  401.53  5803.4  425.70  5892.3  433.47
#Mann=6,-1,0
  4224.4    0.05       0  4499.9     0.1       0  4544.4    0.08       0
  4663.5    0.05       0  4979.4    0.03       0  4985.4    0.05       0
Bank Sta=4979.4,4985.4
Exp/Cntr=0.3,0.1

Type RM Length L Ch R = 1,890,790,790,790
BEGIN DESCRIPTION:
UNT 058 IN UKCR 2.0
END DESCRIPTION:
XS GIS Cut Line= 3
      3599649.57     10603560.21      3600049.61     10603360.19
      3600449.63     10602760.16
#Sta/Elev= 30
  4553.1  408.97  4571.7  408.21  4652.4  405.47  4718.1  403.43  4821.5  394.85
  4857.8  393.52  4874.6  390.95  4880.2  393.12  4888.6  391.68  4910.9  391.31
  4919.3  391.27  4924.9  392.80  4941.7  391.10  4947.2  391.99  4964.0  391.19
  4969.6  392.26  4978.0  390.89  4983.4  388.58  4986.1  388.08  4989.4  388.58
  4992.0  390.43  5003.4  389.41  5007.9  393.06  5080.0  392.42  5095.0  390.96
  5116.0  390.65  5311.3  392.77  5590.8  410.22  5698.9  415.69  5721.5  415.79
#Mann=5,-1,0
  4553.1     0.1       0  4571.7    0.08       0  4652.4    0.05       0
  4983.4    0.03       0  4989.4    0.05       0
Bank Sta=4983.4,4989.4
Exp/Cntr=0.3,0.1

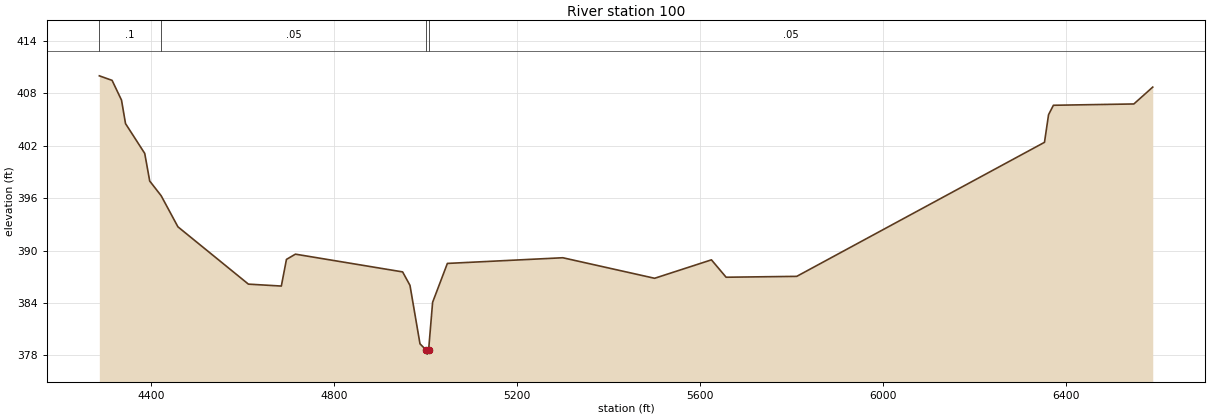
Type RM Length L Ch R = 1,100,0,0,0
BEGIN DESCRIPTION:
UNT 058 IN UKCR 1.0
END DESCRIPTION:
XS GIS Cut Line= 4
      3599522.45     10603831.03      3600111.02     10603971.67
      3600293.31     10603872.71      3600819.34     10602476.90
#Sta/Elev= 30
  4286.1  410.00  4314.0  409.48  4334.6  407.22  4343.4  404.53  4385.4  401.12
  4396.3  397.96  4421.3  396.28  4458.0  392.72  4612.2  386.16  4684.2  385.94
  4695.4  388.99  4715.0  389.59  4949.5  387.56  4965.6  386.02  4987.5  379.33
  5000.4  378.65  5003.2  378.15  5006.4  378.65  5015.1  384.08  5047.4  388.53
  5299.9  389.18  5500.7  386.83  5625.0  388.94  5657.1  386.95  5811.6  387.05
  6353.5  402.39  6362.4  405.55  6373.0  406.63  6549.0  406.78  6590.3  408.71
#Mann=4,-1,0
  4286.1     0.1       0  4421.3    0.05       0  5000.4    0.03       0
  5006.4    0.05       0
Bank Sta=5000.4,5006.4
Exp/Cntr=0.3,0.1

Chan Stop Cuts=-1