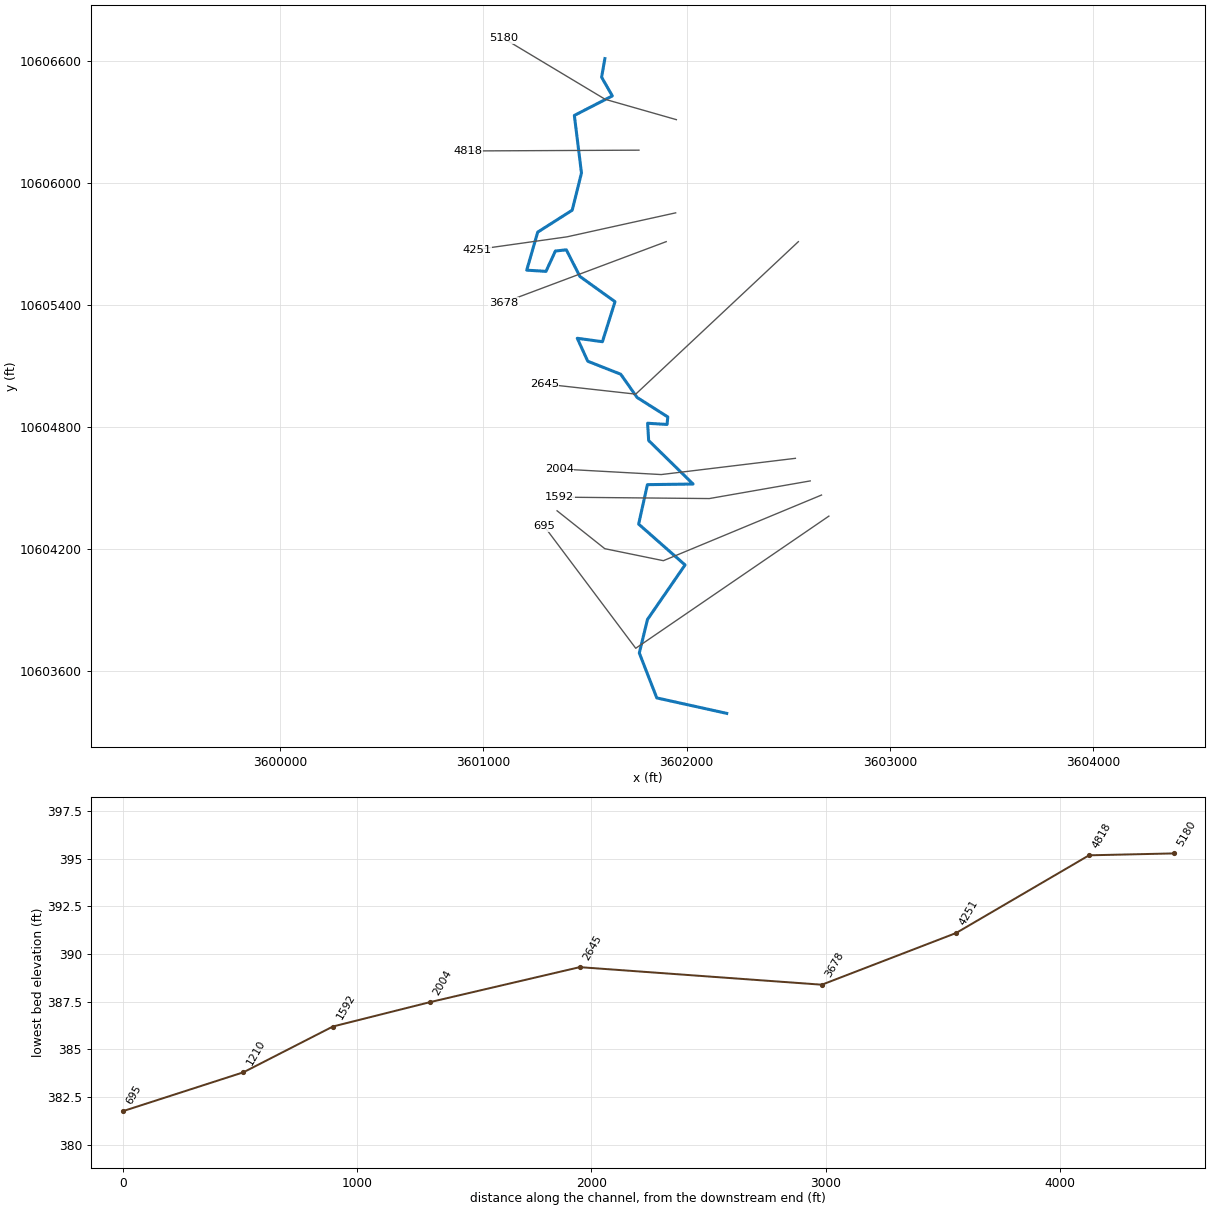
--- UNT 062 IN UKCR.prj (project) ---

Proj Title=UNT 062 IN UKCR Base Level Engineering
Current Plan=p01
Default Exp/Contr=0.3,0.1
English Units
Geom File=g01
Flow File=f01
Plan File=p01
Y Axis Title=Elevation
X Axis Title(PF)=Main Channel Distance
X Axis Title(XS)=Station
BEGIN DESCRIPTION:
UNT 062 IN UKCR
END DESCRIPTION:
DSS Export Rating Curves= 0
DSS Export Rating Curve Sorted= 0
DSS Export Volume Flow Curves= 0
DXF OffsetX= 0
DXF OffsetY= 0
DXF ScaleX= 1
DXF ScaleY= 10

--- UNT 062 IN UKCR.p01 (plan) ---

Plan Title=Multiple Run
Short Identifier=Multiple
Geom File=g01
Flow File=f01
Subcritical Flow
K Sum by GR= 0
Std Step Tol= 0.01
Critical Tol= 0.01
Num of Std Step Trials= 20
Max Error Tol= 0.3
Flow Tol Ratio= 0.001
Split Flow NTrial= 30
Split Flow Tol= 0.02
Split Flow Ratio= 0.02
Log Output Level= 0
Friction Slope Method= 1
Unsteady Friction Slope Method= 2
Unsteady Bridges Friction Slope Method= 1
Parabolic Critical Depth
Global Vel Dist=  1 , 1 , 1
Global Log Level= 0
CheckData=True
Encroach Param= -1, 0, 0, 0
BEGIN DESCRIPTION:
Multiple Run
END DESCRIPTION:

--- UNT 062 IN UKCR.f01 (steady flow) ---

Flow Title=Multiple
Number of Profiles=7
Profile Names=10-year,25-year,50-year,1pct_min,100-year,1pct_plu,500-year
River Rch & RM= UNT 062 IN UKCR,Reach-1,5180
    1038    1412    1719    1526    2064    2791    2963
Boundary for River Rch & Prof#=UNT 062 IN UKCR,Reach-1,1
Up Type=0
Dn Type=3
Dn Slope=0.005
Boundary for River Rch & Prof#=UNT 062 IN UKCR,Reach-1,2
Up Type=0
Dn Type=3
Dn Slope=0.005
Boundary for River Rch & Prof#=UNT 062 IN UKCR,Reach-1,3
Up Type=0
Dn Type=3
Dn Slope=0.005
Boundary for River Rch & Prof#=UNT 062 IN UKCR,Reach-1,4
Up Type=0
Dn Type=3
Dn Slope=0.005
Boundary for River Rch & Prof#=UNT 062 IN UKCR,Reach-1,5
Up Type=0
Dn Type=3
Dn Slope=0.005
Boundary for River Rch & Prof#=UNT 062 IN UKCR,Reach-1,6
Up Type=0
Dn Type=3
Dn Slope=0.005
Boundary for River Rch & Prof#=UNT 062 IN UKCR,Reach-1,7
Up Type=0
Dn Type=3
Dn Slope=0.005

--- UNT 062 IN UKCR.g01 (geometry) ---

Geom Title=Existing Conditions

River Reach=UNT 062 IN UKCR,Reach-1
Reach XY= 30
      3601597.91     10606610.61      3601581.75     10606519.00
      3601634.50     10606427.00      3601447.75     10606331.00
      3601482.75     10606048.00      3601437.25     10605865.00
      3601267.50     10605757.00      3601213.50     10605570.00
      3601308.25     10605564.00      3601354.50     10605664.00
      3601408.25     10605670.00      3601475.00     10605539.00
      3601647.75     10605415.00      3601585.75     10605218.00
      3601462.00     10605235.00      3601513.75     10605122.00
      3601676.00     10605058.00      3601756.25     10604944.00
      3601907.25     10604848.00      3601903.75     10604811.00
      3601808.00     10604817.00      3601813.25     10604732.00
      3602031.75     10604518.00      3601807.00     10604515.00
      3601764.00     10604321.00      3601992.25     10604120.00
      3601807.50     10603852.00      3601767.25     10603687.00
      3601853.25     10603466.00      3602197.25     10603390.00

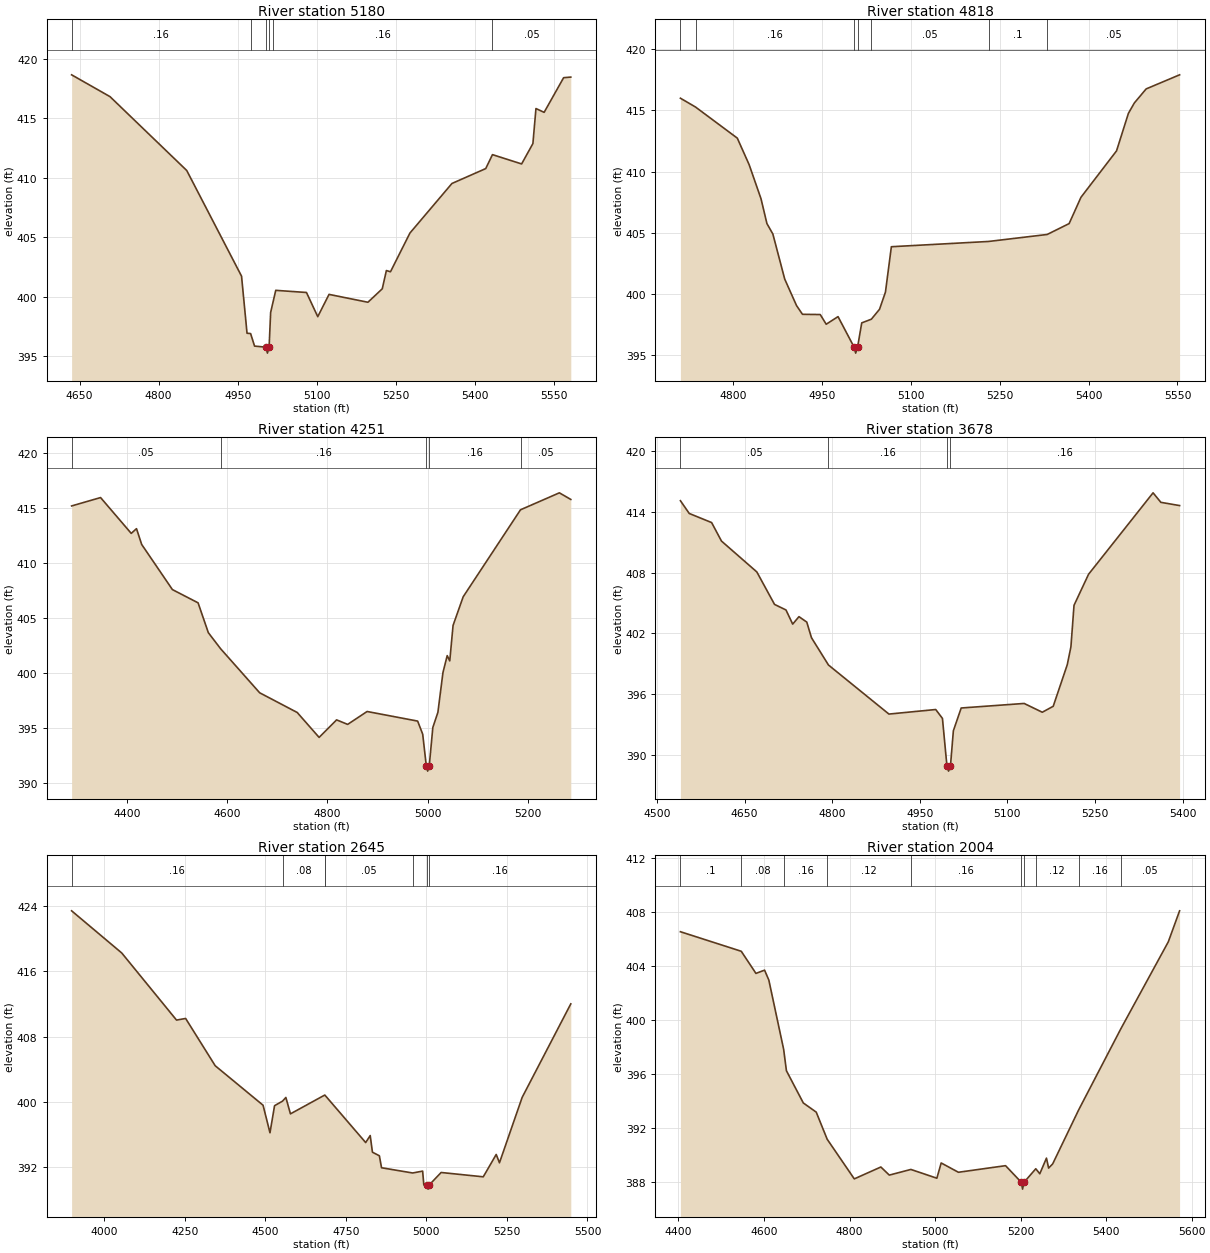
Type RM Length L Ch R = 1,5180,362,362,362
BEGIN DESCRIPTION:
UNT 062 IN UKCR 9.0
END DESCRIPTION:
XS GIS Cut Line= 3
      3601949.58     10606310.20      3601599.61     10606410.19
      3601099.58     10606710.20
#Sta/Elev= 30
  4634.9  418.63  4707.7  416.80  4853.3  410.60  4957.3  401.73  4967.7  396.94
  4974.5  396.91  4982.0  395.86  5003.6  395.77  5006.4  395.27  5009.6  395.77
  5012.5  398.68  5016.6  399.47  5022.2  400.54  5080.5  400.36  5101.9  398.33
  5123.3  400.20  5197.1  399.54  5224.3  400.67  5232.1  402.20  5239.9  402.10
  5276.8  405.35  5356.5  409.51  5420.6  410.76  5433.4  411.93  5488.7  411.15
  5510.1  412.86  5515.9  415.80  5531.4  415.48  5568.4  418.39  5582.0  418.44
#Mann=6,-1,0
  4634.9    0.16       0  4974.5    0.12       0  5003.6    0.07       0
  5009.6    0.12       0  5016.6    0.16       0  5433.4    0.05       0
Bank Sta=5003.6,5009.6
Exp/Cntr=0.3,0.1

Type RM Length L Ch R = 1,4818,567,567,567
BEGIN DESCRIPTION:
UNT 062 IN UKCR 8.0
END DESCRIPTION:
XS GIS Cut Line= 2
      3601765.63     10606160.18      3600923.24     10606156.28
#Sta/Elev= 30
  4711.2  415.99  4736.7  415.27  4807.2  412.73  4827.2  410.56  4847.2  407.78
  4857.2  405.75  4867.2  404.90  4887.2  401.22  4907.2  399.05  4917.2  398.34
  4947.2  398.32  4957.2  397.53  4977.2  398.15  5004.2  395.67  5007.0  395.17
  5010.2  395.67  5017.2  397.64  5033.4  397.94  5047.2  398.75  5057.2  400.15
  5067.2  403.86  5231.2  404.29  5330.1  404.86  5367.2  405.75  5387.2  407.90
  5447.2  411.69  5467.2  414.75  5477.2  415.60  5497.2  416.75  5553.6  417.90
#Mann=7,-1,0
  4711.2    0.05       0  4736.7    0.16       0  5004.2    0.07       0
  5010.2    0.16       0  5033.4    0.05       0  5231.2     0.1       0
  5330.1    0.05       0
Bank Sta=5004.2,5010.2
Exp/Cntr=0.3,0.1

Type RM Length L Ch R = 1,4251,573,573,573
BEGIN DESCRIPTION:
UNT 062 IN UKCR 7.0
END DESCRIPTION:
XS GIS Cut Line= 3
      3601946.07     10605851.87      3601411.37     10605733.82
      3600966.92     10605671.32
#Sta/Elev= 30
  4289.5  415.16  4347.3  415.92  4408.5  412.67  4419.0  413.10  4429.3  411.67
  4490.7  407.57  4541.9  406.37  4562.4  403.66  4586.8  402.21  4664.8  398.21
  4739.8  396.42  4783.5  394.16  4818.4  395.75  4840.5  395.34  4879.3  396.51
  4980.2  395.64  4990.3  394.45  4997.4  391.60  5000.2  391.10  5003.4  391.60
  5010.5  395.06  5020.6  396.43  5030.7  400.04  5039.2  401.58  5044.3  401.10
  5050.9  404.32  5071.1  406.92  5185.5  414.81  5263.1  416.35  5285.9  415.75
#Mann=5,-1,0
  4289.5    0.05       0  4586.8    0.16       0  4997.4    0.07       0
  5003.4    0.16       0  5185.5    0.05       0
Bank Sta=4997.4,5003.4
Exp/Cntr=0.3,0.1

Type RM Length L Ch R = 1,3678,1033,1033,1033
BEGIN DESCRIPTION:
UNT 062 IN UKCR 6.0
END DESCRIPTION:
XS GIS Cut Line= 3
      3601899.59     10605710.18      3601499.61     10605560.19
      3601099.59     10605410.18
#Sta/Elev= 30
  4540.3  415.12  4555.4  413.86  4593.7  412.96  4610.6  411.13  4671.1  408.08
  4701.4  404.87  4721.0  404.32  4732.5  402.92  4743.2  403.66  4756.6  403.12
  4764.6  401.58  4793.7  398.88  4897.2  394.03  4977.3  394.48  4988.8  393.60
  4996.5  388.89  4999.3  388.39  5002.5  388.89  5007.5  392.38  5020.9  394.63
  5128.6  395.08  5159.7  394.21  5178.4  394.80  5202.4  398.90  5208.7  400.68
  5214.0  404.78  5238.9  407.85  5349.3  415.90  5362.6  414.96  5394.7  414.64
#Mann=4,-1,0
  4540.3    0.05       0  4793.7    0.16       0  4996.5    0.07       0
  5002.5    0.16       0
Bank Sta=4996.5,5002.5
Exp/Cntr=0.3,0.1

Type RM Length L Ch R = 1,2645,641,641,641
BEGIN DESCRIPTION:
UNT 062 IN UKCR 5.0
END DESCRIPTION:
XS GIS Cut Line= 3
      3602549.61     10605710.19      3601749.61     10604960.19
      3601299.57     10605010.19
#Sta/Elev= 30
  3898.8  423.44  4054.4  418.27  4224.4  410.04  4252.7  410.24  4344.5  404.44
  4493.0  399.60  4514.5  396.22  4528.7  399.54  4553.4  400.10  4563.8  400.55
  4578.0  398.54  4684.2  400.84  4684.7  400.85  4811.5  395.02  4825.6  395.88
  4832.5  393.84  4854.0  393.40  4860.8  391.93  4957.4  391.29  4988.3  391.52
  4992.0  389.83  5002.5  389.81  5005.2  389.31  5008.5  389.81  5045.7  391.35
  5176.5  390.82  5216.7  393.56  5226.8  392.54  5297.2  400.56  5448.2  412.03
#Mann=7,-1,0
  3898.8    0.16       0  4553.4    0.08       0  4684.2     0.1       0
  4684.7    0.05       0  4957.4    0.16       0  5002.5    0.07       0
  5008.5    0.16       0
Bank Sta=5002.5,5008.5
Exp/Cntr=0.3,0.1

Type RM Length L Ch R = 1,2004,412,412,412
BEGIN DESCRIPTION:
UNT 062 IN UKCR 4.0
END DESCRIPTION:
XS GIS Cut Line= 3
      3602534.95     10604644.46      3601875.26     10604564.61
      3601373.23     10604592.31
#Sta/Elev= 30
  4404.6  406.56  4546.9  405.11  4581.2  403.47  4601.4  403.71  4611.4  402.97
  4646.0  397.84  4652.5  396.25  4692.0  393.86  4722.2  393.18  4747.8  391.17
  4811.2  388.23  4873.3  389.11  4893.1  388.51  4943.5  388.93  5004.3  388.28
  5014.4  389.41  5054.7  388.72  5164.9  389.21  5202.0  387.97  5204.7  387.47
  5208.0  387.97  5235.6  388.98  5245.0  388.61  5260.6  389.77  5265.6  389.03
  5275.1  389.34  5335.8  393.34  5434.5  399.36  5545.5  405.81  5571.9  408.11
#Mann=10,-1,0
  4404.6     0.1       0  4546.9    0.08       0  4646.0    0.16       0
  4747.8    0.12       0  4943.5    0.16       0  5202.0    0.07       0
  5208.0    0.16       0  5235.6    0.12       0  5335.8    0.16       0
  5434.5    0.05       0
Bank Sta=5202,5208
Exp/Cntr=0.3,0.1

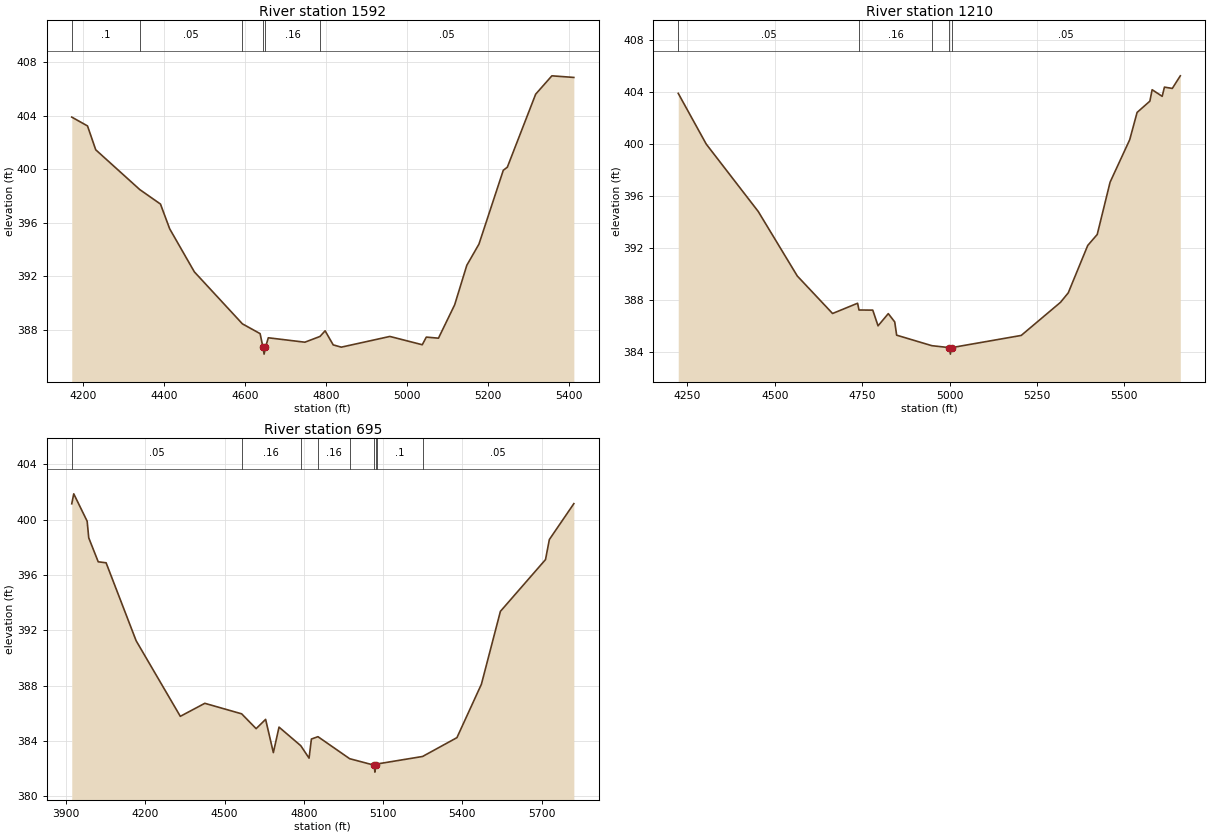
Type RM Length L Ch R = 1,1592,382,382,382
BEGIN DESCRIPTION:
UNT 062 IN UKCR 3.0
END DESCRIPTION:
XS GIS Cut Line= 3
      3602607.90     10604533.36      3602111.37     10604446.55
      3601375.27     10604453.50
#Sta/Elev= 30
  4171.9  403.89  4210.8  403.23  4231.1  401.45  4339.9  398.48  4391.0  397.40
  4413.8  395.55  4474.7  392.34  4593.4  388.46  4637.1  387.73  4644.3  386.70
  4647.0  386.20  4650.3  386.70  4657.4  387.42  4747.7  387.09  4785.1  387.52
  4797.7  387.94  4817.7  386.89  4837.7  386.72  4957.7  387.52  5037.7  386.90
  5047.7  387.47  5077.7  387.39  5117.7  389.88  5147.7  392.83  5177.7  394.41
  5237.8  399.92  5247.8  400.15  5317.8  405.60  5357.8  406.97  5412.1  406.85
#Mann=6,-1,0
  4171.9     0.1       0  4339.9    0.05       0  4593.4    0.16       0
  4644.3    0.03       0  4650.3    0.16       0  4785.1    0.05       0
Bank Sta=4644.3,4650.3
Exp/Cntr=0.3,0.1

Type RM Length L Ch R = 1,1210,515,515,515
BEGIN DESCRIPTION:
UNT 062 IN UKCR 2.0
END DESCRIPTION:
XS GIS Cut Line= 4
      3602663.45     10604463.91      3601885.67     10604141.00
      3601597.48     10604200.02      3601362.80     10604386.39
#Sta/Elev= 30
  4224.1  403.89  4304.2  399.98  4452.9  394.79  4564.6  389.82  4665.5  386.93
  4737.1  387.72  4741.1  387.20  4780.5  387.19  4795.6  385.98  4824.9  386.92
  4843.3  386.28  4848.8  385.26  4949.5  384.45  4999.8  384.30  5002.5  383.80
  5005.8  384.30  5205.1  385.24  5317.4  387.79  5339.6  388.52  5395.3  392.17
  5422.5  393.02  5459.3  397.05  5515.4  400.32  5536.5  402.42  5573.1  403.29
  5579.5  404.17  5608.3  403.66  5614.7  404.37  5637.2  404.27  5660.1  405.24
#Mann=5,-1,0
  4224.1    0.05       0  4741.1    0.16       0  4949.5    0.05       0
  4999.8    0.03       0  5005.8    0.05       0
Bank Sta=4999.8,5005.8
Exp/Cntr=0.3,0.1

Type RM Length L Ch R = 1,695,0,0,0
BEGIN DESCRIPTION:
UNT 062 IN UKCR 1.0
END DESCRIPTION:
XS GIS Cut Line= 3
      3602699.61     10604360.19      3601749.61     10603710.19
      3601299.60     10604310.20
#Sta/Elev= 30
  3921.0  401.14  3928.5  401.86  3979.3  399.88  3985.3  398.68  4021.2  396.95
  4051.0  396.88  4164.7  391.25  4332.0  385.79  4424.8  386.73  4564.3  385.97
  4619.1  384.90  4655.0  385.57  4684.3  383.17  4705.8  385.01  4788.0  383.67
  4819.5  382.77  4828.4  384.15  4853.2  384.32  4973.2  382.73  5066.1  382.26
  5068.8  381.76  5072.1  382.26  5077.3  382.35  5249.3  382.89  5379.4  384.25
  5472.1  388.11  5544.0  393.37  5714.8  397.11  5729.4  398.56  5822.1  401.15
#Mann=9,-1,0
  3921.0    0.05       0  4564.3    0.16       0  4788.0    0.12       0
  4853.2    0.16       0  4973.2    0.05       0  5066.1    0.03       0
  5072.1    0.05       0  5077.3     0.1       0  5249.3    0.05       0
Bank Sta=5066.1,5072.1
Exp/Cntr=0.3,0.1

Chan Stop Cuts=-1