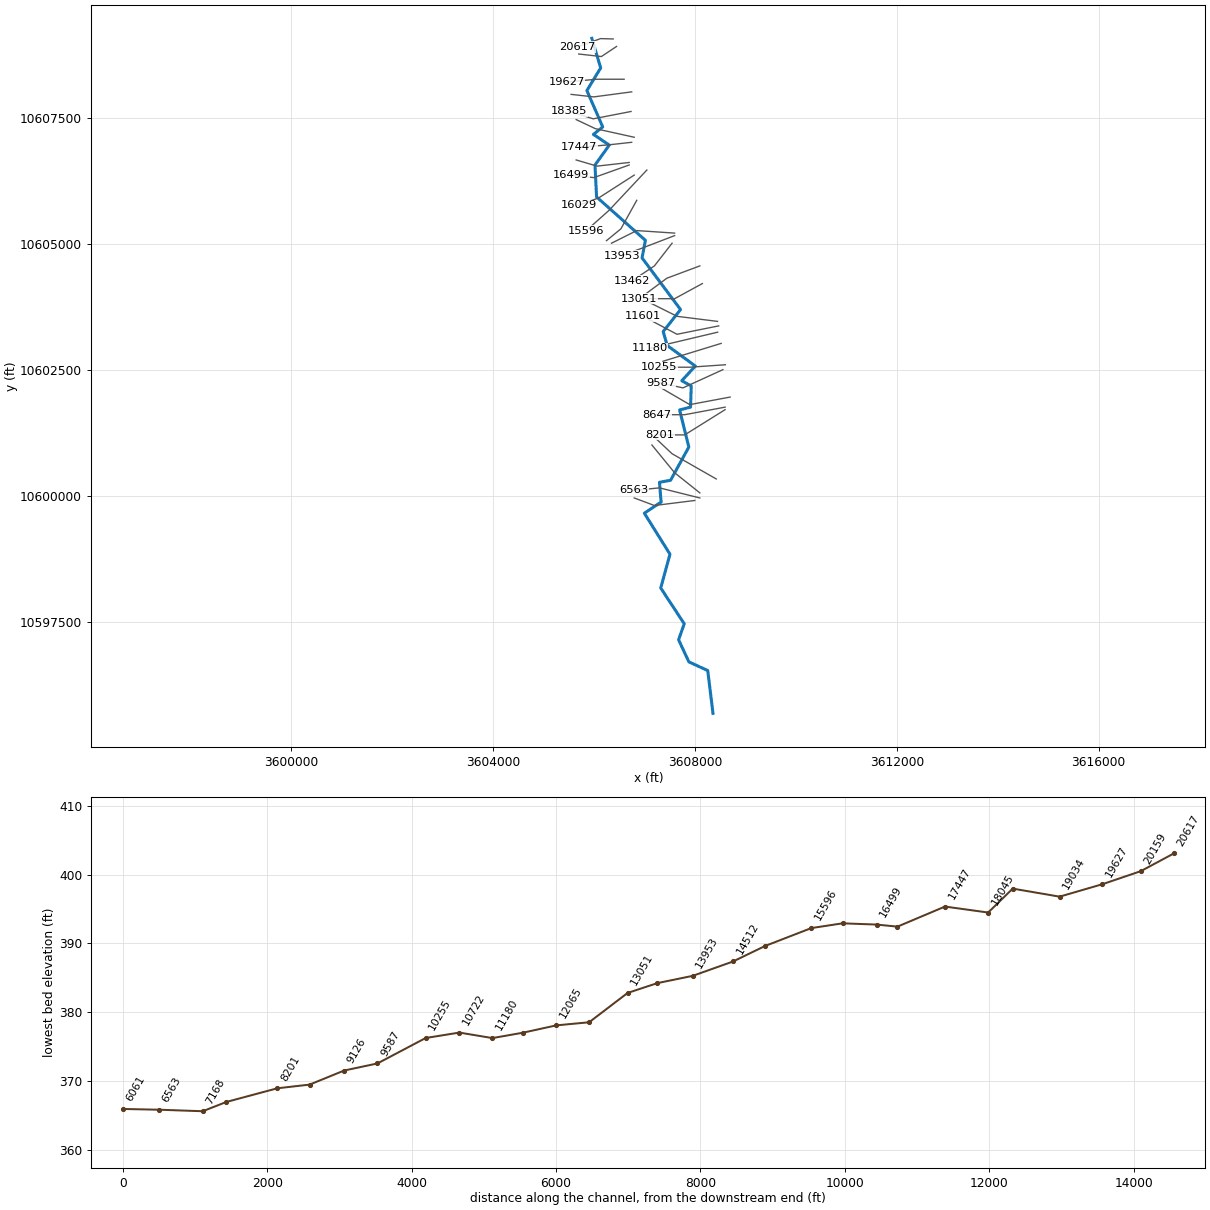
--- UNT 066 IN UKCR.prj (project) ---

Proj Title=UNT 066 IN UKCR Base Level Engineering
Current Plan=p01
Default Exp/Contr=0.3,0.1
English Units
Geom File=g01
Flow File=f01
Plan File=p01
BEGIN DESCRIPTION:
UNT 066 IN UKCR
END DESCRIPTION:

--- UNT 066 IN UKCR.p01 (plan) ---

Plan Title=Multiple Run
Short Identifier=Multiple
Geom File=g01
Flow File=f01
Subcritical Flow
K Sum by GR= 0
Std Step Tol= 0.01
Critical Tol= 0.01
Num of Std Step Trials= 20
Max Error Tol= 0.3
Flow Tol Ratio= 0.001
Split Flow NTrial= 30
Split Flow Tol= 0.02
Split Flow Ratio= 0.02
Log Output Level= 0
Friction Slope Method= 1
Unsteady Friction Slope Method= 2
Unsteady Bridges Friction Slope Method= 1
Parabolic Critical Depth
Global Vel Dist=  1 , 1 , 1
Global Log Level= 0
CheckData=True
Encroach Param= -1, 0, 0, 0
BEGIN DESCRIPTION:
Multiple Run
END DESCRIPTION:

--- UNT 066 IN UKCR.f01 (steady flow) ---

Flow Title=Multiple
Number of Profiles=7
Profile Names=10-year,25-year,50-year,1pct_min,100-year,1pct_plu,500-year
River Rch & RM= UNT 066 IN UKCR,Reach-1,20617
    1158    1601    1970    1770    2394    3237    3519
River Rch & RM= UNT 066 IN UKCR,Reach-1,19627
    1569    2186    2703    2434    3292    4452    4868
River Rch & RM= UNT 066 IN UKCR,Reach-1,6563
    1726    2417    2998    2709    3663    4954    5450
River Rch & RM= UNT 066 IN UKCR,Reach-1,4911
    1855    2606    3239    2931    3964    5360    5918
Boundary for River Rch & Prof#=UNT 066 IN UKCR,Reach-1,1
Up Type=0
Dn Type=3
Dn Slope=0.005
Boundary for River Rch & Prof#=UNT 066 IN UKCR,Reach-1,2
Up Type=0
Dn Type=3
Dn Slope=0.005
Boundary for River Rch & Prof#=UNT 066 IN UKCR,Reach-1,3
Up Type=0
Dn Type=3
Dn Slope=0.005
Boundary for River Rch & Prof#=UNT 066 IN UKCR,Reach-1,4
Up Type=0
Dn Type=3
Dn Slope=0.005
Boundary for River Rch & Prof#=UNT 066 IN UKCR,Reach-1,5
Up Type=0
Dn Type=3
Dn Slope=0.005
Boundary for River Rch & Prof#=UNT 066 IN UKCR,Reach-1,6
Up Type=0
Dn Type=3
Dn Slope=0.005
Boundary for River Rch & Prof#=UNT 066 IN UKCR,Reach-1,7
Up Type=0
Dn Type=3
Dn Slope=0.005

--- UNT 066 IN UKCR.g01 (geometry) ---

Geom Title=Existing Conditions

River Reach=UNT 066 IN UKCR,Reach-1
Reach XY= 30
      3605959.50     10609071.00      3606135.25     10608485.00
      3605862.00     10608036.00      3606175.75     10607315.00
      3605990.75     10607167.00      3606306.00     10606955.00
      3606022.00     10606559.00      3606053.75     10605927.00
      3607020.50     10605067.00      3606955.00     10604718.00
      3607717.00     10603695.00      3607374.00     10603259.00
      3607452.75     10602982.00      3608010.25     10602575.00
      3607741.50     10602284.00      3607928.75     10602180.00
      3607915.75     10601761.00      3607698.75     10601705.00
      3607881.25     10600969.00      3607519.50     10600310.00
      3607299.75     10600271.00      3607331.75     10599878.00
      3606999.75     10599658.00      3607508.00     10598845.00
      3607324.75     10598175.00      3607790.00     10597467.00
      3607678.75     10597149.00      3607882.00     10596711.00
      3608256.00     10596539.00      3608359.50     10595690.00

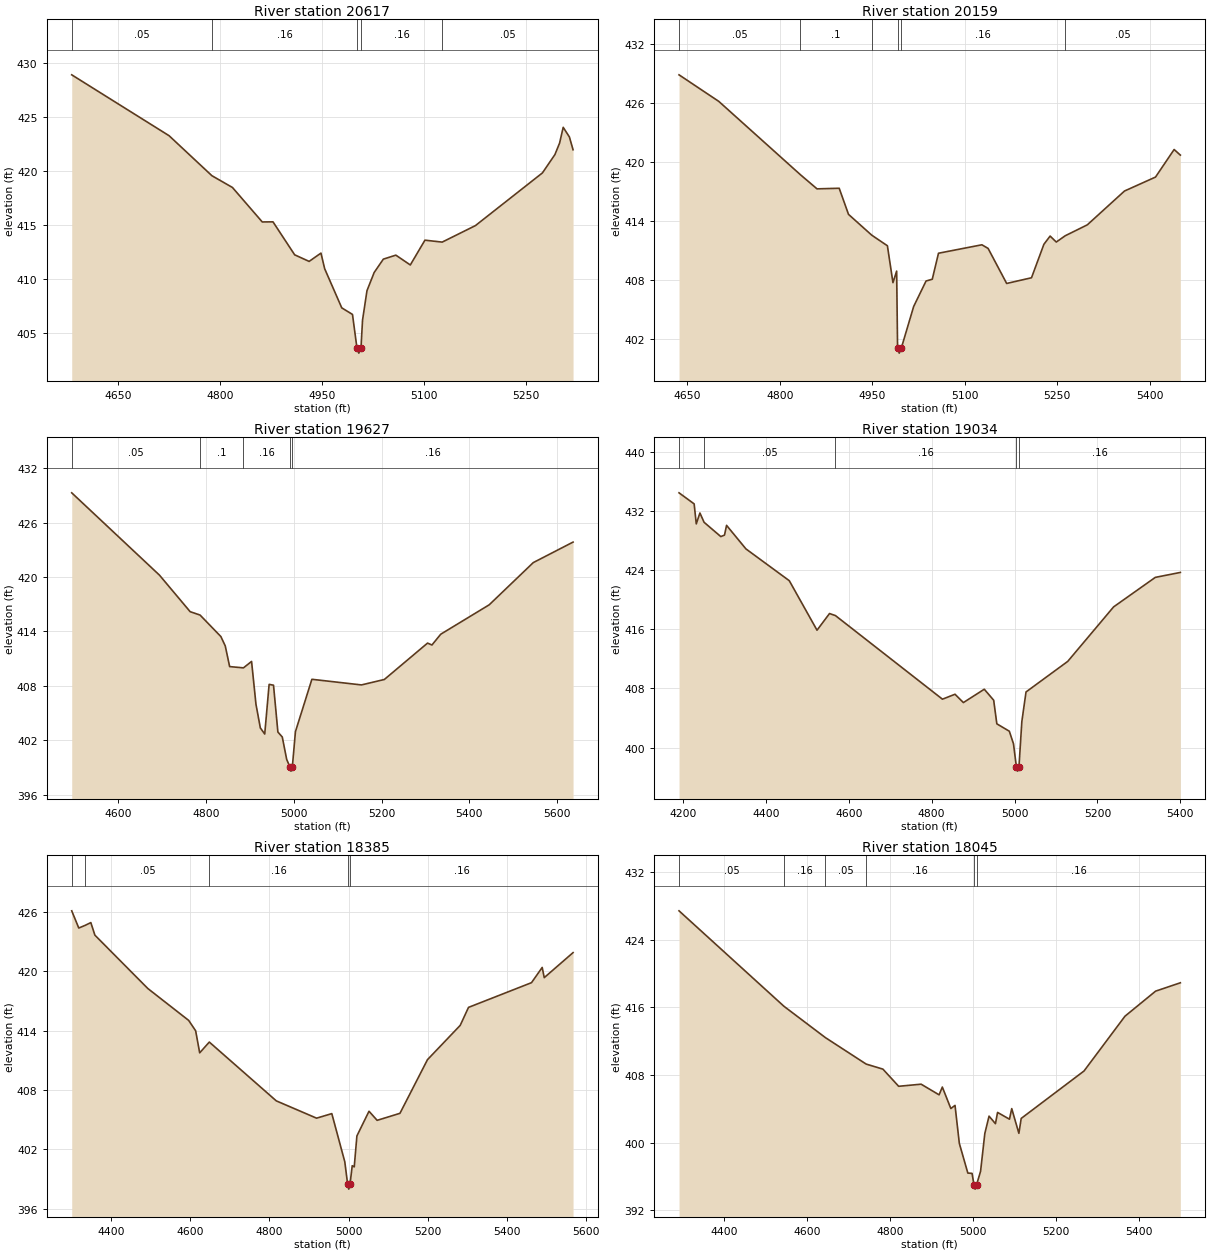
Type RM Length L Ch R = 1,20617,458,458,458
BEGIN DESCRIPTION:
UNT 066 IN UKCR 33.0
END DESCRIPTION:
XS GIS Cut Line= 3
      3606382.89     10609058.68      3606132.92     10609065.62
      3605674.55     10608898.94
#Sta/Elev= 30
  4581.9  428.91  4725.2  423.26  4788.2  419.55  4818.4  418.46  4862.3  415.26
  4878.1  415.27  4910.0  412.21  4931.3  411.60  4948.7  412.37  4954.1  410.93
  4979.3  407.29  4995.1  406.68  5001.6  403.59  5004.4  403.09  5007.6  403.59
  5009.9  406.16  5016.4  408.88  5027.0  410.57  5040.5  411.81  5058.9  412.18
  5080.2  411.27  5101.7  413.57  5127.1  413.39  5176.0  414.92  5274.6  419.81
  5293.0  421.51  5299.9  422.58  5305.2  424.04  5314.3  423.15  5319.7  421.96
#Mann=5,-1,0
  4581.9    0.05       0  4788.2    0.16       0  5001.6    0.07       0
  5007.6    0.16       0  5127.1    0.05       0
Bank Sta=5001.6,5007.6
Exp/Cntr=0.3,0.1

Type RM Length L Ch R = 1,20159,532,532,532
BEGIN DESCRIPTION:
UNT 066 IN UKCR 32.0
END DESCRIPTION:
XS GIS Cut Line= 3
      3606449.65     10608910.22      3606149.61     10608710.19
      3605699.58     10608760.19
#Sta/Elev= 30
  4636.5  428.87  4701.1  426.16  4833.3  418.70  4860.4  417.25  4896.4  417.31
  4911.5  414.65  4949.2  412.53  4974.6  411.45  4983.6  407.69  4989.6  408.87
  4991.1  401.01  4993.8  400.51  4997.1  401.01  5017.2  405.26  5037.3  407.86
  5047.4  408.04  5057.5  410.69  5127.9  411.55  5138.0  411.18  5168.1  407.61
  5208.4  408.19  5228.5  411.60  5238.6  412.44  5248.6  411.83  5263.1  412.47
  5298.9  413.58  5359.3  417.03  5409.6  418.45  5439.8  421.26  5449.9  420.69
#Mann=6,-1,0
  4636.5    0.05       0  4833.3     0.1       0  4949.2    0.16       0
  4991.1    0.07       0  4997.1    0.16       0  5263.1    0.05       0
Bank Sta=4991.1,4997.1
Exp/Cntr=0.3,0.1

Type RM Length L Ch R = 1,19627,593,593,593
BEGIN DESCRIPTION:
UNT 066 IN UKCR 31.0
END DESCRIPTION:
XS GIS Cut Line= 3
      3606599.62     10608260.19      3606049.61     10608260.19
      3605459.34     10608204.51
#Sta/Elev= 30
  4493.7  429.28  4693.7  420.21  4763.7  416.18  4786.3  415.81  4833.7  413.44
  4843.7  412.41  4853.7  410.13  4885.2  409.99  4903.7  410.70  4913.7  405.98
  4923.7  403.37  4933.7  402.70  4943.7  408.17  4953.7  408.08  4963.7  402.92
  4973.7  402.37  4983.7  399.91  4990.7  399.11  4993.5  398.61  4996.7  399.11
  5003.7  402.96  5041.2  408.73  5154.2  408.11  5206.4  408.71  5304.9  412.72
  5314.9  412.51  5335.0  413.70  5445.5  416.94  5545.9  421.59  5636.6  423.85
#Mann=5,-1,0
  4493.7    0.05       0  4786.3     0.1       0  4885.2    0.16       0
  4990.7    0.07       0  4996.7    0.16       0
Bank Sta=4990.7,4996.7
Exp/Cntr=0.3,0.1

Type RM Length L Ch R = 1,19034,649,649,649
BEGIN DESCRIPTION:
UNT 066 IN UKCR 30.0
END DESCRIPTION:
XS GIS Cut Line= 3
      3606749.57     10608010.18      3605999.61     10607910.19
      3605549.57     10607960.19
#Sta/Elev= 30
  4190.5  434.52  4227.0  433.02  4232.1  430.31  4240.9  431.79  4250.9  430.53
  4291.3  428.59  4300.2  428.79  4305.2  430.11  4351.9  426.92  4456.5  422.61
  4523.4  415.90  4553.6  418.16  4567.9  417.88  4826.0  406.55  4856.3  407.22
  4876.5  406.09  4926.9  407.90  4949.6  406.41  4957.2  403.21  4987.3  402.21
  4997.4  400.50  5004.5  397.30  5007.2  396.80  5010.5  397.30  5017.5  403.51
  5027.6  407.53  5128.2  411.67  5238.9  419.06  5339.5  423.06  5399.9  423.73
#Mann=5,-1,0
  4190.5    0.16       0  4250.9    0.05       0  4567.9    0.16       0
  5004.5    0.07       0  5010.5    0.16       0
Bank Sta=5004.5,5010.5
Exp/Cntr=0.3,0.1

Type RM Length L Ch R = 1,18385,340,340,340
BEGIN DESCRIPTION:
UNT 066 IN UKCR 29.0
END DESCRIPTION:
XS GIS Cut Line= 3
      3606737.07     10607621.17      3605987.09     10607475.34
      3605507.88     10607628.13
#Sta/Elev= 30
  4300.3  426.13  4318.1  424.39  4334.8  424.67  4348.6  424.94  4358.8  423.67
  4492.6  418.27  4595.9  415.04  4613.5  413.99  4623.7  411.76  4648.0  412.85
  4817.3  406.90  4919.1  405.15  4957.6  405.61  4990.4  400.74  4997.6  398.47
  5000.4  397.97  5003.6  398.47  5009.2  400.34  5014.3  400.22  5021.0  403.35
  5051.6  405.85  5072.2  404.93  5129.8  405.64  5199.4  411.07  5282.1  414.54
  5303.1  416.36  5462.3  418.86  5489.3  420.40  5494.5  419.37  5567.3  421.90
#Mann=5,-1,0
  4300.3    0.16       0  4334.8    0.05       0  4648.0    0.16       0
  4997.6    0.07       0  5003.6    0.16       0
Bank Sta=4997.6,5003.6
Exp/Cntr=0.3,0.1

Type RM Length L Ch R = 1,18045,598,598,598
BEGIN DESCRIPTION:
UNT 066 IN UKCR 28.0
END DESCRIPTION:
XS GIS Cut Line= 3
      3606799.63     10607110.18      3606028.76     10607280.90
      3605649.57     10607460.21
#Sta/Elev= 30
  4291.5  427.40  4544.6  416.11  4644.4  412.41  4742.7  409.28  4783.2  408.68
  4821.2  406.65  4875.3  406.90  4918.7  405.64  4926.5  406.56  4947.0  404.02
  4957.1  404.39  4967.5  399.90  4988.0  396.39  4998.2  396.35  5002.9  394.99
  5005.6  394.49  5008.9  394.99  5018.7  396.59  5029.0  401.08  5039.2  403.12
  5054.6  402.23  5059.7  403.56  5088.4  402.76  5093.9  404.01  5111.1  401.09
  5116.7  402.85  5268.2  408.46  5367.0  414.94  5440.8  417.90  5500.5  418.89
#Mann=6,-1,0
  4291.5    0.05       0  4544.6    0.16       0  4644.4    0.05       0
  4742.7    0.16       0  5002.9    0.07       0  5008.9    0.16       0
Bank Sta=5002.9,5008.9
Exp/Cntr=0.3,0.1

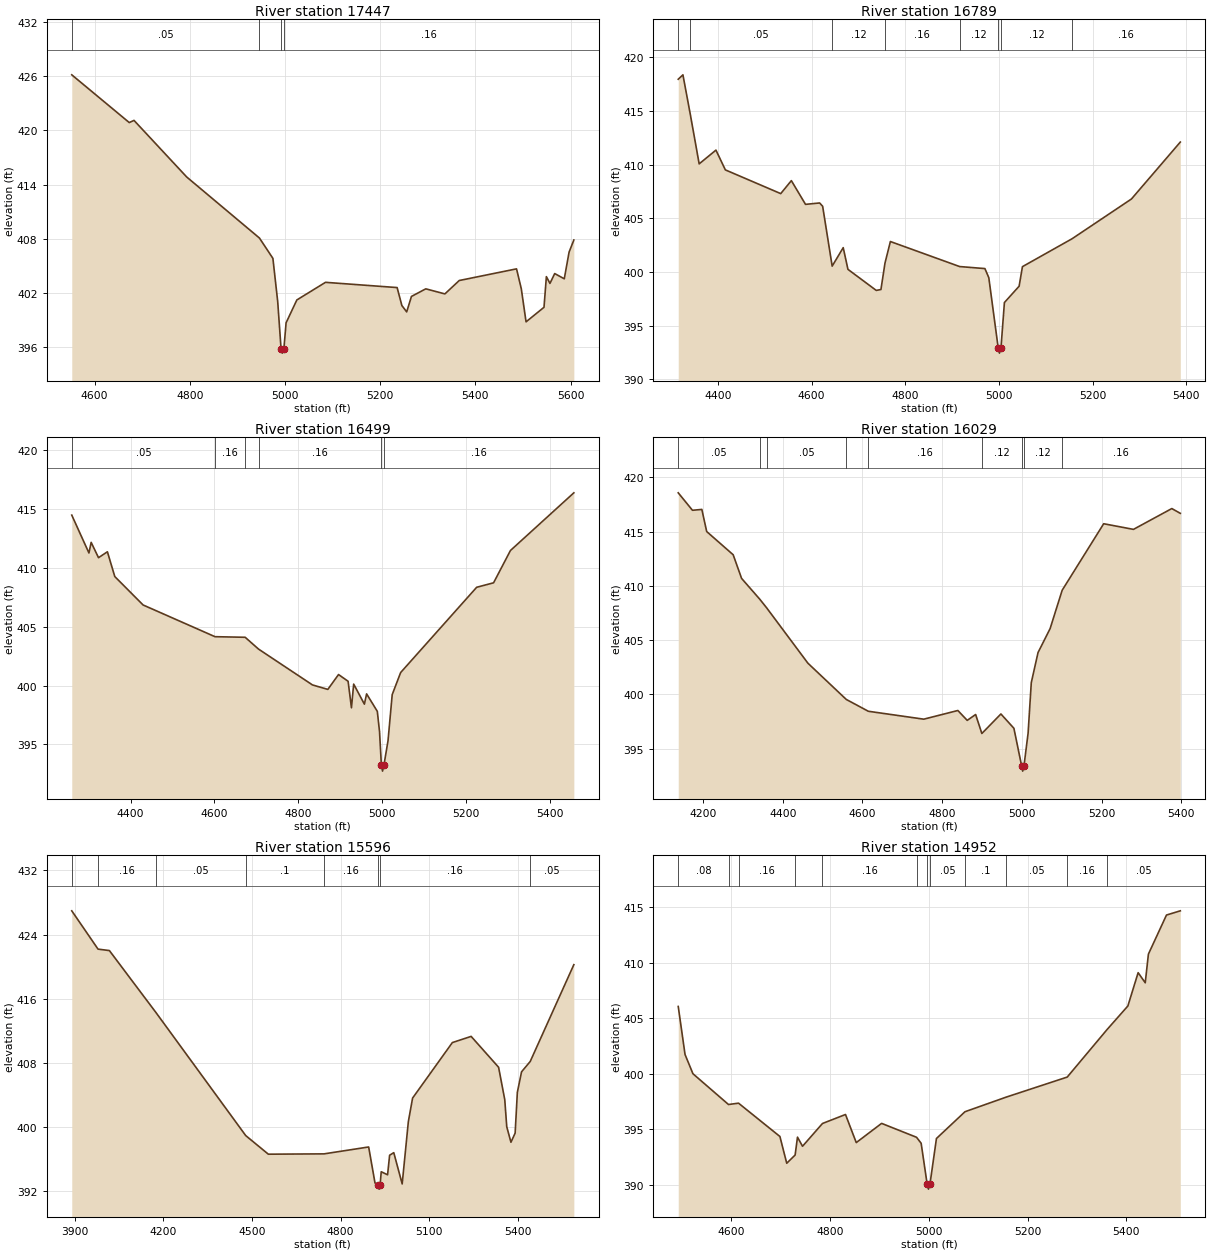
Type RM Length L Ch R = 1,17447,658,658,658
BEGIN DESCRIPTION:
UNT 066 IN UKCR 27.0
END DESCRIPTION:
XS GIS Cut Line= 3
      3606749.65     10607010.19      3606299.61     10606960.19
      3605699.60     10606910.19
#Sta/Elev= 30
  4551.9  426.14  4672.7  420.86  4682.7  421.10  4793.4  414.84  4946.2  408.09
  4974.5  405.84  4984.6  401.06  4991.6  395.86  4994.4  395.36  4997.6  395.86
  5002.2  398.71  5024.8  401.24  5085.0  403.19  5235.5  402.61  5245.5  400.62
  5255.6  399.92  5265.6  401.63  5295.7  402.47  5335.9  401.91  5366.0  403.39
  5486.4  404.68  5496.4  402.48  5506.4  398.82  5544.1  400.43  5549.1  403.82
  5556.6  403.07  5566.6  404.16  5586.7  403.58  5596.8  406.53  5606.8  407.87
#Mann=4,-1,0
  4551.9    0.05       0  4946.2    0.16       0  4991.6    0.07       0
  4997.6    0.16       0
Bank Sta=4991.6,4997.6
Exp/Cntr=0.3,0.1

Type RM Length L Ch R = 1,16789,290,290,290
BEGIN DESCRIPTION:
UNT 066 IN UKCR 26.0
END DESCRIPTION:
XS GIS Cut Line= 3
      3606699.59     10606610.19      3606063.48     10606537.84
      3605649.59     10606660.19
#Sta/Elev= 30
  4315.2  417.94  4325.2  418.35  4340.8  414.71  4359.9  410.06  4395.7  411.34
  4415.8  409.50  4534.0  407.29  4556.7  408.50  4586.9  406.29  4617.1  406.42
  4623.5  406.11  4643.8  400.54  4667.4  402.26  4677.5  400.24  4737.9  398.28
  4747.9  398.36  4756.6  400.83  4768.1  402.83  4915.9  400.50  4969.9  400.31
  4978.2  399.46  4998.2  392.94  5000.9  392.44  5004.2  392.94  5011.5  397.15
  5042.9  398.67  5050.0  400.49  5156.0  403.09  5282.7  406.79  5387.0  412.09
#Mann=8,-1,0
  4315.2    0.16       0  4340.8    0.05       0  4643.8    0.12       0
  4756.6    0.16       0  4915.9    0.12       0  4998.2    0.07       0
  5004.2    0.12       0  5156.0    0.16       0
Bank Sta=4998.2,5004.2
Exp/Cntr=0.3,0.1

Type RM Length L Ch R = 1,16499,470,470,470
BEGIN DESCRIPTION:
UNT 066 IN UKCR 25.0
END DESCRIPTION:
XS GIS Cut Line= 3
      3606699.60     10606560.18      3605999.61     10606310.19
      3605549.57     10606360.19
#Sta/Elev= 30
  4260.0  414.45  4300.9  411.24  4306.2  412.14  4323.7  410.84  4344.9  411.34
  4362.5  409.24  4429.9  406.83  4601.3  404.14  4673.1  404.09  4704.9  403.09
  4833.4  400.05  4870.0  399.67  4895.5  400.93  4918.3  400.36  4926.3  398.11
  4931.6  400.12  4957.1  398.42  4962.4  399.29  4987.9  397.81  4993.2  396.09
  4997.6  393.24  5000.4  392.74  5003.6  393.24  5013.4  395.31  5023.4  399.23
  5043.5  401.10  5224.6  408.33  5264.9  408.71  5305.1  411.45  5456.1  416.34
#Mann=6,-1,0
  4260.0    0.05       0  4601.3    0.16       0  4673.1    0.05       0
  4704.9    0.16       0  4997.6    0.07       0  5003.6    0.16       0
Bank Sta=4997.6,5003.6
Exp/Cntr=0.3,0.1

Type RM Length L Ch R = 1,16029,433,433,433
BEGIN DESCRIPTION:
UNT 066 IN UKCR 24.0
END DESCRIPTION:
XS GIS Cut Line= 3
      3606799.65     10606360.21      3606099.61     10605910.19
      3605699.62     10605760.19
#Sta/Elev= 30
  4137.8  418.58  4173.5  416.97  4197.0  417.05  4209.2  415.01  4275.6  412.87
  4296.7  410.69  4342.8  408.75  4360.1  407.95  4463.1  402.87  4559.3  399.53
  4614.6  398.44  4753.7  397.71  4839.2  398.51  4862.7  397.60  4883.8  398.14
  4899.4  396.39  4947.2  398.19  4979.8  396.87  4999.1  393.42  5001.8  392.92
  5005.1  393.42  5015.4  396.42  5023.4  401.08  5040.3  403.85  5070.6  406.06
  5100.9  409.60  5205.0  415.73  5279.7  415.21  5375.9  417.13  5397.2  416.69
#Mann=9,-1,0
  4137.8    0.05       0  4342.8     0.1       0  4360.1    0.05       0
  4559.3     0.1       0  4614.6    0.16       0  4899.4    0.12       0
  4999.1    0.07       0  5005.1    0.12       0  5100.9    0.16       0
Bank Sta=4999.1,5005.1
Exp/Cntr=0.3,0.1

Type RM Length L Ch R = 1,15596,644,644,644
BEGIN DESCRIPTION:
UNT 066 IN UKCR 23.0
END DESCRIPTION:
XS GIS Cut Line= 3
      3607049.62     10606460.20      3606299.61     10605660.19
      3605849.60     10605260.18
#Sta/Elev= 30
  3890.5  426.96  3979.4  422.18  4017.8  422.00  4175.7  414.25  4479.1  398.91
  4555.6  396.59  4744.1  396.63  4895.0  397.49  4916.5  392.99  4927.7  392.73
  4930.4  392.23  4933.7  392.73  4937.5  394.40  4959.0  394.02  4965.9  396.46
  4980.0  396.78  5008.4  392.88  5029.3  400.66  5043.6  403.59  5178.2  410.52
  5241.7  411.29  5334.6  407.44  5355.5  403.39  5362.2  400.02  5376.4  398.08
  5390.6  399.22  5398.1  404.32  5412.3  406.87  5441.6  408.16  5589.2  420.24
#Mann=8,-1,0
  3890.5    0.05       0  3979.4    0.16       0  4175.7    0.05       0
  4479.1     0.1       0  4744.1    0.16       0  4927.7    0.07       0
  4933.7    0.16       0  5441.6    0.05       0
Bank Sta=4927.7,4933.7
Exp/Cntr=0.3,0.1

Type RM Length L Ch R = 1,14952,440,440,440
BEGIN DESCRIPTION:
UNT 066 IN UKCR 22.0
END DESCRIPTION:
XS GIS Cut Line= 3
      3606849.63     10605860.23      3606535.70     10605294.79
      3606249.63     10605060.20
#Sta/Elev= 30
  4492.4  406.06  4506.2  401.73  4522.2  400.00  4594.2  397.23  4614.5  397.35
  4698.3  394.35  4712.1  391.94  4729.1  392.68  4733.9  394.29  4744.1  393.47
  4784.5  395.52  4831.1  396.33  4852.9  393.80  4904.2  395.53  4974.9  394.28
  4984.3  393.74  4996.3  390.11  4999.1  389.61  5002.3  390.11  5015.3  394.17
  5073.1  396.58  5156.2  397.89  5280.1  399.70  5360.8  403.98  5402.9  406.10
  5423.7  409.10  5438.1  408.19  5444.5  410.77  5481.1  414.29  5509.1  414.67
#Mann=12,-1,0
  4492.4    0.08       0  4594.2    0.05       0  4614.5    0.16       0
  4729.1    0.12       0  4784.5    0.16       0  4974.9    0.05       0
  4996.3    0.03       0  5002.3    0.05       0  5073.1     0.1       0
  5156.2    0.05       0  5280.1    0.16       0  5360.8    0.05       0
Bank Sta=4996.3,5002.3
Exp/Cntr=0.3,0.1

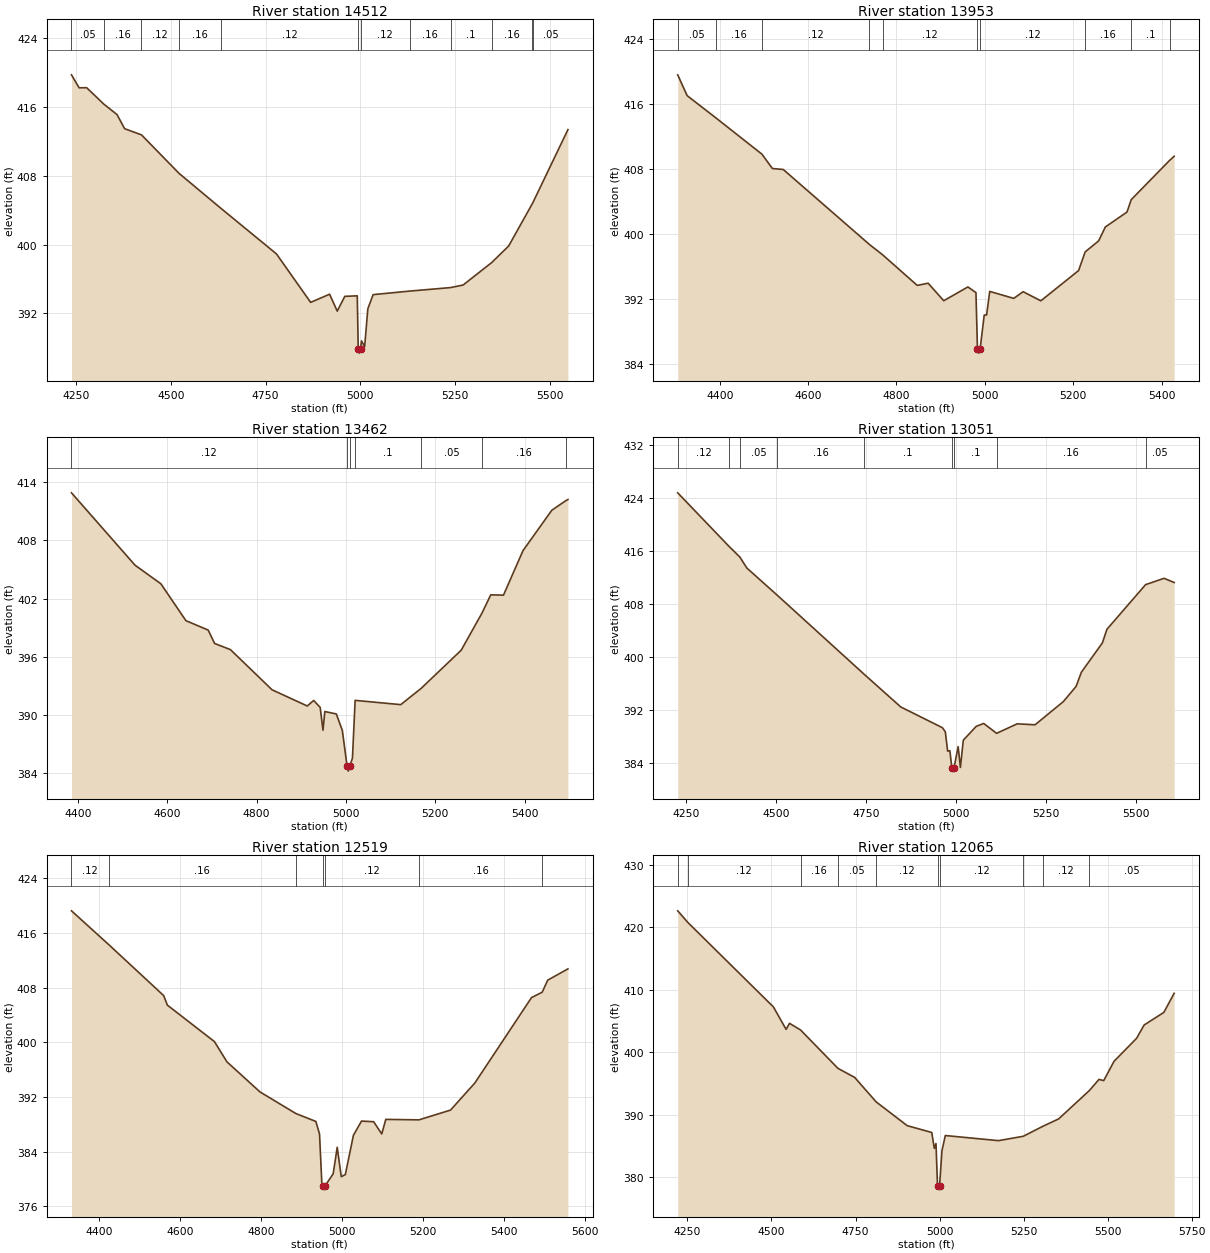
Type RM Length L Ch R = 1,14512,559,559,559
BEGIN DESCRIPTION:
UNT 066 IN UKCR 21.0
END DESCRIPTION:
XS GIS Cut Line= 3
      3607599.62     10605210.19      3606849.61     10605260.19
      3606349.61     10605010.19
#Sta/Elev= 30
  4237.7  419.77  4257.8  418.26  4277.8  418.27  4323.1  416.36  4358.0  415.14
  4378.0  413.50  4422.5  412.78  4521.9  408.29  4633.3  404.19  4778.9  398.92
  4869.1  393.28  4919.2  394.23  4939.3  392.26  4959.3  393.98  4992.2  394.04
  4994.8  387.87  4997.5  387.37  5000.8  387.87  5003.4  388.80  5011.7  388.13
  5020.1  392.53  5034.1  394.18  5130.1  394.59  5238.5  395.00  5271.7  395.30
  5347.0  397.91  5391.9  399.84  5452.5  404.62  5455.5  404.86  5548.4  413.39
#Mann=12,-1,0
  4237.7    0.05       0  4323.1    0.16       0  4422.5    0.12       0
  4521.9    0.16       0  4633.3    0.12       0  4994.8    0.07       0
  5000.8    0.12       0  5130.1    0.16       0  5238.5     0.1       0
  5347.0    0.16       0  5452.5     0.1       0  5455.5    0.05       0
Bank Sta=4994.8,5000.8
Exp/Cntr=0.3,0.1

Type RM Length L Ch R = 1,13953,491,491,491
BEGIN DESCRIPTION:
UNT 066 IN UKCR 20.0
END DESCRIPTION:
XS GIS Cut Line= 3
      3607599.59     10605160.18      3606949.61     10604910.19
      3606549.61     10604760.19
#Sta/Elev= 30
  4305.0  419.59  4326.4  417.02  4392.6  414.23  4495.8  409.80  4519.3  408.04
  4543.9  407.92  4739.0  398.67  4768.8  397.40  4847.1  393.63  4871.8  393.90
  4907.1  391.74  4961.8  393.44  4980.0  392.74  4983.4  385.78  4986.1  385.28
  4989.4  385.78  4998.7  389.98  5004.1  389.98  5011.2  392.89  5065.5  392.03
  5086.8  392.85  5126.9  391.73  5212.3  395.46  5227.2  397.76  5257.7  399.12
  5272.8  400.83  5321.8  402.67  5331.4  404.20  5418.6  409.06  5428.6  409.55
#Mann=10,-1,0
  4305.0    0.05       0  4392.6    0.16       0  4495.8    0.12       0
  4739.0    0.16       0  4768.8    0.12       0  4983.4    0.07       0
  4989.4    0.12       0  5227.2    0.16       0  5331.4     0.1       0
  5418.6    0.05       0
Bank Sta=4983.4,4989.4
Exp/Cntr=0.3,0.1

Type RM Length L Ch R = 1,13462,411,411,411
BEGIN DESCRIPTION:
UNT 066 IN UKCR 19.0
END DESCRIPTION:
XS GIS Cut Line= 3
      3607549.61     10605010.19      3607199.61     10604560.19
      3606749.63     10604260.20
#Sta/Elev= 30
  4385.8  412.89  4527.9  405.44  4585.8  403.52  4641.9  399.72  4691.7  398.75
  4706.1  397.37  4741.4  396.74  4834.6  392.60  4913.4  390.93  4927.8  391.50
  4942.3  390.78  4948.6  388.44  4952.7  390.36  4978.4  390.11  4991.9  388.41
  5002.5  384.72  5005.2  384.22  5008.5  384.72  5014.5  385.56  5020.5  391.51
  5122.6  391.07  5168.1  392.74  5257.9  396.68  5304.1  400.48  5324.0  402.38
  5352.5  402.35  5396.1  406.93  5460.7  411.10  5491.9  412.08  5496.7  412.20
#Mann=7,-1,0
  4385.8    0.12       0  5002.5    0.07       0  5008.5    0.12       0
  5020.5     0.1       0  5168.1    0.05       0  5304.1    0.16       0
  5491.9    0.05       0
Bank Sta=5002.5,5008.5
Exp/Cntr=0.3,0.1

Type RM Length L Ch R = 1,13051,532,532,532
BEGIN DESCRIPTION:
UNT 066 IN UKCR 18.0
END DESCRIPTION:
XS GIS Cut Line= 3
      3608099.63     10604560.20      3607445.42     10604315.62
      3606899.65     10603910.22
#Sta/Elev= 30
  4227.8  424.82  4370.3  416.73  4400.2  415.13  4420.0  413.45  4504.3  409.35
  4744.8  397.45  4847.1  392.48  4962.6  389.35  4970.8  388.73  4977.2  385.81
  4983.4  385.88  4988.8  383.29  4991.5  382.79  4994.8  383.29  5006.4  386.49
  5012.6  383.35  5020.7  387.46  5056.5  389.55  5077.3  389.99  5113.3  388.50
  5170.2  389.93  5220.0  389.79  5298.4  393.29  5333.9  395.59  5348.5  397.73
  5406.8  402.15  5419.4  404.21  5526.7  410.95  5578.0  411.91  5606.1  411.28
#Mann=9,-1,0
  4227.8    0.12       0  4370.3    0.16       0  4400.2    0.05       0
  4504.3    0.16       0  4744.8     0.1       0  4988.8    0.07       0
  4994.8     0.1       0  5113.3    0.16       0  5526.7    0.05       0
Bank Sta=4988.8,4994.8
Exp/Cntr=0.3,0.1

Type RM Length L Ch R = 1,12519,454,454,454
BEGIN DESCRIPTION:
UNT 066 IN UKCR 17.0
END DESCRIPTION:
XS GIS Cut Line= 3
      3608149.64     10604210.20      3607599.61     10603910.19
      3606999.64     10603910.19
#Sta/Elev= 30
  4331.5  419.23  4423.9  414.27  4559.3  406.83  4568.4  405.44  4684.6  400.11
  4715.5  397.15  4797.1  392.75  4885.7  389.59  4935.2  388.43  4944.3  386.59
  4950.0  379.40  4952.2  379.03  4954.9  378.53  4958.2  379.03  4978.0  380.77
  4988.0  384.65  4998.0  380.35  5008.0  380.65  5028.0  386.40  5048.0  388.48
  5078.0  388.39  5098.0  386.60  5108.0  388.73  5189.9  388.66  5268.0  390.09
  5328.0  394.05  5468.0  406.54  5494.4  407.33  5508.0  409.09  5558.0  410.74
#Mann=7,-1,0
  4331.5    0.12       0  4423.9    0.16       0  4885.7    0.12       0
  4952.2    0.07       0  4958.2    0.12       0  5189.9    0.16       0
  5494.4    0.05       0
Bank Sta=4952.2,4958.2
Exp/Cntr=0.3,0.1

Type RM Length L Ch R = 1,12065,464,464,464
BEGIN DESCRIPTION:
UNT 066 IN UKCR 16.0
END DESCRIPTION:
XS GIS Cut Line= 3
      3608449.61     10603460.19      3607649.61     10603560.19
      3607049.65     10603860.17
#Sta/Elev= 30
  4221.0  422.63  4251.1  420.77  4505.7  407.25  4543.5  403.65  4553.6  404.62
  4586.6  403.55  4697.8  397.41  4747.6  395.96  4811.3  392.05  4903.8  388.24
  4976.8  387.15  4984.4  384.61  4989.4  385.38  4994.0  378.58  4996.7  378.08
  5000.0  378.58  5007.1  384.21  5017.1  386.66  5175.4  385.84  5249.1  386.54
  5306.6  388.12  5354.3  389.32  5445.9  393.87  5474.4  395.65  5488.4  395.45
  5519.2  398.55  5586.2  402.22  5608.6  404.35  5667.3  406.37  5698.0  409.43
#Mann=10,-1,0
  4221.0    0.16       0  4251.1    0.12       0  4586.6    0.16       0
  4697.8    0.05       0  4811.3    0.12       0  4994.0    0.07       0
  5000.0    0.12       0  5249.1    0.16       0  5306.6    0.12       0
  5445.9    0.05       0
Bank Sta=4994,5000
Exp/Cntr=0.3,0.1

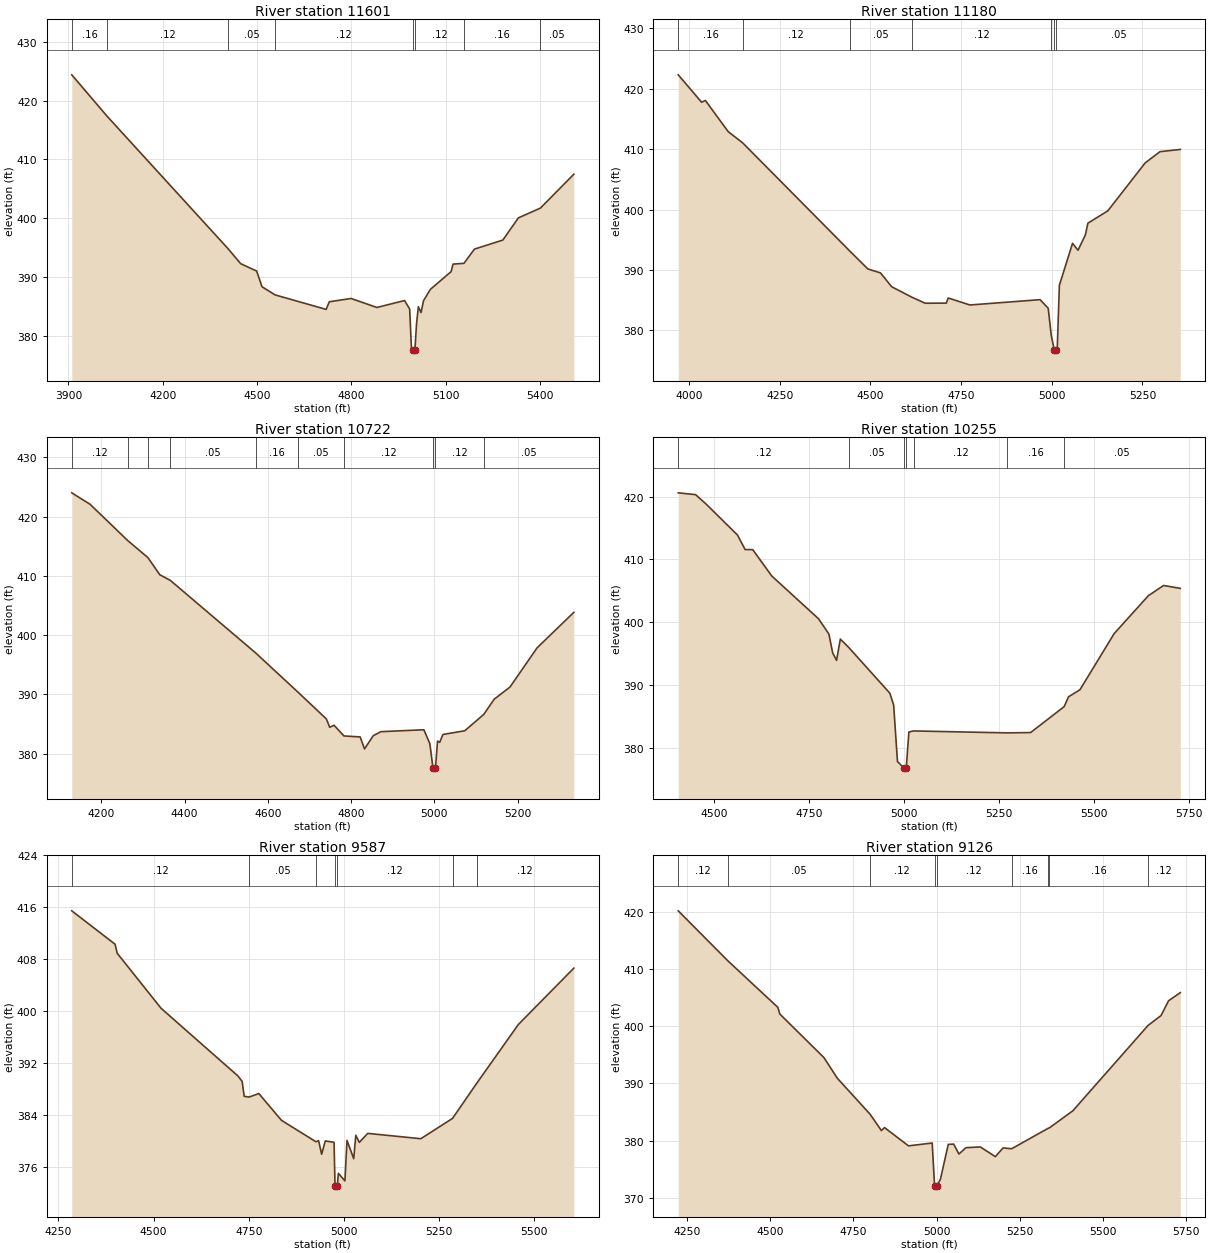
Type RM Length L Ch R = 1,11601,421,421,421
BEGIN DESCRIPTION:
UNT 066 IN UKCR 15.0
END DESCRIPTION:
XS GIS Cut Line= 3
      3608473.17     10603371.17      3607646.81     10603204.51
      3606980.15     10603558.67
#Sta/Elev= 30
  3910.5  424.37  4023.5  417.29  4407.3  394.82  4448.1  392.23  4498.9  390.98
  4516.0  388.30  4557.6  386.92  4720.0  384.45  4730.2  385.75  4799.4  386.31
  4881.7  384.78  4969.6  385.96  4985.9  384.51  4991.6  377.73  4996.5  377.51
  4999.2  377.01  5002.5  377.51  5007.9  382.10  5013.6  384.90  5022.1  383.91
  5029.9  385.92  5051.9  387.87  5117.8  390.88  5124.0  392.16  5158.7  392.29
  5192.0  394.71  5282.4  396.25  5332.0  400.03  5402.2  401.70  5508.4  407.46
#Mann=8,-1,0
  3910.5    0.16       0  4023.5    0.12       0  4407.3    0.05       0
  4557.6    0.12       0  4996.5    0.07       0  5002.5    0.12       0
  5158.7    0.16       0  5402.2    0.05       0
Bank Sta=4996.5,5002.5
Exp/Cntr=0.3,0.1

Type RM Length L Ch R = 1,11180,458,458,458
BEGIN DESCRIPTION:
UNT 066 IN UKCR 14.0
END DESCRIPTION:
XS GIS Cut Line= 2
      3608452.34     10603246.17      3607105.10     10602926.72
#Sta/Elev= 30
  3970.0  422.30  4034.5  417.76  4044.8  418.06  4107.9  412.89  4147.5  411.05
  4443.6  393.10  4493.1  390.16  4527.8  389.51  4558.6  387.22  4613.5  385.51
  4651.1  384.49  4709.4  384.51  4714.5  385.36  4774.4  384.20  4967.9  385.08
  4990.3  383.66  4998.7  379.19  5007.1  376.73  5009.8  376.23  5013.1  376.73
  5015.2  376.94  5021.1  387.46  5057.4  394.41  5072.5  393.26  5093.0  395.83
  5099.7  397.74  5154.7  399.78  5257.5  407.71  5298.6  409.58  5354.6  409.95
#Mann=7,-1,0
  3970.0    0.16       0  4147.5    0.12       0  4443.6    0.05       0
  4613.5    0.12       0  4998.7    0.05       0  5007.1    0.03       0
  5013.1    0.05       0
Bank Sta=5007.1,5013.1
Exp/Cntr=0.3,0.1

Type RM Length L Ch R = 1,10722,467,467,467
BEGIN DESCRIPTION:
UNT 066 IN UKCR 13.0
END DESCRIPTION:
XS GIS Cut Line= 2
      3608521.80     10603023.95      3607369.07     10602669.80
#Sta/Elev= 30
  4129.1  424.00  4173.2  422.06  4263.7  415.93  4312.0  413.07  4340.6  410.17
  4365.9  409.22  4570.4  397.00  4672.7  390.34  4740.6  385.84  4748.6  384.43
  4759.1  384.77  4782.8  382.97  4821.8  382.80  4832.3  380.78  4853.2  383.01
  4871.5  383.69  4974.8  384.01  4989.2  381.66  4996.7  377.53  4999.4  377.03
  5002.7  377.53  5007.6  382.10  5012.8  381.89  5020.6  383.22  5072.9  383.84
  5118.5  386.59  5143.7  389.17  5181.6  391.22  5247.0  397.86  5335.0  403.83
#Mann=10,-1,0
  4129.1    0.12       0  4263.7    0.16       0  4312.0    0.12       0
  4365.9    0.05       0  4570.4    0.16       0  4672.7    0.05       0
  4782.8    0.12       0  4996.7    0.07       0  5002.7    0.12       0
  5118.5    0.05       0
Bank Sta=4996.7,5002.7
Exp/Cntr=0.3,0.1

Type RM Length L Ch R = 1,10255,668,668,668
BEGIN DESCRIPTION:
UNT 066 IN UKCR 12.0
END DESCRIPTION:
XS GIS Cut Line= 3
      3608605.19     10602600.35      3607896.81     10602551.73
      3607285.66     10602551.73
#Sta/Elev= 30
  4405.4  420.63  4451.1  420.34  4478.4  418.86  4561.3  413.90  4581.4  411.58
  4601.4  411.57  4651.6  407.36  4774.8  400.53  4801.9  398.10  4811.9  395.09
  4822.0  393.91  4832.0  397.30  4853.9  395.98  4962.3  388.67  4972.3  386.77
  4982.3  377.77  4999.4  376.74  5002.1  376.24  5005.4  376.74  5012.4  382.48
  5024.5  382.65  5271.4  382.34  5332.6  382.39  5420.8  386.52  5432.6  388.10
  5462.6  389.23  5552.6  398.18  5642.6  404.23  5682.6  405.85  5726.6  405.39
#Mann=7,-1,0
  4405.4    0.12       0  4853.9    0.05       0  4999.4    0.03       0
  5005.4    0.05       0  5024.5    0.12       0  5271.4    0.16       0
  5420.8    0.05       0
Bank Sta=4999.4,5005.4
Exp/Cntr=0.3,0.1

Type RM Length L Ch R = 1,9587,461,461,461
BEGIN DESCRIPTION:
UNT 066 IN UKCR 11.0
END DESCRIPTION:
XS GIS Cut Line= 3
      3608556.54     10602503.12      3607764.87     10602142.01
      3607327.38     10602239.23
#Sta/Elev= 30
  4285.4  415.43  4399.2  410.28  4404.7  408.89  4519.9  400.41  4721.7  389.98
  4732.7  389.15  4738.2  386.84  4751.2  386.73  4776.6  387.27  4835.9  383.15
  4926.5  379.84  4933.5  380.00  4941.5  377.92  4951.1  379.97  4974.1  379.75
  4976.6  373.04  4979.3  372.54  4982.6  373.04  4985.5  374.98  5002.6  373.81
  5008.1  380.05  5025.7  377.23  5031.2  380.84  5040.4  379.74  5062.4  381.13
  5201.9  380.31  5285.2  383.44  5348.4  388.83  5458.0  397.91  5603.7  406.60
#Mann=7,-1,0
  4285.4    0.12       0  4751.2    0.05       0  4926.5    0.12       0
  4976.6    0.07       0  4982.6    0.12       0  5285.2    0.16       0
  5348.4    0.12       0
Bank Sta=4976.6,4982.6
Exp/Cntr=0.3,0.1

Type RM Length L Ch R = 1,9126,479,479,479
BEGIN DESCRIPTION:
UNT 066 IN UKCR 10.0
END DESCRIPTION:
XS GIS Cut Line= 3
      3608699.63     10601960.19      3607899.61     10601810.19
      3607299.60     10602160.20
#Sta/Elev= 30
  4223.7  420.15  4373.1  411.40  4523.0  403.28  4529.0  402.11  4661.2  394.52
  4701.9  390.88  4799.9  384.62  4834.2  381.74  4843.5  382.27  4915.6  379.07
  4986.8  379.57  4994.0  372.01  4996.7  371.51  5000.0  372.01  5011.4  373.22
  5035.1  379.33  5051.3  379.38  5067.0  377.65  5088.5  378.76  5131.5  378.88
  5176.6  377.19  5199.7  378.71  5225.6  378.57  5335.5  382.15  5338.5  382.20
  5409.4  385.20  5635.4  400.12  5674.4  401.85  5697.1  404.44  5732.3  405.85
#Mann=9,-1,0
  4223.7    0.12       0  4373.1    0.05       0  4799.9    0.12       0
  4994.0    0.07       0  5000.0    0.12       0  5225.6    0.16       0
  5335.5    0.12       0  5338.5    0.16       0  5635.4    0.12       0
Bank Sta=4994,5000
Exp/Cntr=0.3,0.1

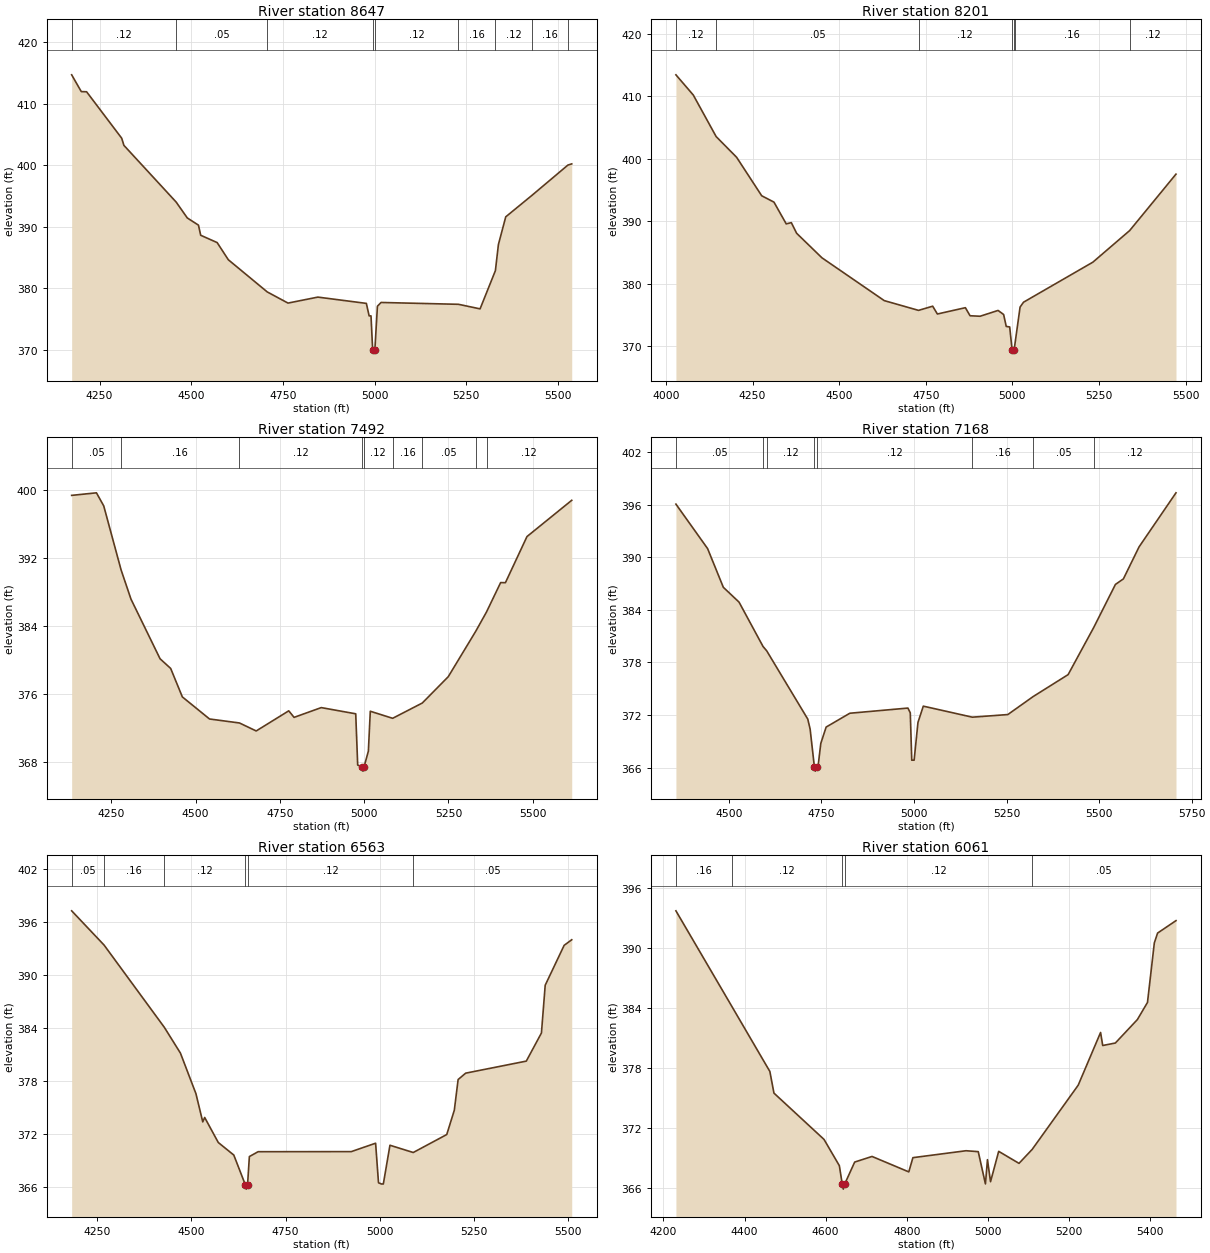
Type RM Length L Ch R = 1,8647,446,446,446
BEGIN DESCRIPTION:
UNT 066 IN UKCR 9.0
END DESCRIPTION:
XS GIS Cut Line= 3
      3608599.62     10601760.19      3607799.61     10601610.19
      3607249.56     10601610.19
#Sta/Elev= 30
  4173.9  414.67  4200.2  411.94  4214.6  411.92  4310.4  404.37  4316.4  403.21
  4458.9  394.00  4489.3  391.42  4519.8  390.25  4525.8  388.61  4570.7  387.42
  4601.2  384.63  4707.4  379.40  4764.0  377.59  4845.4  378.56  4977.7  377.54
  4985.3  375.51  4990.4  375.51  4994.9  369.96  4997.6  369.46  5000.9  369.96
  5007.9  377.08  5017.9  377.69  5229.0  377.39  5287.9  376.65  5329.7  382.86
  5337.9  387.10  5357.9  391.60  5428.6  395.05  5527.5  400.01  5537.9  400.20
#Mann=9,-1,0
  4173.9    0.12       0  4458.9    0.05       0  4707.4    0.12       0
  4994.9    0.07       0  5000.9    0.12       0  5229.0    0.16       0
  5329.7    0.12       0  5428.6    0.16       0  5527.5    0.12       0
Bank Sta=4994.9,5000.9
Exp/Cntr=0.3,0.1

Type RM Length L Ch R = 1,8201,709,709,709
BEGIN DESCRIPTION:
UNT 066 IN UKCR 8.0
END DESCRIPTION:
XS GIS Cut Line= 3
      3608599.58     10601710.17      3607799.61     10601210.19
      3607299.57     10601210.19
#Sta/Elev= 30
  4028.8  413.46  4078.9  410.23  4144.9  403.58  4203.9  400.27  4276.4  394.11
  4311.8  393.09  4347.2  389.61  4361.9  389.81  4377.2  388.11  4450.3  384.18
  4630.2  377.33  4729.1  375.77  4769.9  376.44  4783.5  375.19  4864.3  376.20
  4877.8  374.91  4906.7  374.83  4958.6  375.76  4974.7  375.11  4982.2  373.20
  4992.2  373.12  4999.2  369.43  5001.9  368.93  5005.2  369.43  5006.6  370.08
  5022.2  376.30  5032.2  377.08  5232.2  383.48  5338.5  388.54  5472.2  397.57
#Mann=7,-1,0
  4028.8    0.12       0  4144.9    0.05       0  4729.1    0.12       0
  4999.2    0.07       0  5005.2    0.12       0  5006.6    0.16       0
  5338.5    0.12       0
Bank Sta=4999.2,5005.2
Exp/Cntr=0.3,0.1

Type RM Length L Ch R = 1,7492,324,324,324
BEGIN DESCRIPTION:
UNT 066 IN UKCR 7.0
END DESCRIPTION:
XS GIS Cut Line= 3
      3608424.57     10600336.47      3607549.59     10600836.45
      3607203.46     10601161.82
#Sta/Elev= 30
  4132.8  399.40  4206.3  399.70  4227.9  398.16  4279.3  390.63  4308.6  387.19
  4394.9  380.16  4426.4  379.02  4461.0  375.67  4541.6  373.07  4630.3  372.60
  4680.0  371.66  4776.5  374.03  4792.3  373.26  4872.9  374.41  4975.1  373.68
  4980.9  367.65  4993.7  367.43  4996.5  366.93  4999.7  367.43  5012.6  369.28
  5018.3  373.98  5084.6  373.15  5172.5  374.95  5249.5  378.05  5330.7  383.38
  5362.9  385.67  5404.8  389.13  5419.0  389.12  5482.9  394.55  5615.6  398.82
#Mann=9,-1,0
  4132.8    0.05       0  4279.3    0.16       0  4630.3    0.12       0
  4993.7    0.07       0  4999.7    0.12       0  5084.6    0.16       0
  5172.5    0.05       0  5330.7    0.16       0  5362.9    0.12       0
Bank Sta=4993.7,4999.7
Exp/Cntr=0.3,0.1

Type RM Length L Ch R = 1,7168,605,605,605
BEGIN DESCRIPTION:
UNT 066 IN UKCR 6.0
END DESCRIPTION:
XS GIS Cut Line= 3
      3608099.60     10600060.19      3607599.61     10600460.19
      3607149.63     10601010.16
#Sta/Elev= 30
  4356.8  396.08  4442.4  391.00  4484.9  386.58  4527.3  384.89  4592.2  379.82
  4602.0  379.33  4713.0  371.53  4719.4  370.38  4730.8  366.09  4733.5  365.59
  4736.8  366.09  4741.0  366.22  4748.2  368.76  4762.6  370.62  4826.6  372.20
  4983.5  372.79  4989.9  372.25  4993.9  366.84  5000.3  366.84  5010.7  371.16
  5025.1  373.01  5157.6  371.75  5253.4  372.05  5321.7  374.10  5416.3  376.61
  5485.7  382.01  5544.1  386.91  5565.6  387.54  5608.0  391.20  5707.7  397.37
#Mann=8,-1,0
  4356.8    0.05       0  4592.2    0.16       0  4602.0    0.12       0
  4730.8    0.07       0  4736.8    0.12       0  5157.6    0.16       0
  5321.7    0.05       0  5485.7    0.12       0
Bank Sta=4730.8,4736.8
Exp/Cntr=0.3,0.1

Type RM Length L Ch R = 1,6563,502,502,502
BEGIN DESCRIPTION:
UNT 066 IN UKCR 5.0
END DESCRIPTION:
XS GIS Cut Line= 3
      3608099.59     10599960.19      3607299.61     10600160.19
      3606799.60     10600110.19
#Sta/Elev= 30
  4182.5  397.27  4268.5  393.40  4428.6  384.09  4471.1  381.19  4512.3  376.60
  4530.4  373.41  4535.5  373.91  4571.6  371.08  4612.8  369.66  4643.3  366.31
  4646.1  365.81  4649.3  366.31  4654.1  369.49  4677.3  370.04  4924.6  370.05
  4989.1  371.00  4996.8  366.53  5004.5  366.39  5009.6  366.39  5027.2  370.77
  5089.0  369.95  5177.9  371.98  5198.0  374.73  5208.1  378.20  5228.2  378.92
  5389.0  380.28  5429.2  383.46  5439.2  388.86  5489.5  393.37  5509.6  394.00
#Mann=6,-1,0
  4182.5    0.05       0  4268.5    0.16       0  4428.6    0.12       0
  4643.3    0.07       0  4649.3    0.12       0  5089.0    0.05       0
Bank Sta=4643.3,4649.3
Exp/Cntr=0.3,0.1

Type RM Length L Ch R = 1,6061,430,430,430
BEGIN DESCRIPTION:
UNT 066 IN UKCR 4.0
END DESCRIPTION:
XS GIS Cut Line= 3
      3607999.57     10599910.18      3607199.61     10599810.19
      3606799.60     10599960.19
#Sta/Elev= 30
  4230.8  393.69  4369.5  384.10  4462.5  377.66  4472.6  375.50  4596.1  370.88
  4633.9  368.26  4641.0  366.42  4643.7  365.92  4647.0  366.42  4671.7  368.62
  4714.5  369.18  4805.2  367.64  4815.3  369.06  4946.3  369.75  4976.5  369.66
  4994.2  366.44  4999.2  368.86  5006.8  366.66  5026.9  369.69  5077.0  368.49
  5109.6  369.89  5223.0  376.29  5278.2  381.55  5283.5  380.25  5314.7  380.50
  5369.0  382.84  5393.9  384.55  5410.8  390.49  5418.8  391.47  5464.2  392.71
#Mann=5,-1,0
  4230.8    0.16       0  4369.5    0.12       0  4641.0    0.07       0
  4647.0    0.12       0  5109.6    0.05       0
Bank Sta=4641,4647
Exp/Cntr=0.3,0.1