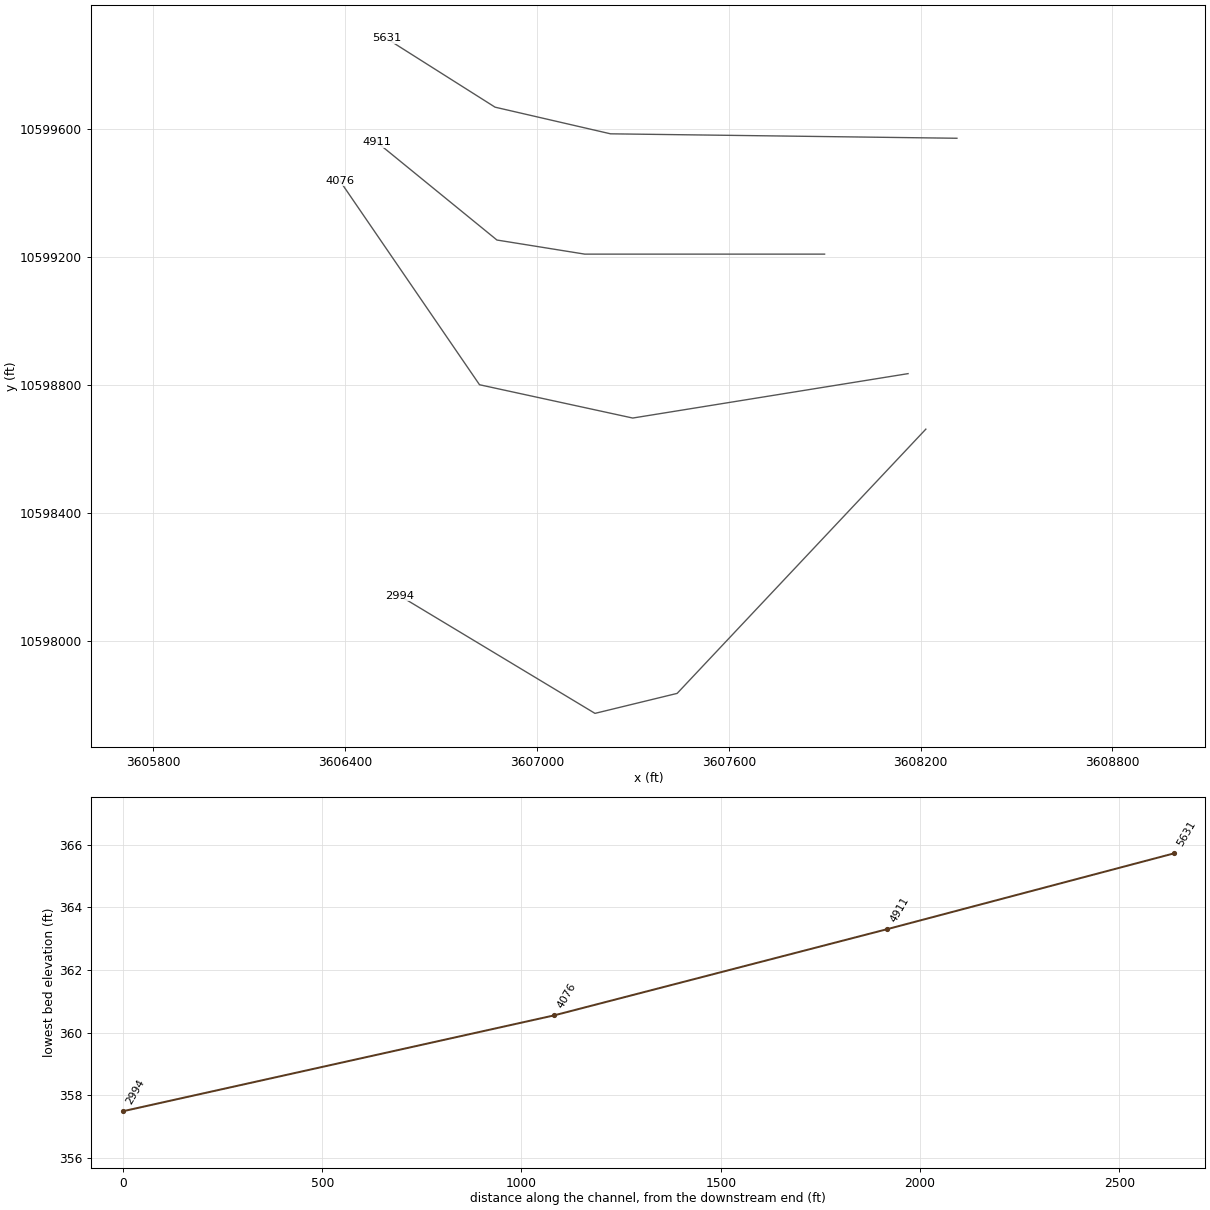
HEC-RAS study UNT 066 IN UKCR.prj: UNT 066 IN UKCR Base Level Engineering

--- UNT 066 IN UKCR.g01 (geometry) --- (continued)

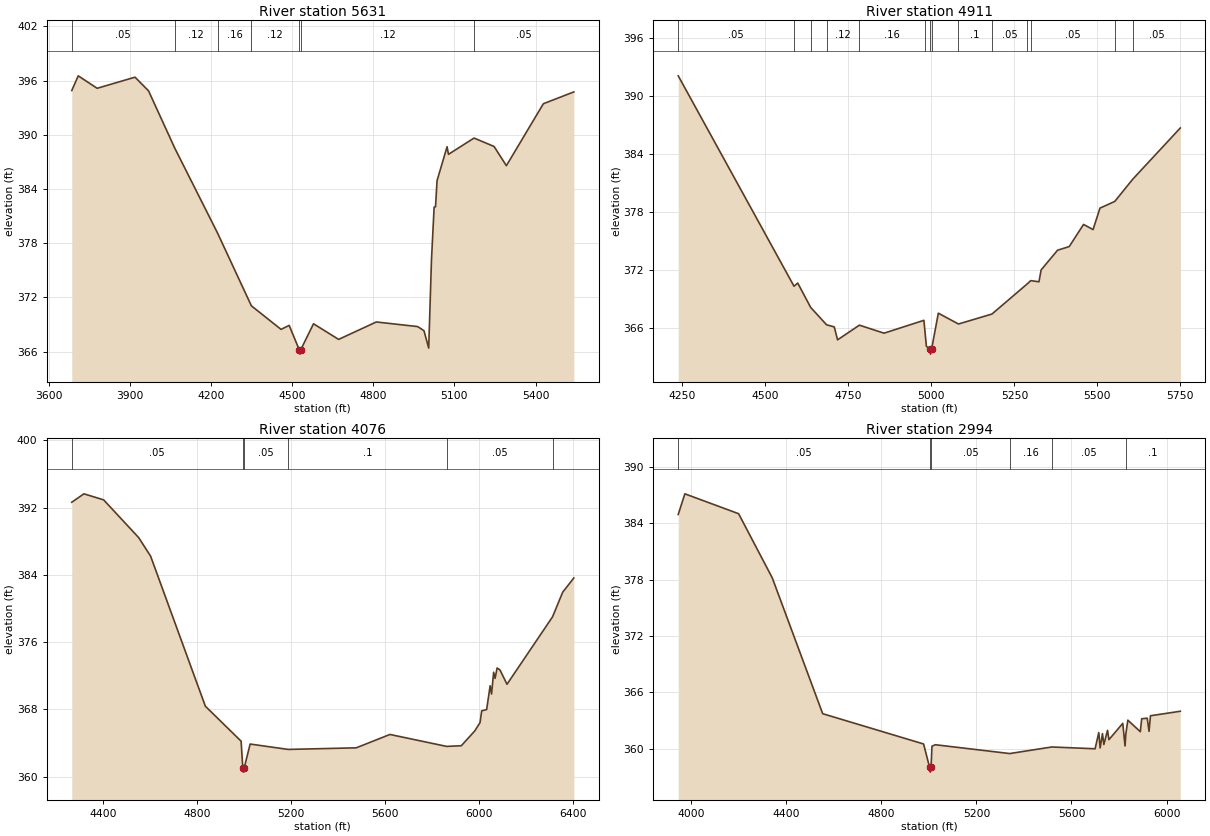
Type RM Length L Ch R = 1,5631,720,720,720
BEGIN DESCRIPTION:
UNT 066 IN UKCR 3.0
END DESCRIPTION:
XS GIS Cut Line= 4
      3608313.51     10599572.56      3607230.15     10599586.45
      3606869.04     10599669.79      3606528.77     10599885.06
#Sta/Elev= 30
  3685.0  394.90  3708.9  396.53  3778.9  395.15  3918.9  396.38  3968.9  394.87
  4065.5  388.55  4224.0  379.13  4349.2  371.07  4459.0  368.46  4489.0  368.90
  4526.0  366.22  4528.7  365.72  4532.0  366.22  4579.0  369.08  4671.9  367.35
  4811.2  369.28  4964.0  368.77  4987.4  368.32  5005.0  366.39  5015.3  376.22
  5025.0  381.99  5030.2  382.03  5035.8  384.92  5072.9  388.68  5078.1  387.84
  5172.6  389.64  5246.7  388.71  5292.2  386.58  5429.0  393.44  5541.7  394.75
#Mann=7,-1,0
  3685.0    0.05       0  4065.5    0.12       0  4224.0    0.16       0
  4349.2    0.12       0  4526.0    0.07       0  4532.0    0.12       0
  5172.6    0.05       0
Bank Sta=4526,4532
Exp/Cntr=0.3,0.1

Type RM Length L Ch R = 1,4911,835,835,835
BEGIN DESCRIPTION:
UNT 066 IN UKCR 2.0
END DESCRIPTION:
XS GIS Cut Line= 4
      3607899.62     10599210.19      3607149.61     10599210.19
      3606874.92     10599254.28      3606499.62     10599560.18
#Sta/Elev= 30
  4237.3  392.12  4586.1  370.33  4597.3  370.66  4636.2  368.14  4684.1  366.34
  4707.3  366.12  4717.3  364.78  4783.0  366.30  4857.3  365.47  4977.3  366.80
  4980.8  365.55  4984.8  364.12  4994.4  363.80  4997.2  363.30  5000.4  363.80
  5020.8  367.54  5081.5  366.42  5182.3  367.45  5288.5  370.57  5299.1  370.91
  5323.9  370.79  5330.4  372.02  5379.9  374.06  5415.1  374.44  5458.2  376.73
  5486.9  376.20  5507.7  378.42  5552.2  379.11  5606.3  381.41  5749.7  386.72
#Mann=14,-1,0
  4237.3    0.05       0  4586.1    0.12       0  4636.2    0.05       0
  4684.1    0.12       0  4783.0    0.16       0  4980.8    0.05       0
  4994.4    0.03       0  5000.4    0.05       0  5081.5     0.1       0
  5182.3    0.05       0  5288.5     0.1       0  5299.1    0.05       0
  5552.2    0.08       0  5606.3    0.05       0
Bank Sta=4994.4,5000.4
Exp/Cntr=0.3,0.1

Type RM Length L Ch R = 1,4076,1082,1082,1082
BEGIN DESCRIPTION:
Mapping XS 03ac89bb
END DESCRIPTION:
XS GIS Cut Line= 4
      3608160.67     10598836.45      3607299.59     10598697.56
      3606820.42     10598801.73      3606383.77     10599439.39
#Sta/Elev= 30
  4267.8  392.65  4319.5  393.65  4403.5  392.93  4552.5  388.44  4603.1  386.24
  4836.0  368.39  4988.1  364.23  4995.2  361.05  4997.9  360.55  5001.2  361.05
  5026.4  363.89  5188.5  363.25  5477.7  363.44  5621.0  365.03  5862.1  363.61
  5924.6  363.69  5981.5  365.44  6004.2  366.44  6011.3  367.84  6032.3  367.99
  6047.2  370.82  6053.2  369.84  6062.1  372.43  6068.2  371.70  6076.9  372.94
  6089.1  372.70  6118.9  371.00  6312.6  379.02  6355.7  381.95  6403.2  383.64
#Mann=6,-1,0
  4267.8    0.05       0  4995.2    0.03       0  5001.2    0.05       0
  5188.5     0.1       0  5862.1    0.05       0  6312.6    0.08       0
Bank Sta=4995.2,5001.2
Exp/Cntr=0.3,0.1

Type RM Length L Ch R = 1,2994,0,0,0
BEGIN DESCRIPTION:
UNT 066 IN UKCR 1.0
END DESCRIPTION:
XS GIS Cut Line= 4
      3608216.25     10598662.84      3607438.48     10597836.45
      3607181.54     10597773.95      3606570.38     10598142.03
#Sta/Elev= 30
  3945.4  384.96  3973.3  387.16  4199.5  385.04  4341.1  378.20  4553.3  363.72
  4977.9  360.49  5003.2  357.99  5006.0  357.49  5009.2  357.99  5013.1  360.25
  5027.3  360.41  5340.4  359.47  5516.9  360.17  5699.5  359.98  5715.0  361.71
  5720.8  360.07  5730.5  361.60  5736.3  360.43  5751.9  361.95  5757.7  360.95
  5816.0  362.69  5825.5  360.28  5828.9  361.55  5837.3  363.03  5889.8  361.80
  5895.6  363.18  5918.9  363.24  5926.6  361.84  5932.5  363.50  6058.1  363.98
#Mann=6,-1,0
  3945.4    0.05       0  5003.2    0.03       0  5009.2    0.05       0
  5340.4    0.16       0  5516.9    0.05       0  5828.9     0.1       0
Bank Sta=5003.2,5009.2
Exp/Cntr=0.3,0.1

Chan Stop Cuts=-1