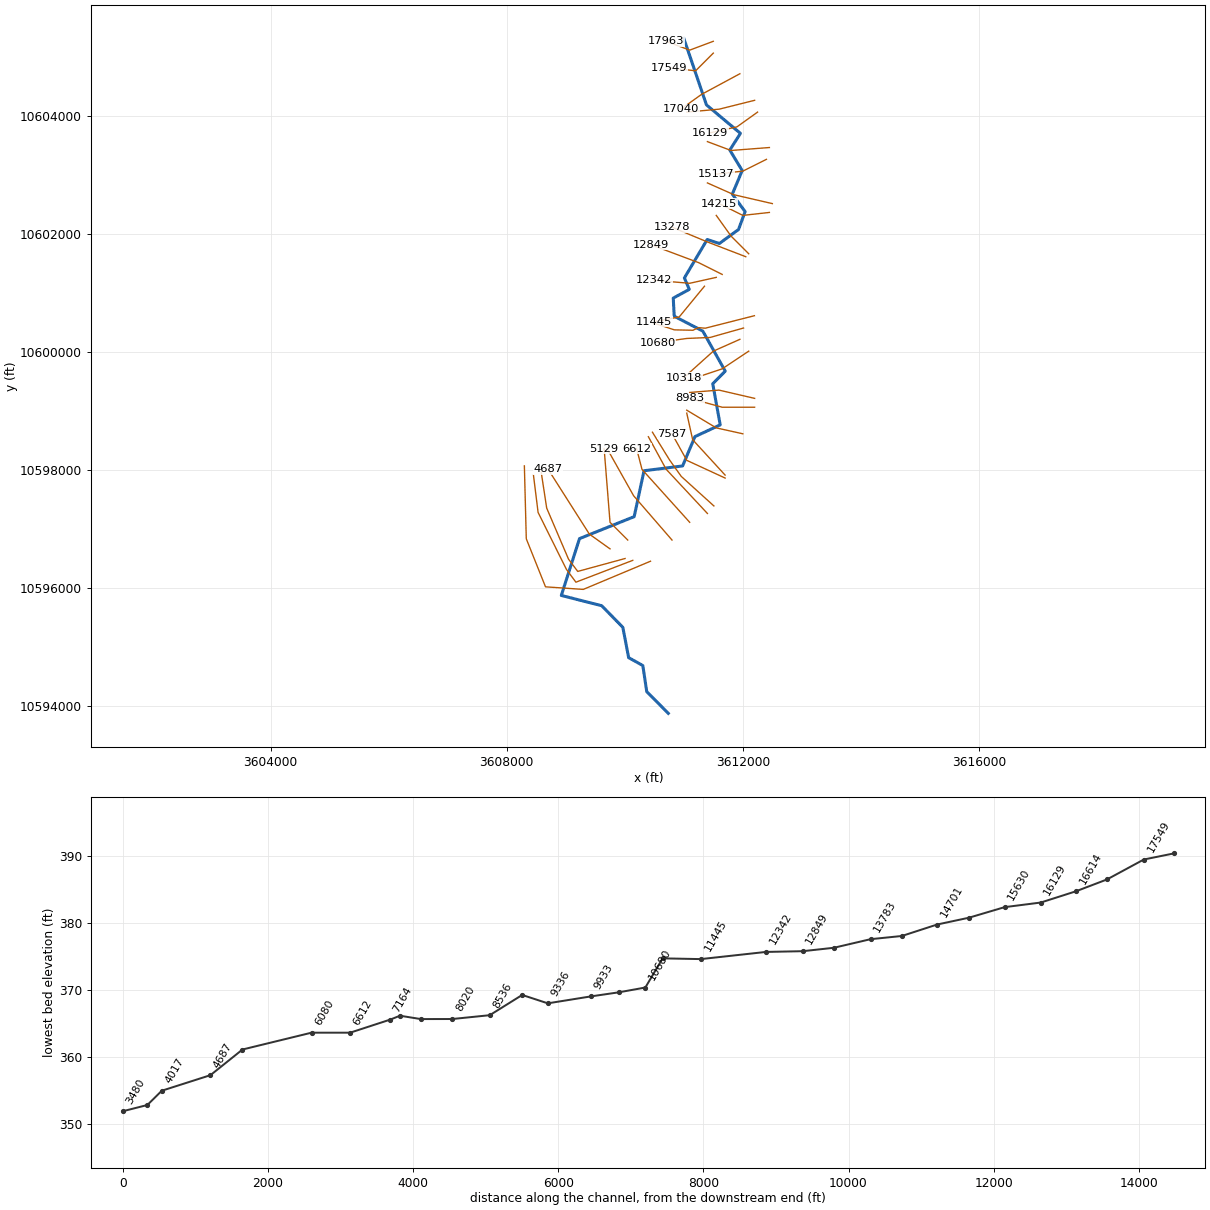
--- UNT 067 IN UKCR.prj (project) ---

Proj Title=UNT 067 IN UKCR Base Level Engineering
Current Plan=p01
Default Exp/Contr=0.3,0.1
English Units
Geom File=g01
Flow File=f01
Plan File=p01
BEGIN DESCRIPTION:
UNT 067 IN UKCR
END DESCRIPTION:

--- UNT 067 IN UKCR.p01 (plan) ---

Plan Title=Multiple Run
Short Identifier=Multiple
Geom File=g01
Flow File=f01
Subcritical Flow
K Sum by GR= 0
Std Step Tol= 0.01
Critical Tol= 0.01
Num of Std Step Trials= 20
Max Error Tol= 0.3
Flow Tol Ratio= 0.001
Split Flow NTrial= 30
Split Flow Tol= 0.02
Split Flow Ratio= 0.02
Log Output Level= 0
Friction Slope Method= 1
Unsteady Friction Slope Method= 2
Unsteady Bridges Friction Slope Method= 1
Parabolic Critical Depth
Global Vel Dist=  1 , 1 , 1
Global Log Level= 0
CheckData=True
Encroach Param= -1, 0, 0, 0
BEGIN DESCRIPTION:
Multiple Run
END DESCRIPTION:

--- UNT 067 IN UKCR.f01 (steady flow) ---

Flow Title=Multiple
Number of Profiles=7
Profile Names=10-year,25-year,50-year,1pct_min,100-year,1pct_plu,500-year
River Rch & RM= UNT 067 IN UKCR,Reach-1,17963
    1535    2143    2652    2392    3235    4374    4796
River Rch & RM= UNT 067 IN UKCR,Reach-1,10680
    2074    2931    3656    3319    4489    6070    6748
Boundary for River Rch & Prof#=UNT 067 IN UKCR,Reach-1,1
Up Type=0
Dn Type=3
Dn Slope=0.005
Boundary for River Rch & Prof#=UNT 067 IN UKCR,Reach-1,2
Up Type=0
Dn Type=3
Dn Slope=0.005
Boundary for River Rch & Prof#=UNT 067 IN UKCR,Reach-1,3
Up Type=0
Dn Type=3
Dn Slope=0.005
Boundary for River Rch & Prof#=UNT 067 IN UKCR,Reach-1,4
Up Type=0
Dn Type=3
Dn Slope=0.005
Boundary for River Rch & Prof#=UNT 067 IN UKCR,Reach-1,5
Up Type=0
Dn Type=3
Dn Slope=0.005
Boundary for River Rch & Prof#=UNT 067 IN UKCR,Reach-1,6
Up Type=0
Dn Type=3
Dn Slope=0.005
Boundary for River Rch & Prof#=UNT 067 IN UKCR,Reach-1,7
Up Type=0
Dn Type=3
Dn Slope=0.005

--- UNT 067 IN UKCR.g01 (geometry) ---

Geom Title=Existing Conditions

River Reach=UNT 067 IN UKCR,Reach-1
Reach XY= 30
      3610999.61     10605310.19      3611383.75     10604182.00
      3611959.00     10603700.00      3611779.00     10603417.00
      3611989.00     10603070.00      3611821.25     10602670.00
      3612038.25     10602374.00      3611926.75     10602071.00
      3611602.25     10601834.00      3611396.00     10601902.00
      3611009.50     10601250.00      3611092.75     10601057.00
      3610820.75     10600909.00      3610837.25     10600602.00
      3611321.75     10600350.00      3611701.50     10599671.00
      3611490.00     10599458.00      3611616.25     10598761.00
      3611188.25     10598562.00      3610979.25     10598065.00
      3610325.50     10597984.00      3610158.75     10597206.00
      3609232.50     10596834.00      3608924.25     10595871.00
      3609608.25     10595697.00      3609966.50     10595331.00
      3610065.25     10594817.00      3610305.25     10594683.00
      3610372.00     10594241.00      3610737.25     10593873.00

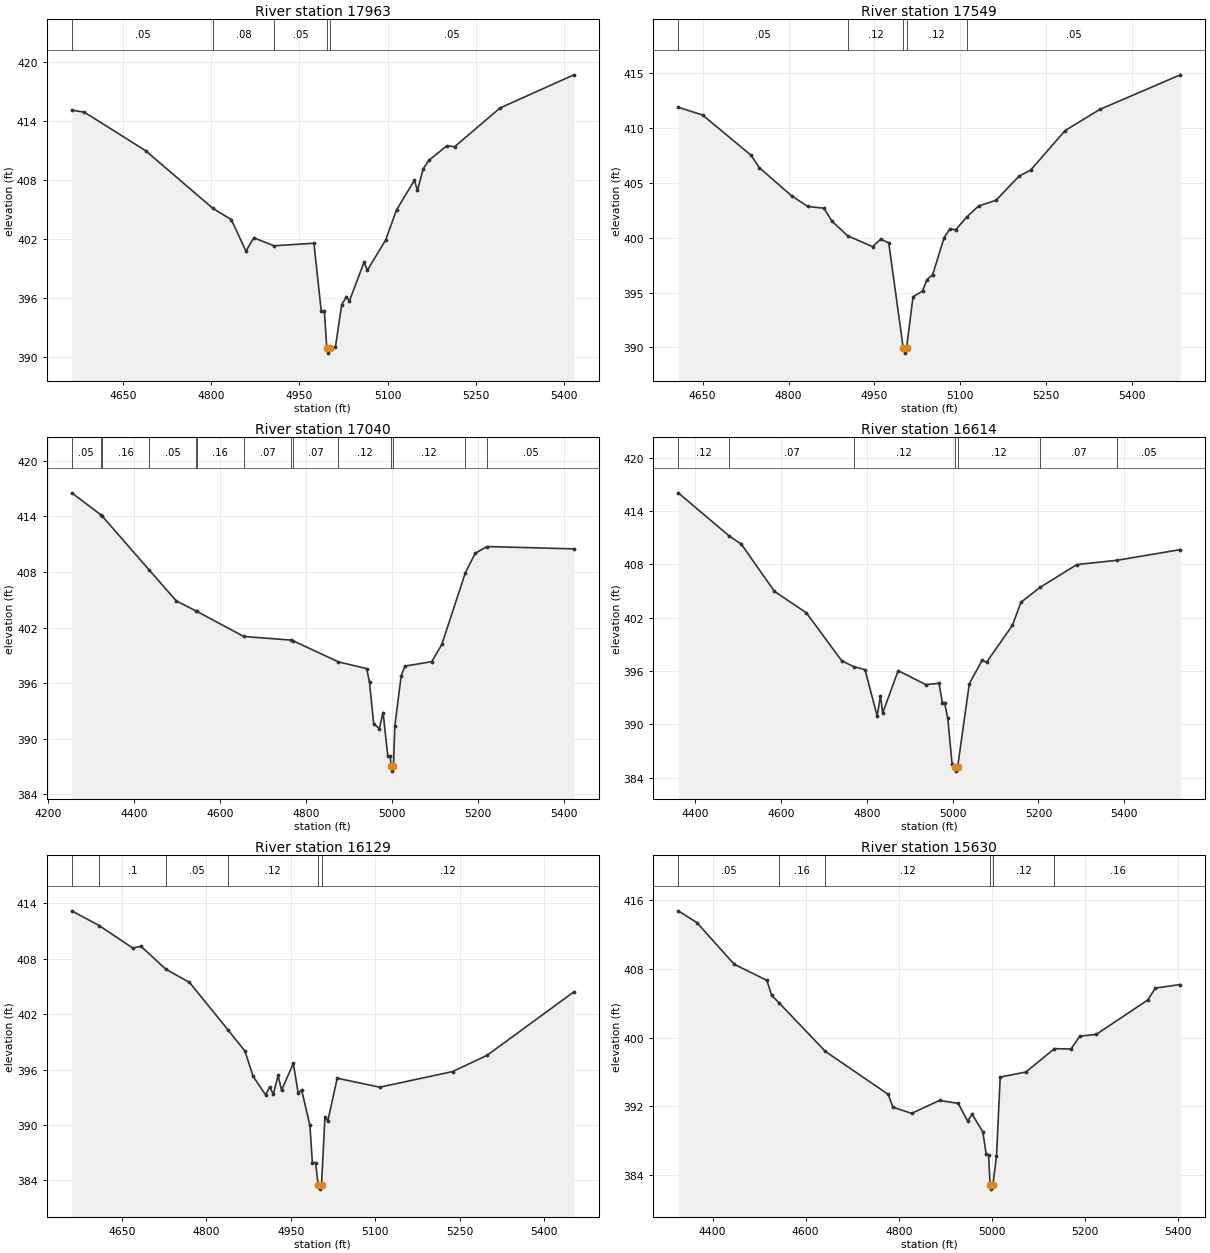
Type RM Length L Ch R = 1,17963,414,414,414
BEGIN DESCRIPTION:
UNT 067 IN UKCR 29.0
END DESCRIPTION:
XS GIS Cut Line= 3
      3611499.64     10605260.20      3611099.61     10605110.19
      3610699.64     10605260.18
#Sta/Elev= 30
  4562.5  415.11  4583.9  414.90  4688.0  410.99  4802.6  405.12  4834.0  403.97
  4858.9  400.77  4872.3  402.12  4906.7  401.31  4974.6  401.57  4987.1  394.63
  4992.4  394.63  4996.5  390.89  4999.3  390.39  5002.5  390.89  5011.1  390.97
  5021.8  395.32  5029.8  396.10  5035.1  395.72  5060.0  399.66  5065.4  398.81
  5096.5  401.88  5115.2  404.96  5145.5  407.97  5150.8  406.95  5160.6  409.15
  5170.4  410.01  5200.7  411.48  5214.0  411.39  5291.4  415.33  5416.9  418.70
#Mann=5,-1,0
  4562.5    0.05       0  4802.6    0.08       0  4906.7    0.05       0
  4996.5    0.03       0  5002.5    0.05       0
Bank Sta=4996.5,5002.5
Exp/Cntr=0.3,0.1

Type RM Length L Ch R = 1,17549,509,509,509
BEGIN DESCRIPTION:
UNT 067 IN UKCR 28.0
END DESCRIPTION:
XS GIS Cut Line= 3
      3611499.59     10605060.16      3611199.61     10604760.19
      3610749.61     10604810.19
#Sta/Elev= 30
  4607.3  411.89  4649.7  411.19  4734.5  407.52  4748.7  406.40  4805.3  403.82
  4833.5  402.85  4861.8  402.69  4876.0  401.50  4903.4  400.17  4946.7  399.19
  4960.8  399.86  4975.0  399.53  5000.2  389.98  5003.0  389.48  5006.2  389.98
  5017.4  394.61  5034.0  395.14  5041.6  396.18  5051.7  396.63  5071.8  400.02
  5081.8  400.81  5091.9  400.72  5111.2  401.89  5132.1  402.90  5162.3  403.41
  5202.6  405.61  5222.7  406.16  5283.1  409.77  5343.4  411.69  5484.3  414.85
#Mann=5,-1,0
  4607.3    0.05       0  4903.4    0.12       0  5000.2    0.07       0
  5006.2    0.12       0  5111.2    0.05       0
Bank Sta=5000.2,5006.2
Exp/Cntr=0.3,0.1

Type RM Length L Ch R = 1,17040,426,426,426
BEGIN DESCRIPTION:
UNT 067 IN UKCR 27.0
END DESCRIPTION:
XS GIS Cut Line= 3
      3611949.58     10604710.17      3611299.61     10604360.19
      3610949.63     10604110.20
#Sta/Elev= 30
  4255.1  416.55  4322.7  414.18  4325.2  414.08  4435.2  408.22  4498.4  404.88
  4545.2  403.77  4545.8  403.76  4655.2  401.04  4765.3  400.65  4768.9  400.60
  4875.3  398.30  4941.4  397.57  4947.9  396.07  4957.6  391.64  4970.6  391.09
  4979.5  392.83  4990.5  388.11  4996.4  388.11  4997.7  387.00  5000.4  386.50
  5003.7  387.00  5006.8  391.36  5021.6  396.79  5030.2  397.84  5092.8  398.32
  5116.2  400.18  5170.7  407.88  5193.6  410.01  5221.2  410.75  5423.4  410.50
#Mann=14,-1,0
  4255.1    0.05       0  4322.7    0.12       0  4325.2    0.16       0
  4435.2    0.05       0  4545.2    0.07       0  4545.8    0.16       0
  4655.2    0.07       0  4765.3    0.12       0  4768.9    0.07       0
  4875.3    0.12       0  4997.7    0.07       0  5003.7    0.12       0
  5170.7    0.07       0  5221.2    0.05       0
Bank Sta=4997.7,5003.7
Exp/Cntr=0.3,0.1

Type RM Length L Ch R = 1,16614,485,485,485
BEGIN DESCRIPTION:
UNT 067 IN UKCR 26.0
END DESCRIPTION:
XS GIS Cut Line= 3
      3612199.58     10604260.18      3611599.61     10604110.19
      3611049.61     10604060.19
#Sta/Elev= 30
  4360.0  416.06  4478.9  411.20  4506.9  410.30  4584.2  404.98  4658.9  402.55
  4741.4  397.15  4768.9  396.51  4795.5  396.16  4823.8  390.95  4831.6  393.24
  4836.7  391.29  4872.8  396.05  4937.2  394.48  4968.1  394.62  4975.9  392.46
  4980.9  392.46  4988.5  390.71  4998.5  385.54  5005.6  385.24  5008.3  384.74
  5011.6  385.24  5038.7  394.58  5068.8  397.24  5078.8  396.98  5139.1  401.14
  5159.2  403.75  5204.0  405.43  5289.7  407.99  5382.2  408.46  5530.7  409.67
#Mann=7,-1,0
  4360.0    0.12       0  4478.9    0.07       0  4768.9    0.12       0
  5005.6    0.07       0  5011.6    0.12       0  5204.0    0.07       0
  5382.2    0.05       0
Bank Sta=5005.6,5011.6
Exp/Cntr=0.3,0.1

Type RM Length L Ch R = 1,16129,499,499,499
BEGIN DESCRIPTION:
UNT 067 IN UKCR 25.0
END DESCRIPTION:
XS GIS Cut Line= 3
      3612249.60     10604060.18      3611899.61     10603810.19
      3611449.59     10603710.18
#Sta/Elev= 30
  4561.1  413.17  4609.9  411.57  4669.2  409.15  4684.0  409.33  4728.1  406.85
  4770.0  405.43  4838.9  400.25  4868.3  398.01  4883.1  395.25  4905.2  393.25
  4912.6  394.15  4918.7  393.30  4927.3  395.36  4933.4  393.76  4954.3  396.66
  4962.9  393.48  4969.1  393.78  4983.8  389.95  4988.1  385.93  4993.8  385.93
  4998.4  383.56  5001.2  383.06  5004.4  383.56  5010.4  390.85  5015.5  390.43
  5032.2  395.06  5107.7  394.09  5237.1  395.78  5298.5  397.55  5452.2  404.40
#Mann=6,-1,0
  4561.1    0.05       0  4609.9     0.1       0  4728.1    0.05       0
  4838.9    0.12       0  4998.4    0.07       0  5004.4    0.12       0
Bank Sta=4998.4,5004.4
Exp/Cntr=0.3,0.1

Type RM Length L Ch R = 1,15630,493,493,493
BEGIN DESCRIPTION:
UNT 067 IN UKCR 24.0
END DESCRIPTION:
XS GIS Cut Line= 3
      3612449.63     10603460.19      3611799.61     10603410.19
      3611399.64     10603560.18
#Sta/Elev= 30
  4326.1  414.74  4366.2  413.37  4446.5  408.52  4516.7  406.65  4526.7  404.93
  4543.4  404.00  4642.3  398.39  4777.4  393.39  4787.5  391.91  4827.6  391.18
  4887.8  392.69  4927.9  392.34  4947.9  390.31  4958.0  391.06  4980.7  389.05
  4987.8  386.51  4993.2  386.33  4996.4  382.87  4999.1  382.37  5002.4  382.87
  5010.1  386.17  5018.1  395.40  5073.3  395.99  5134.7  398.71  5170.3  398.67
  5189.0  400.15  5224.6  400.37  5334.9  404.36  5351.8  405.76  5405.2  406.17
#Mann=6,-1,0
  4326.1    0.05       0  4543.4    0.16       0  4642.3    0.12       0
  4996.4    0.07       0  5002.4    0.12       0  5134.7    0.16       0
Bank Sta=4996.4,5002.4
Exp/Cntr=0.3,0.1

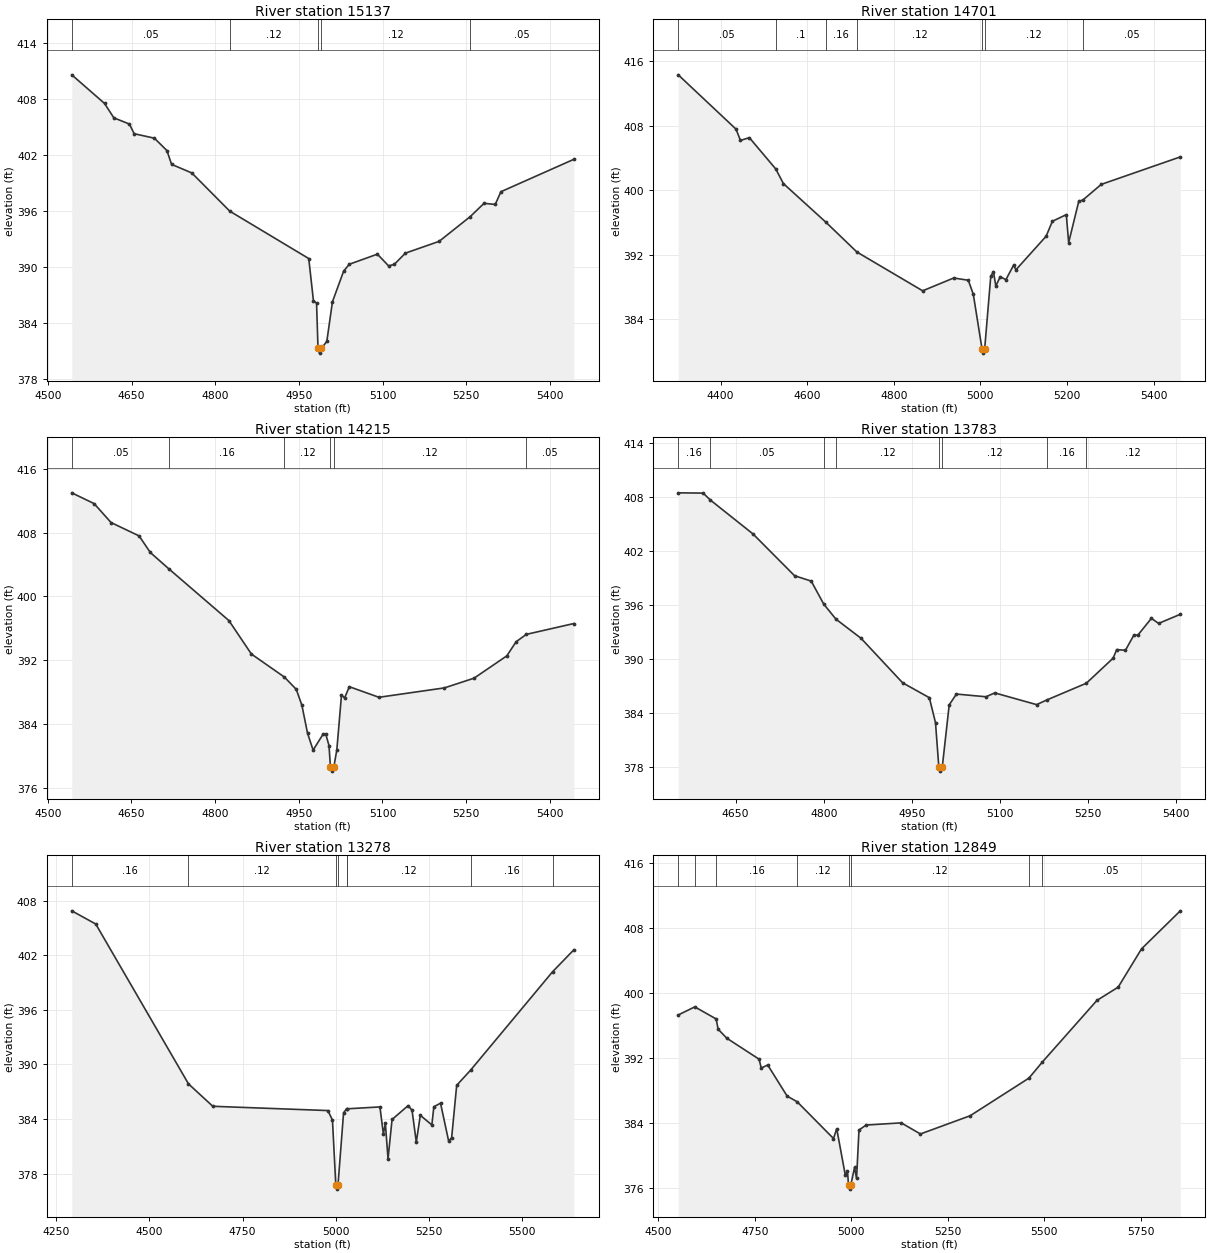
Type RM Length L Ch R = 1,15137,436,436,436
BEGIN DESCRIPTION:
UNT 067 IN UKCR 23.0
END DESCRIPTION:
XS GIS Cut Line= 3
      3612399.58     10603260.18      3611999.61     10603060.19
      3611549.56     10603010.18
#Sta/Elev= 30
  4542.8  410.57  4601.5  407.51  4618.2  405.97  4646.2  405.30  4654.6  404.27
  4690.9  403.79  4713.3  402.47  4721.7  400.99  4758.0  400.07  4826.1  395.98
  4967.6  390.91  4976.0  386.40  4981.6  386.14  4984.2  381.29  4986.9  380.79
  4990.2  381.29  5000.0  382.05  5010.1  386.29  5030.2  389.57  5040.3  390.30
  5090.6  391.38  5110.7  390.13  5120.8  390.28  5140.9  391.49  5201.3  392.75
  5257.1  395.40  5281.8  396.82  5301.9  396.70  5312.0  398.06  5442.8  401.53
#Mann=5,-1,0
  4542.8    0.05       0  4826.1    0.12       0  4984.2    0.07       0
  4990.2    0.12       0  5257.1    0.05       0
Bank Sta=4984.2,4990.2
Exp/Cntr=0.3,0.1

Type RM Length L Ch R = 1,14701,486,486,486
BEGIN DESCRIPTION:
UNT 067 IN UKCR 22.0
END DESCRIPTION:
XS GIS Cut Line= 3
      3612499.65     10602510.18      3611849.61     10602660.19
      3611399.58     10602860.20
#Sta/Elev= 30
  4302.2  414.30  4435.7  407.56  4445.9  406.16  4466.4  406.51  4527.5  402.62
  4545.1  400.81  4643.0  396.03  4714.9  392.32  4866.7  387.51  4938.5  389.10
  4972.1  388.82  4983.7  387.08  5003.9  380.28  5006.7  379.78  5009.9  380.28
  5024.0  389.30  5030.2  389.89  5035.7  388.10  5045.9  389.26  5058.9  388.89
  5076.7  390.68  5082.2  390.12  5151.9  394.28  5166.3  396.13  5198.5  396.96
  5203.9  393.49  5227.2  398.60  5236.9  398.78  5279.2  400.71  5461.8  404.12
#Mann=7,-1,0
  4302.2    0.05       0  4527.5     0.1       0  4643.0    0.16       0
  4714.9    0.12       0  5003.9    0.07       0  5009.9    0.12       0
  5236.9    0.05       0
Bank Sta=5003.9,5009.9
Exp/Cntr=0.3,0.1

Type RM Length L Ch R = 1,14215,432,432,432
BEGIN DESCRIPTION:
UNT 067 IN UKCR 21.0
END DESCRIPTION:
XS GIS Cut Line= 3
      3612449.59     10602360.19      3611999.61     10602310.19
      3611599.57     10602510.21
#Sta/Elev= 30
  4543.0  413.01  4583.2  411.65  4613.4  409.28  4663.7  407.60  4683.8  405.52
  4717.6  403.43  4824.7  396.97  4865.0  392.77  4924.1  389.88  4945.4  388.34
  4955.5  386.34  4965.6  382.84  4975.6  380.71  4993.2  382.67  4998.5  382.67
  5004.1  381.28  5006.7  378.57  5009.5  378.07  5012.7  378.57  5018.1  380.72
  5026.5  387.62  5032.1  387.26  5040.5  388.67  5093.6  387.34  5211.0  388.52
  5264.1  389.74  5322.8  392.54  5339.5  394.31  5357.8  395.24  5443.0  396.60
#Mann=6,-1,0
  4543.0    0.05       0  4717.6    0.16       0  4924.1    0.12       0
  5006.7    0.07       0  5012.7    0.12       0  5357.8    0.05       0
Bank Sta=5006.7,5012.7
Exp/Cntr=0.3,0.1

Type RM Length L Ch R = 1,13783,505,505,505
BEGIN DESCRIPTION:
UNT 067 IN UKCR 20.0
END DESCRIPTION:
XS GIS Cut Line= 3
      3612099.61     10601660.18      3611799.61     10601960.19
      3611549.60     10602310.20
#Sta/Elev= 30
  4552.3  408.43  4594.7  408.40  4606.8  407.64  4679.6  403.87  4750.3  399.24
  4778.6  398.65  4799.9  396.10  4820.7  394.43  4863.4  392.31  4934.1  387.38
  4979.6  385.73  4990.1  382.96  4995.7  378.09  4998.4  377.59  5001.7  378.09
  5013.4  384.93  5025.7  386.13  5076.1  385.83  5090.9  386.26  5162.1  384.96
  5180.4  385.50  5246.8  387.33  5292.4  390.11  5298.5  391.06  5313.3  390.98
  5328.0  392.70  5334.2  392.64  5357.5  394.52  5369.8  393.96  5406.7  394.97
#Mann=8,-1,0
  4552.3    0.16       0  4606.8    0.05       0  4799.9    0.16       0
  4820.7    0.12       0  4995.7    0.07       0  5001.7    0.12       0
  5180.4    0.16       0  5246.8    0.12       0
Bank Sta=4995.7,5001.7
Exp/Cntr=0.3,0.1

Type RM Length L Ch R = 1,13278,429,429,429
BEGIN DESCRIPTION:
UNT 067 IN UKCR 19.0
END DESCRIPTION:
XS GIS Cut Line= 3
      3612049.59     10601610.19      3611399.61     10601860.19
      3610799.61     10602110.19
#Sta/Elev= 30
  4291.7  406.88  4356.0  405.43  4604.7  387.87  4669.9  385.41  4978.5  384.94
  4990.8  383.89  4999.7  376.81  5002.5  376.31  5005.7  376.81  5020.6  384.70
  5028.5  385.12  5029.1  385.13  5118.1  385.34  5127.3  382.38  5132.7  383.52
  5139.8  379.63  5150.6  383.96  5193.9  385.49  5204.2  384.97  5215.6  381.48
  5226.4  384.42  5257.3  383.36  5262.7  385.36  5280.6  385.75  5302.3  381.60
  5310.4  381.95  5323.9  387.71  5361.0  389.37  5580.9  400.18  5638.1  402.60
#Mann=8,-1,0
  4291.7    0.16       0  4604.7    0.12       0  4999.7    0.07       0
  5005.7    0.12       0  5028.5    0.16       0  5029.1    0.12       0
  5361.0    0.16       0  5580.9    0.05       0
Bank Sta=4999.7,5005.7
Exp/Cntr=0.3,0.1

Type RM Length L Ch R = 1,12849,507,507,507
BEGIN DESCRIPTION:
UNT 067 IN UKCR 18.0
END DESCRIPTION:
XS GIS Cut Line= 3
      3611649.60     10601310.19      3611249.61     10601510.19
      3610449.61     10601810.19
#Sta/Elev= 30
  4551.4  397.27  4594.3  398.27  4649.7  396.78  4654.8  395.52  4677.2  394.41
  4761.0  391.82  4766.6  390.73  4783.4  391.10  4833.7  387.27  4859.7  386.57
  4953.9  382.04  4962.3  383.24  4984.6  377.50  4990.2  378.02  4992.8  376.30
  4995.6  375.80  4998.8  376.30  5008.4  378.47  5013.7  377.13  5020.0  383.09
  5038.6  383.70  5129.4  383.97  5179.3  382.60  5308.3  384.85  5460.7  389.49
  5495.0  391.45  5636.7  399.06  5691.9  400.70  5752.4  405.42  5853.0  410.11
#Mann=8,-1,0
  4551.4    0.16       0  4594.3    0.12       0  4649.7    0.16       0
  4859.7    0.12       0  4992.8    0.07       0  4998.8    0.12       0
  5460.7    0.07       0  5495.0    0.05       0
Bank Sta=4992.8,4998.8
Exp/Cntr=0.3,0.1

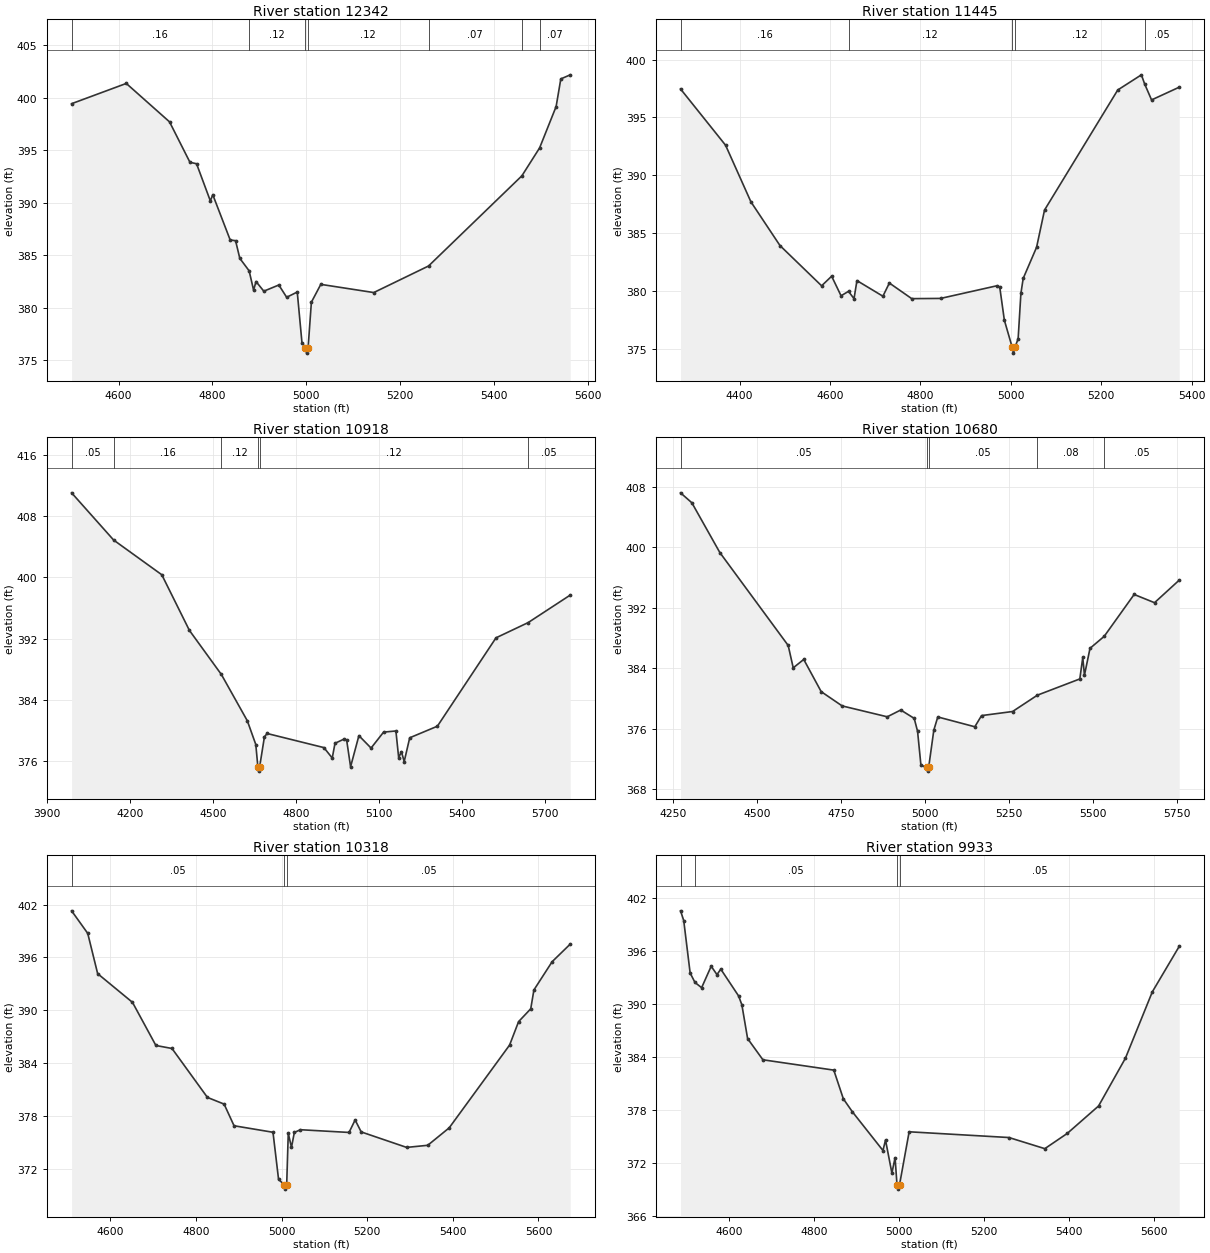
Type RM Length L Ch R = 1,12342,897,897,897
BEGIN DESCRIPTION:
UNT 067 IN UKCR 17.0
END DESCRIPTION:
XS GIS Cut Line= 3
      3611549.65     10601260.20      3611099.61     10601160.19
      3610499.61     10601210.19
#Sta/Elev= 30
  4499.8  399.45  4616.4  401.38  4708.6  397.72  4752.1  393.87  4766.2  393.73
  4795.6  390.19  4800.8  390.78  4837.9  386.47  4849.4  386.40  4858.4  384.72
  4878.3  383.53  4887.8  381.69  4893.0  382.51  4909.6  381.59  4941.6  382.18
  4958.3  381.01  4980.9  381.51  4990.9  376.70  4998.0  376.19  5000.7  375.69
  5004.0  376.19  5011.0  380.54  5031.1  382.24  5144.0  381.46  5260.8  383.99
  5459.8  392.58  5497.6  395.24  5532.8  399.18  5542.8  401.81  5562.9  402.20
#Mann=7,-1,0
  4499.8    0.16       0  4878.3    0.12       0  4998.0    0.07       0
  5004.0    0.12       0  5260.8    0.07       0  5459.8    0.12       0
  5497.6    0.07       0
Bank Sta=4998,5004
Exp/Cntr=0.3,0.1

Type RM Length L Ch R = 1,11445,527,527,527
BEGIN DESCRIPTION:
UNT 067 IN UKCR 16.0
END DESCRIPTION:
XS GIS Cut Line= 3
      3611349.60     10601110.17      3610922.29     10600590.28
      3610499.58     10600510.18
#Sta/Elev= 30
  4269.3  397.46  4369.0  392.59  4425.0  387.70  4489.3  383.92  4581.4  380.44
  4603.6  381.27  4624.4  379.58  4640.9  379.96  4653.1  379.33  4659.6  380.89
  4717.0  379.54  4731.3  380.68  4780.8  379.33  4844.7  379.35  4970.0  380.45
  4975.5  380.33  4985.7  377.47  5003.1  375.12  5005.8  374.62  5009.1  375.12
  5016.2  375.86  5022.3  379.78  5027.4  381.08  5057.0  383.77  5074.6  386.99
  5236.6  397.37  5288.9  398.68  5296.1  397.89  5311.4  396.51  5372.5  397.61
#Mann=5,-1,0
  4269.3    0.16       0  4640.9    0.12       0  5003.1    0.07       0
  5009.1    0.12       0  5296.1    0.05       0
Bank Sta=5003.1,5009.1
Exp/Cntr=0.3,0.1

Type RM Length L Ch R = 1,10918,238,238,238
BEGIN DESCRIPTION:
Mapping XS e1eba978
END DESCRIPTION:
XS GIS Cut Line= 6
      3612195.94     10600610.60      3611362.66     10600398.80
      3611248.07     10600409.22      3611154.32     10600364.08
      3610838.35     10600371.02      3610449.46     10600499.50
#Sta/Elev= 30
  3988.6  411.04  4140.7  404.88  4315.0  400.35  4414.8  393.10  4530.6  387.34
  4624.6  381.29  4655.2  378.20  4662.8  375.23  4665.6  374.73  4668.8  375.23
  4686.4  379.20  4696.1  379.64  4901.6  377.80  4931.8  376.44  4941.8  378.36
  4975.6  378.93  4983.9  378.79  4998.2  375.30  5028.3  379.36  5072.3  377.74
  5117.6  379.82  5162.2  379.97  5172.2  376.49  5182.2  377.27  5192.2  375.98
  5212.2  379.08  5312.3  380.59  5524.4  392.12  5640.8  394.11  5793.1  397.70
#Mann=6,-1,0
  3988.6    0.05       0  4140.7    0.16       0  4530.6    0.12       0
  4662.8    0.07       0  4668.8    0.12       0  5640.8    0.05       0
Bank Sta=4662.8,4668.8
Exp/Cntr=0.3,0.1

Type RM Length L Ch R = 1,10680,362,362,362
BEGIN DESCRIPTION:
UNT 067 IN UKCR 15.0
END DESCRIPTION:
XS GIS Cut Line= 4
      3612012.00     10600402.28      3611445.99     10600242.55
      3611050.16     10600225.19      3610557.05     10600155.74
#Sta/Elev= 30
  4273.0  407.21  4306.7  405.89  4389.8  399.31  4593.0  387.01  4608.0  384.05
  4639.2  385.16  4691.1  380.90  4753.4  379.01  4887.5  377.57  4927.6  378.47
  4967.6  377.36  4977.6  375.65  4987.6  371.16  5004.6  370.88  5007.4  370.38
  5010.6  370.88  5025.9  375.80  5037.7  377.55  5147.8  376.25  5167.8  377.73
  5260.1  378.27  5333.7  380.43  5459.9  382.58  5468.7  385.42  5473.7  383.08
  5490.2  386.63  5532.4  388.22  5621.4  393.76  5682.0  392.67  5755.3  395.65
#Mann=5,-1,0
  4273.0    0.05       0  5004.6    0.03       0  5010.6    0.05       0
  5333.7    0.08       0  5532.4    0.05       0
Bank Sta=5004.6,5010.6
Exp/Cntr=0.3,0.1

Type RM Length L Ch R = 1,10318,385,385,385
BEGIN DESCRIPTION:
UNT 067 IN UKCR 14.0
END DESCRIPTION:
XS GIS Cut Line= 3
      3611949.65     10600210.21      3611499.61     10600010.19
      3610999.58     10599560.17
#Sta/Elev= 30
  4509.1  401.29  4546.8  398.73  4570.0  394.15  4651.4  390.89  4706.1  385.99
  4743.7  385.65  4826.5  380.09  4865.5  379.33  4888.7  376.87  4979.7  376.13
  4992.7  370.79  5005.7  370.17  5008.4  369.67  5011.7  370.17  5015.4  376.02
  5022.9  374.41  5029.6  376.11  5043.8  376.42  5157.4  376.11  5171.6  377.53
  5185.8  376.17  5292.0  374.41  5341.3  374.65  5391.4  376.63  5532.6  386.04
  5553.6  388.70  5582.0  390.16  5589.4  392.30  5632.0  395.51  5674.3  397.51
#Mann=3,-1,0
  4509.1    0.05       0  5005.7    0.03       0  5011.7    0.05       0
Bank Sta=5005.7,5011.7
Exp/Cntr=0.3,0.1

Type RM Length L Ch R = 1,9933,597,597,597
BEGIN DESCRIPTION:
UNT 067 IN UKCR 13.0
END DESCRIPTION:
XS GIS Cut Line= 3
      3612099.64     10600010.21      3611649.61     10599710.19
      3611049.63     10599510.19
#Sta/Elev= 30
  4485.1  400.56  4492.6  399.46  4507.7  393.52  4519.1  392.45  4534.7  391.86
  4557.2  394.29  4570.8  393.34  4579.8  393.96  4621.8  390.92  4629.4  389.92
  4642.9  386.10  4678.9  383.70  4845.7  382.53  4868.2  379.28  4889.3  377.82
  4961.4  373.43  4967.4  374.62  4982.4  370.88  4989.9  372.62  4994.4  369.56
  4997.2  369.06  5000.4  369.56  5023.0  375.55  5257.9  374.90  5342.2  373.64
  5394.9  375.36  5468.7  378.47  5531.9  383.88  5595.2  391.39  5658.4  396.53
#Mann=4,-1,0
  4485.1     0.1       0  4519.1    0.05       0  4994.4    0.03       0
  5000.4    0.05       0
Bank Sta=4994.4,5000.4
Exp/Cntr=0.3,0.1

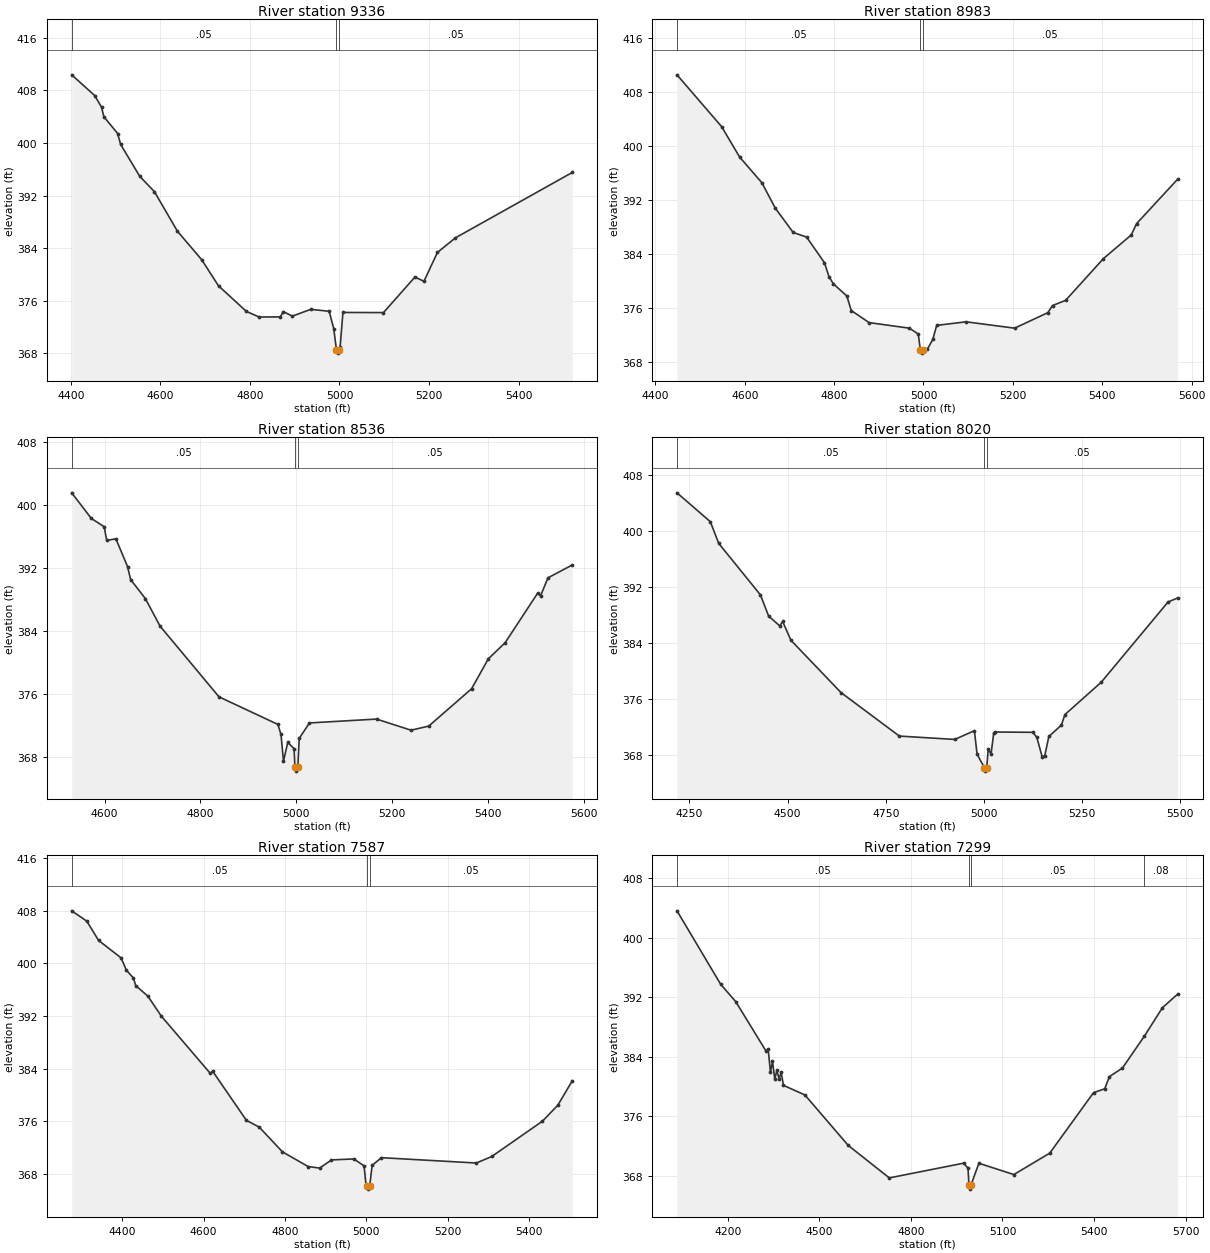
Type RM Length L Ch R = 1,9336,353,353,353
BEGIN DESCRIPTION:
UNT 067 IN UKCR 12.0
END DESCRIPTION:
XS GIS Cut Line= 3
      3612199.58     10599210.20      3611595.29     10599350.19
      3611099.60     10599310.19
#Sta/Elev= 30
  4402.1  410.37  4453.4  407.22  4468.7  405.46  4473.9  404.00  4504.7  401.44
  4511.3  399.79  4554.0  394.93  4586.8  392.59  4638.2  386.57  4692.3  382.24
  4729.9  378.26  4792.1  374.37  4820.4  373.52  4868.2  373.53  4874.3  374.35
  4894.8  373.65  4935.8  374.68  4976.9  374.39  4987.2  371.76  4993.3  368.52
  4996.0  368.02  4999.3  368.52  5001.4  368.88  5007.7  374.21  5098.3  374.19
  5168.5  379.60  5188.6  378.95  5218.7  383.34  5258.8  385.56  5519.7  395.51
#Mann=3,-1,0
  4402.1    0.05       0  4993.3    0.03       0  4999.3    0.05       0
Bank Sta=4993.3,4999.3
Exp/Cntr=0.3,0.1

Type RM Length L Ch R = 1,8983,447,447,447
BEGIN DESCRIPTION:
UNT 067 IN UKCR 11.0
END DESCRIPTION:
XS GIS Cut Line= 3
      3612199.65     10599060.19      3611649.61     10599060.19
      3611099.64     10599210.18
#Sta/Elev= 30
  4448.4  410.51  4548.4  402.82  4588.4  398.34  4638.4  394.51  4668.4  390.75
  4708.4  387.15  4738.4  386.47  4778.4  382.67  4788.4  380.62  4798.4  379.53
  4828.4  377.74  4838.4  375.58  4878.4  373.79  4968.4  372.97  4988.4  372.09
  4992.9  369.77  4995.7  369.27  4998.9  369.77  5008.8  369.86  5020.9  371.32
  5029.5  373.38  5095.2  373.91  5204.0  372.97  5278.3  375.27  5288.7  376.32
  5318.0  377.09  5402.7  383.28  5464.9  386.78  5477.0  388.47  5568.5  395.03
#Mann=3,-1,0
  4448.4    0.05       0  4992.9    0.03       0  4998.9    0.05       0
Bank Sta=4992.9,4998.9
Exp/Cntr=0.3,0.1

Type RM Length L Ch R = 1,8536,516,516,516
BEGIN DESCRIPTION:
UNT 067 IN UKCR 10.0
END DESCRIPTION:
XS GIS Cut Line= 3
      3611999.59     10598610.19      3611549.61     10598710.19
      3611049.57     10599010.21
#Sta/Elev= 30
  4531.4  401.54  4572.4  398.29  4599.2  397.24  4604.4  395.51  4623.6  395.71
  4647.9  392.19  4654.3  390.54  4685.0  388.14  4715.8  384.63  4838.7  375.67
  4961.6  372.17  4968.0  370.90  4973.2  367.50  4982.1  369.89  4995.3  369.09
  4997.1  366.75  4999.9  366.25  5003.1  366.75  5006.0  370.40  5027.3  372.36
  5167.3  372.85  5239.2  371.44  5276.1  371.96  5365.5  376.69  5400.5  380.49
  5435.5  382.53  5503.5  388.83  5509.4  388.47  5524.9  390.76  5575.5  392.39
#Mann=3,-1,0
  4531.4    0.05       0  4997.1    0.03       0  5003.1    0.05       0
Bank Sta=4997.1,5003.1
Exp/Cntr=0.3,0.1

Type RM Length L Ch R = 1,8020,433,433,433
BEGIN DESCRIPTION:
UNT 067 IN UKCR 9.0
END DESCRIPTION:
XS GIS Cut Line= 3
      3611699.59     10597910.21      3611149.61     10598510.19
      3611049.61     10598960.20
#Sta/Elev= 30
  4218.3  405.46  4303.1  401.34  4324.6  398.23  4430.7  390.88  4451.7  387.84
  4480.0  386.44  4487.4  387.07  4508.4  384.39  4636.0  376.91  4784.6  370.69
  4925.8  370.21  4975.8  371.46  4982.6  368.10  5001.2  366.18  5003.9  365.68
  5007.2  366.18  5010.9  368.78  5018.3  368.17  5025.1  371.16  5028.8  371.27
  5124.4  371.23  5134.7  370.53  5148.7  367.66  5155.1  367.91  5165.4  370.63
  5197.4  372.26  5206.4  373.77  5298.6  378.37  5468.9  389.85  5493.2  390.43
#Mann=3,-1,0
  4218.3    0.05       0  5001.2    0.03       0  5007.2    0.05       0
Bank Sta=5001.2,5007.2
Exp/Cntr=0.3,0.1

Type RM Length L Ch R = 1,7587,288,288,288
BEGIN DESCRIPTION:
UNT 067 IN UKCR 8.0
END DESCRIPTION:
XS GIS Cut Line= 3
      3611699.64     10597860.17      3611049.61     10598160.19
      3610799.61     10598610.18
#Sta/Elev= 30
  4275.8  407.97  4313.0  406.40  4341.9  403.47  4397.0  400.83  4410.3  398.95
  4427.7  397.75  4433.2  396.60  4463.1  395.01  4496.1  391.97  4616.8  383.25
  4622.3  383.60  4705.4  376.12  4737.0  375.09  4793.9  371.34  4857.3  369.10
  4885.7  368.87  4914.6  370.11  4969.7  370.26  4994.6  369.20  4999.7  366.19
  5002.5  366.17  5005.2  365.67  5008.5  366.17  5014.6  369.29  5037.5  370.45
  5270.8  369.64  5308.6  370.63  5433.3  376.00  5471.0  378.42  5506.5  382.13
#Mann=3,-1,0
  4275.8    0.05       0  5002.5    0.03       0  5008.5    0.05       0
Bank Sta=5002.5,5008.5
Exp/Cntr=0.3,0.1

Type RM Length L Ch R = 1,7299,135,135,135
BEGIN DESCRIPTION:
Mapping XS 7f44e73e
END DESCRIPTION:
XS GIS Cut Line= 4
      3611509.15     10597387.61      3610957.07     10597887.60
      3610759.15     10598165.38      3610468.25     10598636.37
#Sta/Elev= 30
  4034.0  403.61  4177.2  393.72  4226.5  391.39  4325.9  384.72  4332.6  385.02
  4340.1  381.90  4346.8  383.37  4354.3  380.96  4361.0  382.14  4368.5  381.01
  4375.2  381.88  4382.7  380.13  4452.9  378.84  4594.9  372.05  4729.4  367.68
  4972.5  369.66  4987.2  369.00  4990.4  366.67  4993.1  366.17  4996.4  366.67
  5022.9  369.65  5137.3  368.13  5254.9  371.01  5398.4  379.15  5435.0  379.67
  5450.4  381.31  5493.0  382.46  5564.9  386.75  5624.2  390.59  5673.5  392.39
#Mann=4,-1,0
  4034.0    0.05       0  4990.4    0.03       0  4996.4    0.05       0
  5564.9    0.08       0
Bank Sta=4990.4,4996.4
Exp/Cntr=0.3,0.1

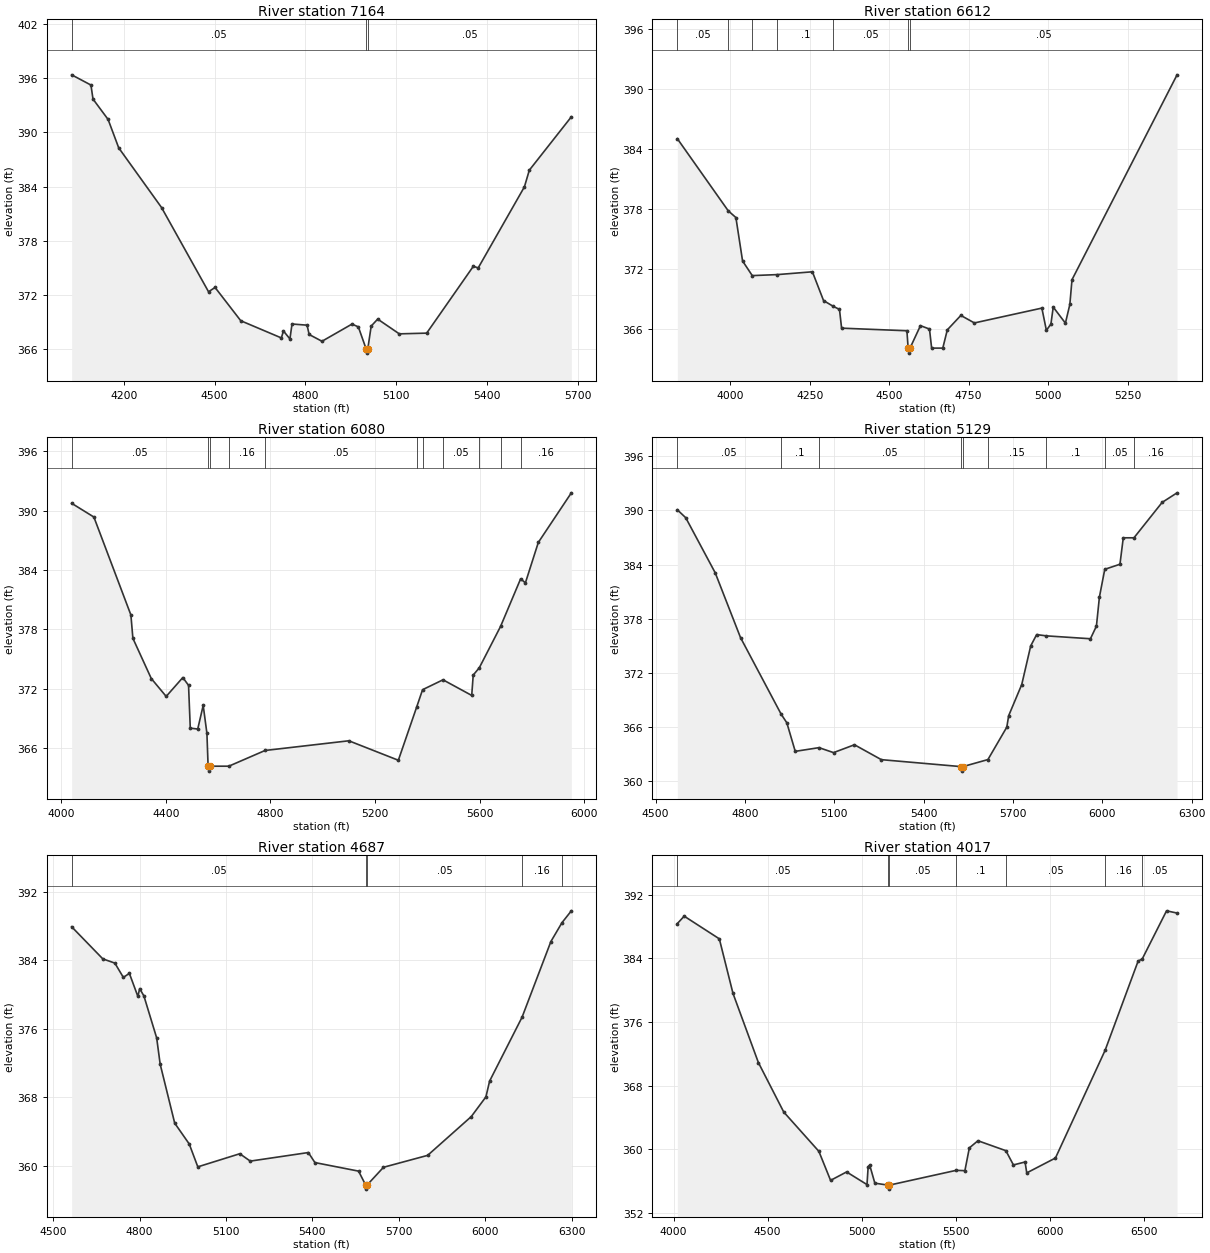
Type RM Length L Ch R = 1,7164,552,552,552
BEGIN DESCRIPTION:
UNT 067 IN UKCR 7.0
END DESCRIPTION:
XS GIS Cut Line= 3
      3611399.63     10597260.16      3610699.61     10598010.19
      3610399.63     10598560.15
#Sta/Elev= 30
  4027.1  396.35  4090.9  395.22  4097.7  393.67  4147.6  391.42  4182.7  388.28
  4324.4  381.68  4479.8  372.37  4501.3  372.85  4586.3  369.17  4720.6  367.27
  4727.4  368.04  4748.9  367.16  4755.8  368.81  4805.6  368.68  4812.4  367.65
  4854.9  366.90  4954.1  368.80  4975.1  368.49  5000.5  366.09  5003.2  365.59
  5006.5  366.09  5017.6  368.58  5039.1  369.35  5110.5  367.72  5201.1  367.80
  5355.4  375.19  5371.5  375.01  5524.3  383.97  5540.5  385.81  5679.5  391.71
#Mann=3,-1,0
  4027.1    0.05       0  5000.5    0.03       0  5006.5    0.05       0
Bank Sta=5000.5,5006.5
Exp/Cntr=0.3,0.1

Type RM Length L Ch R = 1,6612,532,532,532
BEGIN DESCRIPTION:
UNT 067 IN UKCR 6.0
END DESCRIPTION:
XS GIS Cut Line= 3
      3611099.62     10597110.17      3610291.13     10598007.13
      3610199.61     10598360.20
#Sta/Elev= 30
  3833.5  385.02  3993.6  377.83  4017.7  377.16  4038.7  372.83  4069.2  371.37
  4148.0  371.47  4258.4  371.75  4293.5  368.88  4324.3  368.30  4343.6  368.00
  4350.3  366.13  4555.8  365.87  4559.6  364.14  4562.3  363.64  4565.6  364.14
  4598.4  366.38  4626.8  366.04  4633.6  364.14  4668.7  364.14  4682.9  365.96
  4725.5  367.40  4768.1  366.65  4980.4  368.13  4994.6  365.92  5008.8  366.52
  5016.2  368.23  5054.5  366.63  5068.5  368.50  5075.2  370.96  5405.8  391.39
#Mann=7,-1,0
  3833.5    0.05       0  3993.6     0.1       0  4069.2    0.15       0
  4148.0     0.1       0  4324.3    0.05       0  4559.6    0.03       0
  4565.6    0.05       0
Bank Sta=4559.6,4565.6
Exp/Cntr=0.3,0.1

Type RM Length L Ch R = 1,6080,951,951,951
BEGIN DESCRIPTION:
UNT 067 IN UKCR 5.0
END DESCRIPTION:
XS GIS Cut Line= 3
      3610799.61     10596810.19      3610149.61     10597560.19
      3609699.59     10598360.23
#Sta/Elev= 30
  4039.8  390.74  4124.8  389.35  4266.3  379.44  4273.9  377.08  4344.2  373.01
  4401.2  371.20  4464.8  373.11  4486.7  372.32  4493.3  367.99  4521.8  367.90
  4542.7  370.29  4556.9  367.47  4561.5  364.14  4564.3  363.64  4567.5  364.14
  4640.7  364.14  4779.3  365.73  5099.5  366.71  5288.8  364.74  5358.4  370.09
  5381.4  371.88  5459.5  372.88  5569.3  371.30  5575.0  373.36  5598.3  374.10
  5679.7  378.29  5756.3  383.10  5774.5  382.69  5823.9  386.78  5950.2  391.80
#Mann=11,-1,0
  4039.8    0.05       0  4561.5    0.03       0  4567.5    0.05       0
  4640.7    0.16       0  4779.3    0.05       0  5358.4    0.16       0
  5381.4    0.08       0  5459.5    0.05       0  5598.3     0.1       0
  5679.7    0.05       0  5756.3    0.16       0
Bank Sta=4561.5,4567.5
Exp/Cntr=0.3,0.1

Type RM Length L Ch R = 1,5129,442,442,442
BEGIN DESCRIPTION:
UNT 067 IN UKCR 4.0
END DESCRIPTION:
XS GIS Cut Line= 3
      3610049.58     10596810.22      3609749.61     10597110.19
      3609649.61     10598360.17
#Sta/Elev= 30
  4572.9  390.07  4601.1  389.19  4700.1  383.09  4785.0  375.92  4921.6  367.43
  4940.6  366.48  4968.8  363.32  5048.6  363.73  5097.4  363.18  5167.7  364.05
  5258.0  362.40  5525.8  361.63  5528.6  361.13  5531.8  361.63  5615.9  362.41
  5679.3  366.00  5685.6  367.27  5729.5  370.72  5759.6  375.00  5779.6  376.25
  5812.1  376.11  5960.2  375.79  5980.3  377.19  5990.3  380.40  6008.3  383.48
  6059.3  384.04  6070.5  386.97  6106.4  386.97  6201.0  390.89  6251.1  391.95
#Mann=9,-1,0
  4572.9    0.05       0  4921.6     0.1       0  5048.6    0.05       0
  5525.8    0.07       0  5531.8    0.05       0  5615.9    0.15       0
  5812.1     0.1       0  6008.3    0.05       0  6106.4    0.16       0
Bank Sta=5525.8,5531.8
Exp/Cntr=0.3,0.1

Type RM Length L Ch R = 1,4687,670,670,670
BEGIN DESCRIPTION:
UNT 067 IN UKCR 3.0
END DESCRIPTION:
XS GIS Cut Line= 3
      3609749.62     10596660.18      3609399.61     10596910.19
      3608699.59     10598010.21
#Sta/Elev= 30
  4564.5  387.92  4672.7  384.17  4714.4  383.68  4743.9  382.01  4764.8  382.48
  4794.3  379.79  4800.5  380.70  4815.2  379.85  4859.5  374.95  4871.7  371.88
  4922.1  365.00  4972.5  362.57  5002.3  359.90  5147.9  361.43  5184.3  360.57
  5385.8  361.57  5408.6  360.40  5560.2  359.40  5584.3  357.80  5587.0  357.30
  5590.3  357.80  5646.6  359.85  5799.8  361.24  5951.3  365.77  6002.1  368.07
  6014.8  369.91  6127.5  377.37  6227.4  386.19  6266.0  388.40  6298.5  389.78
#Mann=5,-1,0
  4564.5    0.05       0  5584.3    0.03       0  5590.3    0.05       0
  6127.5    0.16       0  6266.0    0.05       0
Bank Sta=5584.3,5590.3
Exp/Cntr=0.3,0.1

Type RM Length L Ch R = 1,4017,199,199,199
BEGIN DESCRIPTION:
UNT 067 IN UKCR 2.0
END DESCRIPTION:
XS GIS Cut Line= 5
      3610004.64     10596496.71      3609202.59     10596277.97
      3609046.34     10596486.30      3608676.54     10597350.88
      3608582.81     10597965.36
#Sta/Elev= 30
  4020.4  388.35  4056.7  389.28  4243.3  386.43  4315.8  379.58  4450.6  370.89
  4585.3  364.67  4771.9  359.73  4834.1  356.08  4919.2  357.14  5027.5  355.55
  5033.7  357.81  5042.0  357.99  5069.2  355.73  5139.8  355.48  5142.5  354.98
  5145.8  355.48  5501.1  357.34  5547.4  357.30  5571.0  360.16  5616.7  361.06
  5765.0  359.81  5805.1  358.02  5866.9  358.39  5875.9  357.02  6028.3  358.89
  6291.8  372.41  6467.4  383.64  6489.1  383.90  6618.3  389.95  6674.1  389.67
#Mann=7,-1,0
  4020.4    0.05       0  5139.8    0.03       0  5145.8    0.05       0
  5501.1     0.1       0  5765.0    0.05       0  6291.8    0.16       0
  6489.1    0.05       0
Bank Sta=5139.8,5145.8
Exp/Cntr=0.3,0.1

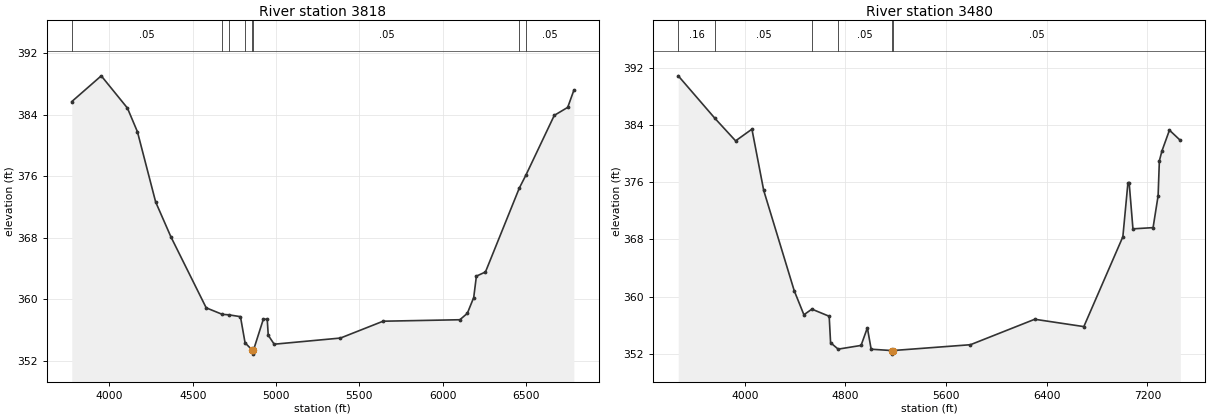
Type RM Length L Ch R = 1,3818,338,338,338
BEGIN DESCRIPTION:
Mapping XS 24b72c5d
END DESCRIPTION:
XS GIS Cut Line= 5
      3610134.90     10596465.48      3609171.34     10596095.68
      3609009.88     10596314.43      3608530.71     10597277.97
      3608452.77     10597906.67
#Sta/Elev= 30
  3773.6  385.68  3950.6  389.03  4107.6  384.84  4167.7  381.76  4277.1  372.63
  4368.4  368.11  4580.5  358.87  4677.0  358.02  4715.9  357.96  4786.1  357.72
  4813.8  354.32  4858.0  353.35  4860.8  352.85  4864.0  353.35  4923.7  357.41
  4946.8  357.38  4953.0  355.30  4988.5  354.14  5386.3  354.94  5642.4  357.13
  6103.0  357.32  6147.8  358.15  6186.2  360.21  6202.3  362.99  6256.7  363.53
  6459.7  374.43  6501.0  376.19  6669.8  383.89  6750.4  384.93  6787.2  387.15
#Mann=8,-1,0
  3773.6    0.05       0  4677.0     0.1       0  4715.9    0.08       0
  4813.8    0.05       0  4858.0    0.03       0  4864.0    0.05       0
  6459.7    0.16       0  6501.0    0.05       0
Bank Sta=4858,4864
Exp/Cntr=0.3,0.1

Type RM Length L Ch R = 1,3480,0,0,0
BEGIN DESCRIPTION:
UNT 067 IN UKCR 1.0
END DESCRIPTION:
XS GIS Cut Line= 5
      3610435.89     10596451.04      3609296.55     10595973.61
      3608656.36     10596017.01      3608330.84     10596830.81
      3608298.32     10598066.50
#Sta/Elev= 30
  3471.9  390.95  3764.3  384.97  3927.8  381.83  4057.5  383.47  4150.9  374.89
  4393.8  360.80  4470.5  357.44  4533.9  358.23  4671.4  357.23  4682.5  353.52
  4742.8  352.62  4924.7  353.14  4974.8  355.61  5004.9  352.61  5169.2  352.42
  5171.9  351.92  5175.2  352.42  5793.9  353.24  6304.8  356.81  6694.9  355.78
  7005.0  368.38  7045.0  375.89  7055.0  375.97  7085.1  369.49  7245.1  369.66
  7285.1  374.13  7295.1  379.03  7315.1  380.39  7375.2  383.33  7461.5  381.90
#Mann=6,-1,0
  3471.9    0.16       0  3764.3    0.05       0  4533.9     0.1       0
  4742.8    0.05       0  5169.2    0.03       0  5175.2    0.05       0
Bank Sta=5169.2,5175.2
Exp/Cntr=0.3,0.1

Chan Stop Cuts=-1