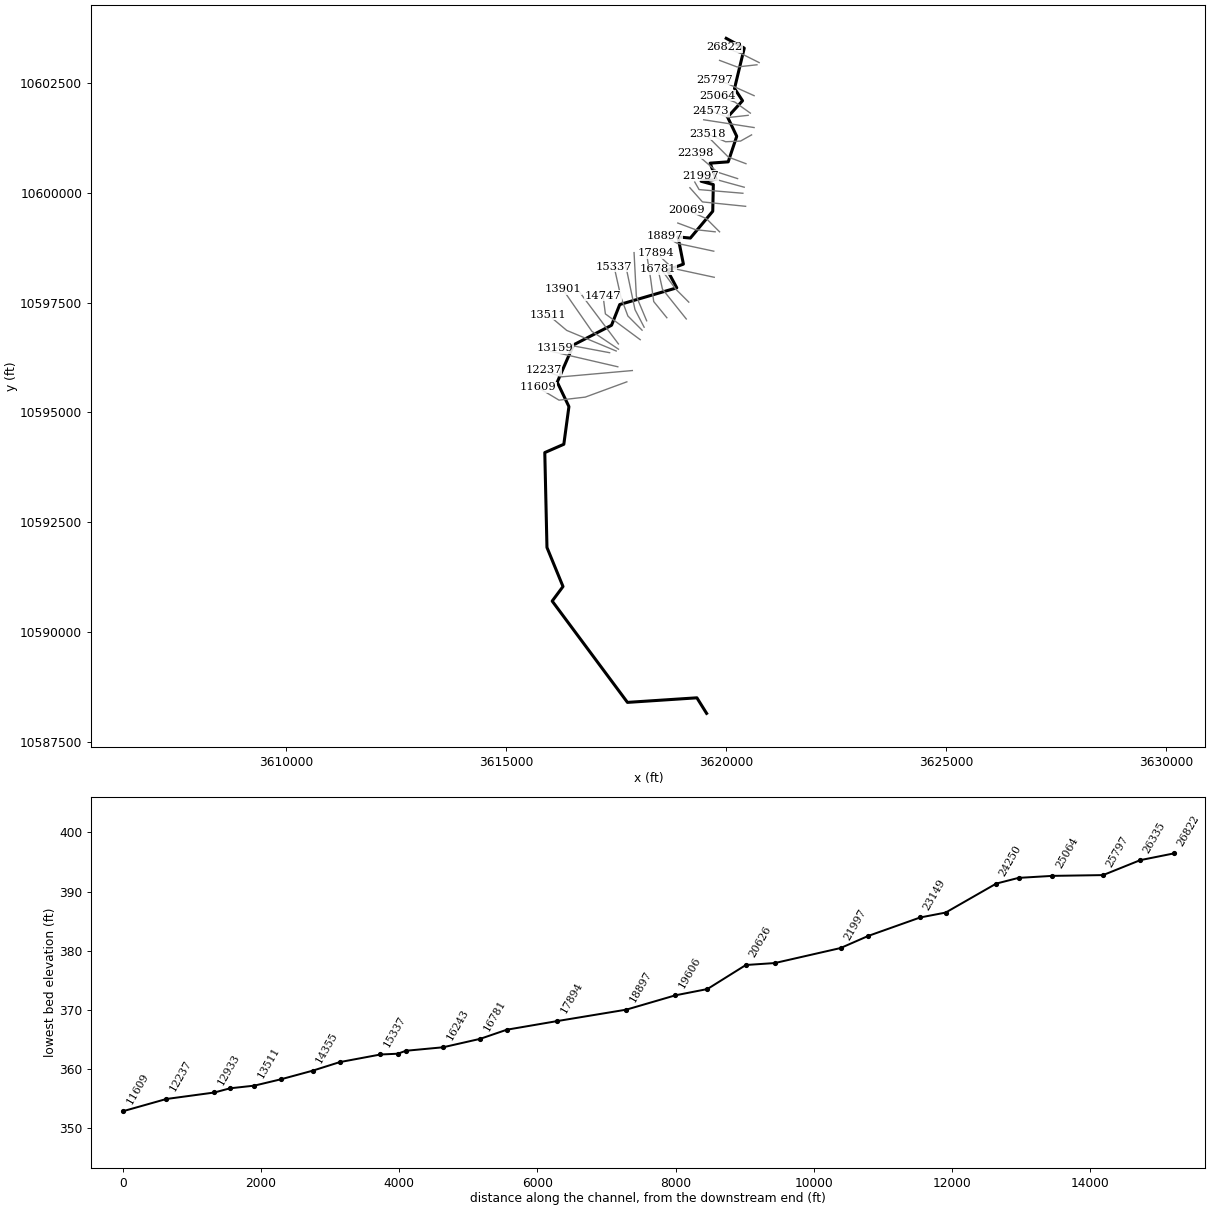
--- UNT 069 IN UKCR.prj (project) ---

Proj Title=UNT 069 IN UKCR Base Level Engineering
Current Plan=p01
Default Exp/Contr=0.3,0.1
English Units
Geom File=g01
Flow File=f01
Plan File=p01
Y Axis Title=Elevation
X Axis Title(PF)=Main Channel Distance
X Axis Title(XS)=Station
BEGIN DESCRIPTION:
UNT 069 IN UKCR
END DESCRIPTION:
DSS Export Rating Curves= 0
DSS Export Rating Curve Sorted= 0
DSS Export Volume Flow Curves= 0
DXF OffsetX= 0
DXF OffsetY= 0
DXF ScaleX= 1
DXF ScaleY= 10

--- UNT 069 IN UKCR.p01 (plan) ---

Plan Title=Multiple Run
Short Identifier=Multiple
Geom File=g01
Flow File=f01
Subcritical Flow
K Sum by GR= 0
Std Step Tol= 0.01
Critical Tol= 0.01
Num of Std Step Trials= 20
Max Error Tol= 0.3
Flow Tol Ratio= 0.001
Split Flow NTrial= 30
Split Flow Tol= 0.02
Split Flow Ratio= 0.02
Log Output Level= 0
Friction Slope Method= 1
Unsteady Friction Slope Method= 2
Unsteady Bridges Friction Slope Method= 1
Parabolic Critical Depth
Global Vel Dist=  1 , 1 , 1
Global Log Level= 0
CheckData=True
Encroach Param= -1, 0, 0, 0
BEGIN DESCRIPTION:
Multiple Run
END DESCRIPTION:

--- UNT 069 IN UKCR.f01 (steady flow) ---

Flow Title=Multiple
Program Version=4.10
Number of Profiles= 7
Profile Names=10-year,25-year,50-year,1pct_min,100-year,1pct_plu,500-year
River Rch & RM=UNT 069 IN UKCR,Reach-1         ,26822
    1850    2614    3263    2966    4011    5424    6045
River Rch & RM=UNT 069 IN UKCR,Reach-1         ,14355
    2394    3423    4305    3940    5329    7207    8143
River Rch & RM=UNT 069 IN UKCR,Reach-1         ,13901
    2394    3423    4305    3940    5329    7207    8143
River Rch & RM=UNT 069 IN UKCR,Reach-1         ,8485
    2698    3864    4864    4452    6021    8143    9205
Boundary for River Rch & Prof#=UNT 069 IN UKCR,Reach-1         , 1
Up Type= 0
Dn Type= 3
Dn Slope=0.003
Boundary for River Rch & Prof#=UNT 069 IN UKCR,Reach-1         , 2
Up Type= 0
Dn Type= 3
Dn Slope=0.003
Boundary for River Rch & Prof#=UNT 069 IN UKCR,Reach-1         , 3
Up Type= 0
Dn Type= 3
Dn Slope=0.003
Boundary for River Rch & Prof#=UNT 069 IN UKCR,Reach-1         , 4
Up Type= 0
Dn Type= 3
Dn Slope=0.003
Boundary for River Rch & Prof#=UNT 069 IN UKCR,Reach-1         , 5
Up Type= 0
Dn Type= 3
Dn Slope=0.003
Boundary for River Rch & Prof#=UNT 069 IN UKCR,Reach-1         , 6
Up Type= 0
Dn Type= 3
Dn Slope=0.003
Boundary for River Rch & Prof#=UNT 069 IN UKCR,Reach-1         , 7
Up Type= 0
Dn Type= 3
Dn Slope=0.003
DSS Import GetInterval= 0
DSS Import GetPeak= 0
DSS Import FillOption= 0

--- UNT 069 IN UKCR.g01 (geometry) ---

Geom Title=Existing Conditions
Program Version=4.10

River Reach=UNT 069 IN UKCR ,Reach-1
Reach XY= 30
      3620000.75     10603511.71        3620411.       10603289.
      3620189.25       10602371.        3620372.       10602092.
        3620032.       10601720.      3620239.75       10601283.
      3620045.75       10600702.      3619634.75       10600672.
      3619771.25       10600306.        3619430.       10600260.
      3619707.75       10600185.       3619694.5       10599578.
      3619185.75       10598968.        3618904.       10598994.
       3619027.5       10598375.      3618660.25       10598240.
       3618876.5       10597836.      3617580.25       10597456.
      3617393.25       10596984.      3616528.75       10596538.
       3616158.5       10595690.       3616424.5       10595134.
       3616308.5       10594277.      3615875.75       10594088.
      3615925.25       10591929.      3616289.75       10591041.
        3616044.       10590710.      3617755.25       10588405.
        3619334.       10588509.        3619555.       10588155.

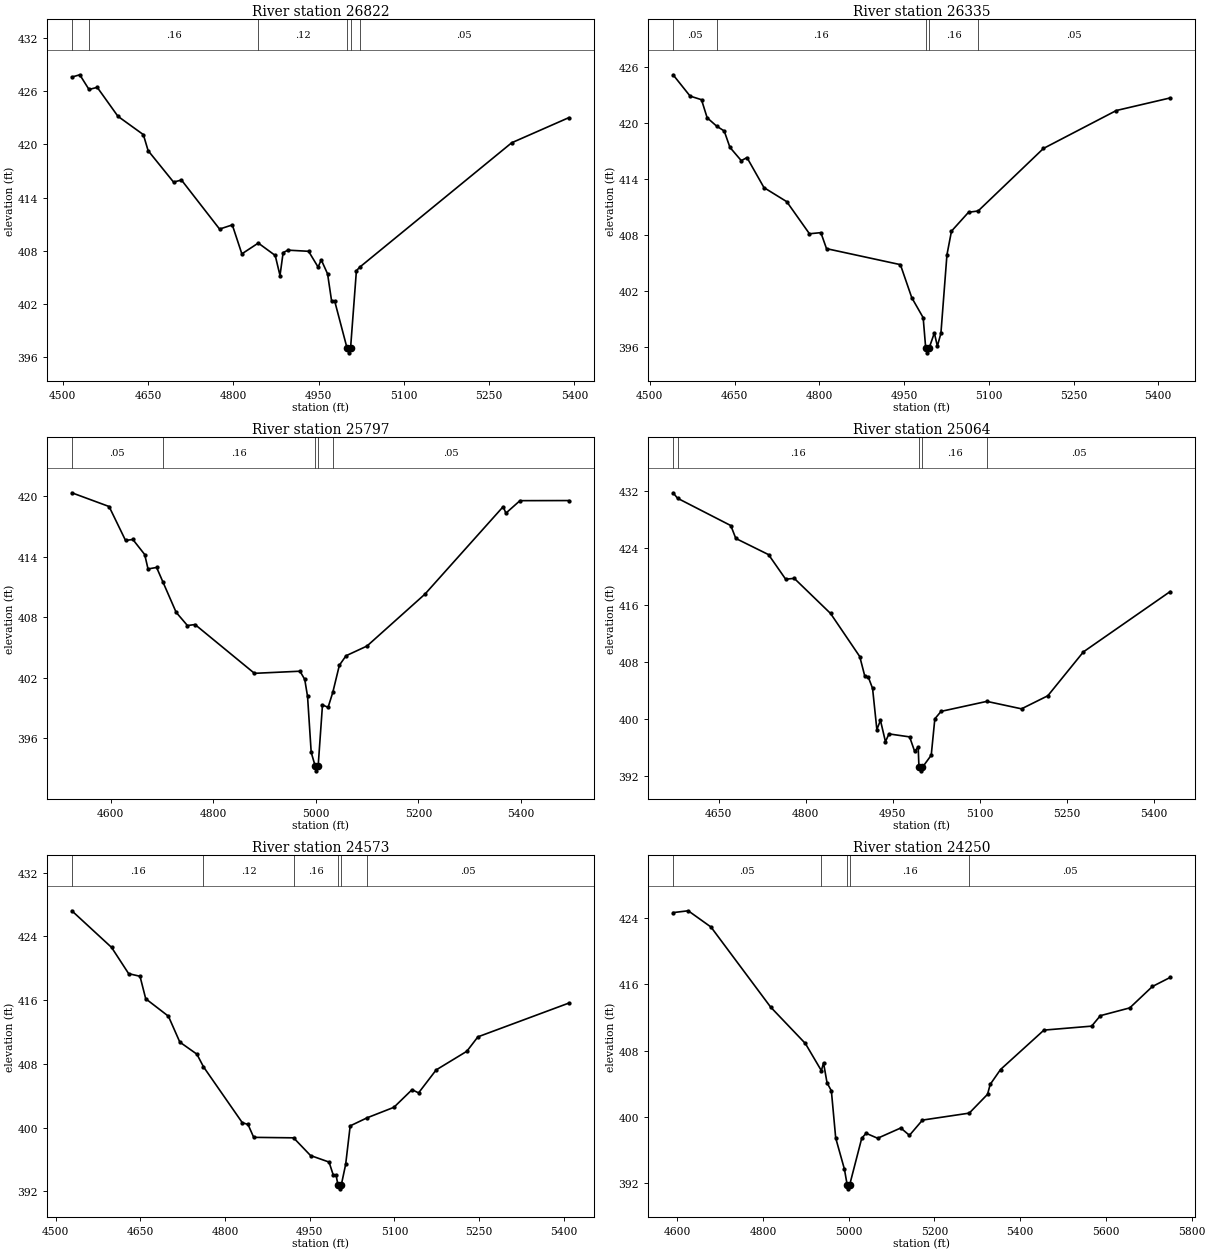
Type RM Length L Ch R = 1 ,26822   ,487,487,487
BEGIN DESCRIPTION:
UNT 069 IN UKCR 43.0
END DESCRIPTION:
XS GIS Cut Line= 3
      3620749.61     10602960.19      3620349.61     10603160.19
      3619949.62     10603310.18
#Sta/Elev= 30
    4516  427.61    4530  427.87  4546.2  426.21  4560.7  426.45  4597.1  423.18
  4641.8  421.11  4650.2   419.3  4694.9  415.75  4708.9  415.98  4775.9  410.44
  4798.3  410.91  4815.1  407.64    4844  408.86  4873.8  407.46  4882.2  405.19
  4887.7  407.78  4896.1  408.06  4932.5  407.93  4949.2  406.15  4954.8  406.96
  4965.9  405.38    4973   402.3  4978.3  402.33  5000.3  396.96    5003  396.46
  5006.3  396.96  5016.6  405.73  5022.3  406.13  5289.8  420.19  5390.4  423.03
#Mann= 6 ,-1 , 0
    4516     .05       0  4546.2     .16       0    4844     .12       0
  5000.3     .07       0  5006.3     .12       0  5022.3     .05       0
Bank Sta=5000.3,5006.3
XS Rating Curve= 0 ,0
Exp/Cntr=0.3,0.1

Type RM Length L Ch R = 1 ,26335   ,538,538,538
BEGIN DESCRIPTION:
UNT 069 IN UKCR 42.0
END DESCRIPTION:
XS GIS Cut Line= 3
      3620699.56     10602910.18      3620249.61     10602860.19
      3619849.63     10603010.18
#Sta/Elev= 30
  4541.1  425.21  4571.2  422.92  4591.4  422.53  4601.4  420.59  4618.2  419.69
  4631.6  419.17  4641.7  417.41  4661.8  415.98  4671.9  416.31    4702  413.08
  4742.3  411.57  4782.5  408.12  4802.7  408.24  4812.7  406.52  4943.5   404.8
  4963.6  401.25  4983.8   399.1  4988.3  395.82  4991.1  395.32  4994.3  395.82
  5003.6  397.46  5008.9  396.04  5015.2  397.41  5025.9  405.86  5033.9   408.4
  5064.1  410.43  5081.1  410.57  5196.7  417.29  5325.8  421.37    5421  422.72
#Mann= 5 ,-1 , 0
  4541.1     .05       0  4618.2     .16       0  4988.3     .07       0
  4994.3     .16       0  5081.1     .05       0
Bank Sta=4988.3,4994.3
XS Rating Curve= 0 ,0
Exp/Cntr=0.3,0.1

Type RM Length L Ch R = 1 ,25797   ,733,733,733
BEGIN DESCRIPTION:
UNT 069 IN UKCR 41.0
END DESCRIPTION:
XS GIS Cut Line= 3
      3620635.04     10602207.32      3620010.03     10602488.58
      3619739.24      10602571.9
#Sta/Elev= 30
  4524.6  420.31  4597.2  418.95  4629.3  415.59  4643.5  415.69  4666.6   414.2
  4673.1  412.77  4689.8  412.92  4701.8  411.52  4727.9  408.48  4749.9  407.17
  4764.7  407.27  4880.5  402.44  4969.2  402.65  4978.5  401.84    4984  400.15
  4991.1  394.62  4998.7  393.29  5001.4  392.79  5004.7  393.29  5013.1  399.32
    5024  399.07  5033.2  400.56    5046  403.24    5059  404.18  5099.8  405.14
  5212.8  410.28  5365.3  418.94  5370.5  418.29    5398  419.53  5493.3  419.54
#Mann= 5 ,-1 , 0
  4524.6     .05       0  4701.8     .16       0  4998.7     .07       0
  5004.7     .16       0  5033.2     .05       0
Bank Sta=4998.7,5004.7
XS Rating Curve= 0 ,0
Exp/Cntr=0.3,0.1

Type RM Length L Ch R = 1 ,25064   ,491,491,491
BEGIN DESCRIPTION:
UNT 069 IN UKCR 40.0
END DESCRIPTION:
XS GIS Cut Line= 3
      3620549.64     10601810.16      3620199.61     10602060.19
      3619799.57      10602210.2
#Sta/Elev= 30
  4571.1  431.81  4578.8  431.04  4670.7  427.19  4679.3  425.38  4735.8   423.1
  4765.3  419.64  4780.1  419.76  4842.7  414.82  4893.1  408.75  4901.7  406.02
  4907.9  405.84  4915.2  404.27  4922.6  398.47  4928.8  399.77  4937.4  396.77
  4943.5  397.86  4979.1  397.44  4987.7  395.42  4993.9     396  4995.2  393.16
  4997.9  392.66  5001.2  393.16  5016.4  394.86  5022.6  399.98  5033.3  401.03
  5112.3  402.44  5172.1  401.39  5217.5  403.23  5278.9  409.41  5428.5   417.9
#Mann= 5 ,-1 , 0
  4571.1     .05       0  4578.8     .16       0  4995.2     .07       0
  5001.2     .16       0  5112.3     .05       0
Bank Sta=4995.2,5001.2
XS Rating Curve= 0 ,0
Exp/Cntr=0.3,0.1

Type RM Length L Ch R = 1 ,24573   ,323,323,323
BEGIN DESCRIPTION:
UNT 069 IN UKCR 39.0
END DESCRIPTION:
XS GIS Cut Line= 3
      3620499.61     10601760.19      3620049.61     10601710.19
      3619649.58      10601860.2
#Sta/Elev= 30
  4528.9  427.21  4599.3  422.61  4629.5  419.32  4649.6  418.99  4659.7  416.17
  4699.9  413.98  4720.1  410.73  4750.3  409.22    4762  407.63  4830.7  400.62
  4840.8   400.4  4850.9  398.78  4921.5  398.72  4951.5   396.5  4984.3  395.68
  4991.5   394.1  4996.8  394.01    5000  392.82  5002.8  392.32    5006  392.82
  5013.7  395.39  5021.7  400.22  5051.9  401.24  5099.1  402.55  5131.2  404.76
  5142.8  404.36  5173.9  407.24  5228.2  409.58  5247.8  411.39  5408.9  415.63
#Mann= 6 ,-1 , 0
  4528.9     .16       0    4762     .12       0  4921.5     .16       0
    5000     .07       0    5006     .16       0  5051.9     .05       0
Bank Sta=5000,5006
XS Rating Curve= 0 ,0
Exp/Cntr=0.3,0.1

Type RM Length L Ch R = 1 ,24250   ,732,732,732
BEGIN DESCRIPTION:
UNT 069 IN UKCR 38.0
END DESCRIPTION:
XS GIS Cut Line= 2
      3620634.48     10601482.07      3619488.68     10601659.14
#Sta/Elev= 30
  4590.4  424.66  4625.7  424.88  4678.8  422.92  4817.9  413.27  4898.9  408.88
  4936.3   405.6  4941.3  406.54  4949.5  404.14  4959.6  403.17  4969.7  397.48
    4990  393.73  4996.4  391.85  4999.1  391.35  5002.4  391.85  5030.4  397.45
  5040.6  398.05  5067.5  397.45  5121.5  398.69  5141.7   397.8  5172.1  399.64
  5281.2  400.48  5323.9  402.75    5330  403.94  5354.2  405.74  5455.4  410.49
  5566.7  410.97    5587  412.23  5655.6  413.17  5708.4  415.75  5749.8  416.84
#Mann= 5 ,-1 , 0
  4590.4     .05       0  4936.3     .16       0  4996.4     .07       0
  5002.4     .16       0  5281.2     .05       0
Bank Sta=4996.4,5002.4
XS Rating Curve= 0 ,0
Exp/Cntr=0.3,0.1

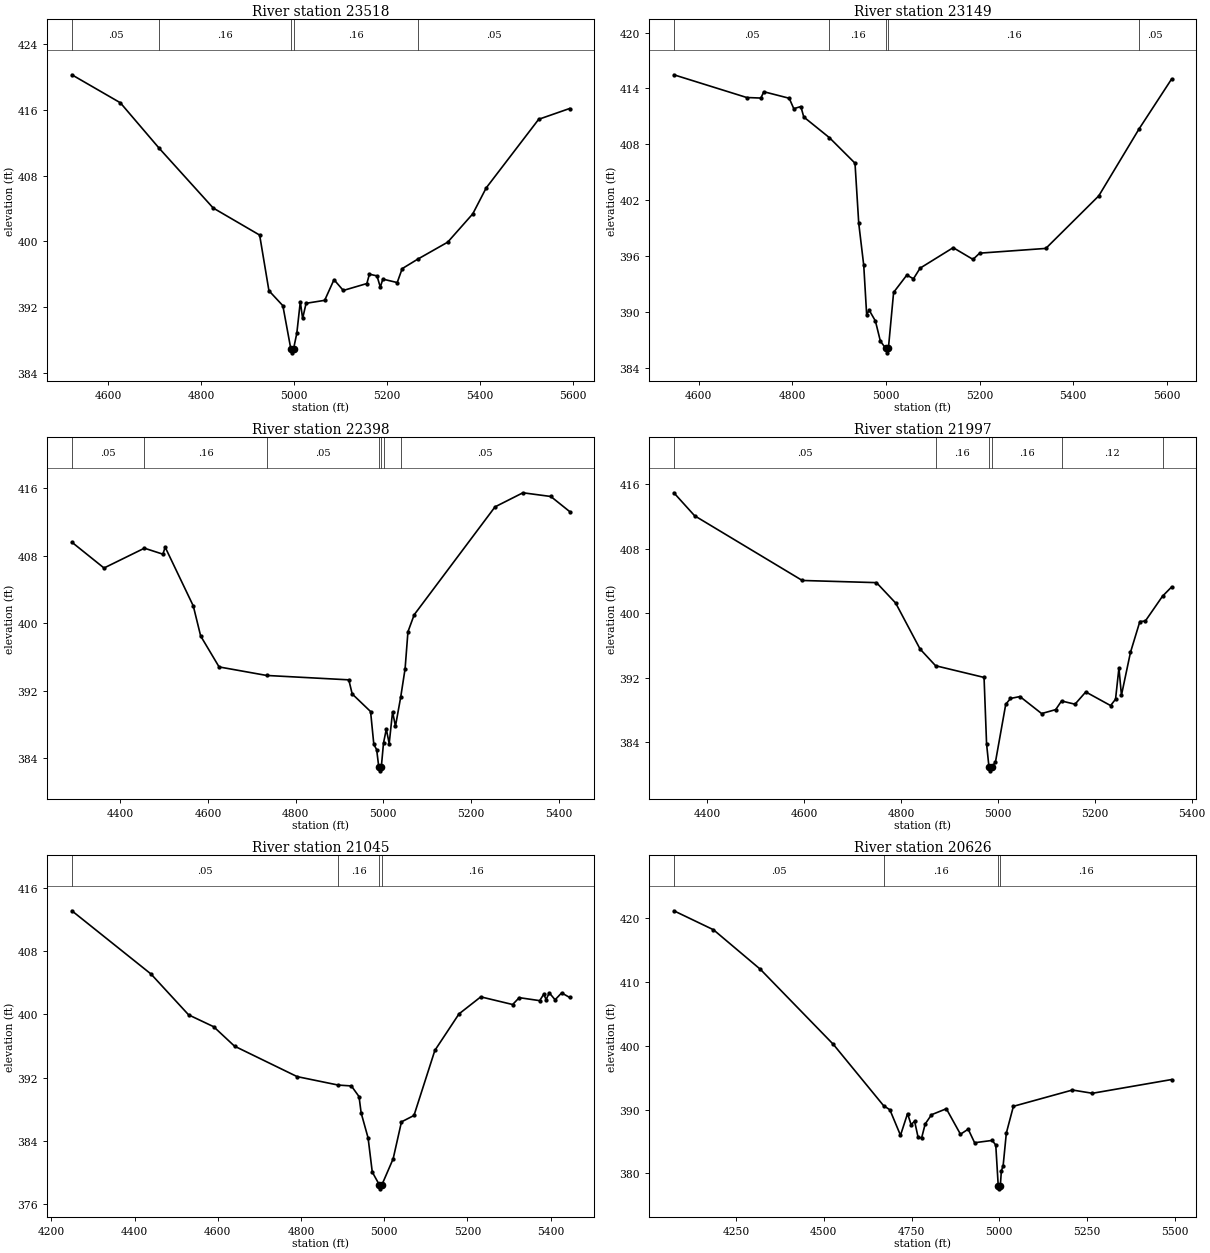
Type RM Length L Ch R = 1 ,23518   ,369,369,369
BEGIN DESCRIPTION:
UNT 069 IN UKCR 37.0
END DESCRIPTION:
XS GIS Cut Line= 4
      3620577.23     10601315.41      3620327.21     10601174.77
      3619988.67     10601159.15      3619578.42     10601335.71
#Sta/Elev= 30
  4521.3  420.24  4625.7  416.84  4709.3  411.32  4825.8  404.05  4925.9  400.76
  4945.9     394  4975.9  392.18    4993  386.95  4995.7  386.45    4999  386.95
    5006  388.84  5013.5  392.66  5018.5  390.63    5026  392.47    5066  392.83
  5086.1  395.34  5106.1  394.03  5156.9  394.87  5162.4  396.01  5178.7   395.8
  5185.9  394.43  5191.3  395.41  5222.3  394.99    5233  396.68  5266.4  397.83
  5331.1   399.9  5385.1  403.34    5414  406.49  5527.1  414.83  5593.7  416.14
#Mann= 5 ,-1 , 0
  4521.3     .05       0  4709.3     .16       0    4993     .07       0
    4999     .16       0  5266.4     .05       0
Bank Sta=4993,4999
XS Rating Curve= 0 ,0
Exp/Cntr=0.3,0.1

Type RM Length L Ch R = 1 ,23149   ,751,751,751
BEGIN DESCRIPTION:
UNT 069 IN UKCR 36.0
END DESCRIPTION:
XS GIS Cut Line= 3
      3620449.58      10600660.2      3620049.61     10600810.19
      3619599.58     10601260.22
#Sta/Elev= 30
  4546.7  415.47  4702.4  413.03  4732.7  412.97  4738.9  413.65  4793.2  412.95
    4803  411.83  4818.1  412.06  4824.3  410.94  4879.3  408.71  4933.8  405.98
  4941.8  399.52  4952.5     395  4958.7  389.72  4964.1   390.2  4977.4  389.04
    4988  386.88  4999.2  386.12  5001.9  385.62  5005.2  386.12  5016.3  392.11
  5044.6  393.97  5058.7  393.57  5072.9  394.71  5143.6  396.91    5186  395.65
  5200.1  396.32  5341.6  396.83  5454.7  402.47  5540.6  409.64  5610.3  415.01
#Mann= 5 ,-1 , 0
  4546.7     .05       0  4879.3     .16       0  4999.2     .07       0
  5005.2     .16       0  5540.6     .05       0
Bank Sta=4999.2,5005.2
XS Rating Curve= 0 ,0
Exp/Cntr=0.3,0.1

Type RM Length L Ch R = 1 ,22398   ,401,401,401
BEGIN DESCRIPTION:
UNT 069 IN UKCR 35.0
END DESCRIPTION:
XS GIS Cut Line= 3
      3620259.51      10600320.6      3619806.38     10600466.44
      3619303.74     10600894.43
#Sta/Elev= 30
    4289  409.61  4362.4  406.55  4454.6   408.9  4496.8  408.19    4502  409.02
  4566.2  402.05    4583  398.49  4625.1  394.82  4733.6  393.81  4921.2  393.29
  4928.9  391.62  4970.9  389.53  4978.3  385.64  4984.8  385.01  4989.5     383
  4992.3   382.5  4995.5     383  5000.4  385.79  5006.8  387.44  5013.4  385.74
  5021.1   389.5  5027.7  387.79  5039.8  391.28  5049.7  394.61  5056.2  398.99
  5070.5  401.01    5255   413.8  5318.7  415.47  5382.4  415.03  5425.2  413.25
#Mann= 7 ,-1 , 0
    4289     .05       0  4454.6     .16       0  4733.6     .05       0
  4989.5     .03       0  4995.5     .05       0  5000.4     .16       0
  5039.8     .05       0
Bank Sta=4989.5,4995.5
XS Rating Curve= 0 ,0
Exp/Cntr=0.3,0.1

Type RM Length L Ch R = 1 ,21997   ,952,952,952
BEGIN DESCRIPTION:
Mapping XS 71514147
END DESCRIPTION:
XS GIS Cut Line= 3
      3620409.87     10600124.87      3619600.86     10600347.09
      3619416.79     10600388.77
#Sta/Elev= 30
  4330.7  414.92  4373.6  412.07  4595.8  404.05  4749.1  403.78  4788.7  401.25
  4839.1  395.55  4871.1  393.48  4971.2  392.03  4976.4   383.8  4981.3  380.95
  4984.1  380.45  4987.3  380.95  4994.7  381.53    5016   388.7  5025.8  389.42
  5045.3  389.66  5090.1  387.55  5119.1  388.04  5131.2  389.11    5159  388.71
  5181.2  390.23  5232.5  388.54  5242.7  389.33  5249.7   393.2  5254.9  389.83
  5273.5  395.13  5292.9  398.96  5304.2  399.02  5339.7   402.1  5358.4  403.24
#Mann= 6 ,-1 , 0
  4330.7     .05       0  4871.1     .16       0  4981.3     .07       0
  4987.3     .16       0  5131.2     .12       0  5339.7     .16       0
Bank Sta=4981.3,4987.3
XS Rating Curve= 0 ,0
Exp/Cntr=0.3,0.1

Type RM Length L Ch R = 1 ,21045   ,419,419,419
BEGIN DESCRIPTION:
UNT 069 IN UKCR 34.0
END DESCRIPTION:
XS GIS Cut Line= 3
      3620379.28     10599987.27       3619384.5      10600070.6
      3619285.54     10600242.48
#Sta/Elev= 30
  4249.2  413.12  4439.5  405.11  4529.9  399.94  4590.1  398.44  4640.2  395.98
  4790.8  392.12  4889.5  391.05  4921.2  390.94  4939.6  389.59  4944.7  387.52
  4961.4  384.35  4971.4  380.04  4988.5  378.41  4991.2  377.91  4994.5  378.41
  5021.6  381.71  5041.6  386.39  5071.7   387.2  5121.9  395.44  5179.9  400.06
  5232.3  402.22  5308.9  401.25  5324.7  402.12  5373.9  401.74  5383.6  402.55
  5389.4  401.88    5397  402.73  5410.9  401.85  5426.7  402.72  5445.8  402.15
#Mann= 4 ,-1 , 0
  4249.2     .05       0  4889.5     .16       0  4988.5     .07       0
  4994.5     .16       0
Bank Sta=4988.5,4994.5
XS Rating Curve= 0 ,0
Exp/Cntr=0.3,0.1

Type RM Length L Ch R = 1 ,20626   ,557,557,557
BEGIN DESCRIPTION:
UNT 069 IN UKCR 33.0
END DESCRIPTION:
XS GIS Cut Line= 3
      3620441.84     10599690.39      3619460.27     10599790.55
      3619174.37     10600113.26
#Sta/Elev= 30
  4072.9  421.11  4185.7  418.14  4319.3  411.95  4527.5  400.18  4670.2  390.61
  4688.3  389.95  4718.5  385.96  4738.6  389.36  4748.6  387.64  4758.7  388.16
  4768.7  385.63  4778.8  385.57  4788.8  387.73  4806.8  389.18  4849.1  390.12
  4889.3  386.13  4911.4  386.92  4929.6   384.8  4979.8  385.16  4989.9  384.43
  4996.9  378.08  4999.7  377.58  5002.9  378.08  5005.8  380.37  5010.9  381.21
    5020  386.31  5040.1   390.5  5208.3  393.05  5265.2  392.54  5490.7  394.69
#Mann= 4 ,-1 , 0
  4072.9     .05       0  4670.2     .16       0  4996.9     .07       0
  5002.9     .16       0
Bank Sta=4996.9,5002.9
XS Rating Curve= 0 ,0
Exp/Cntr=0.3,0.1

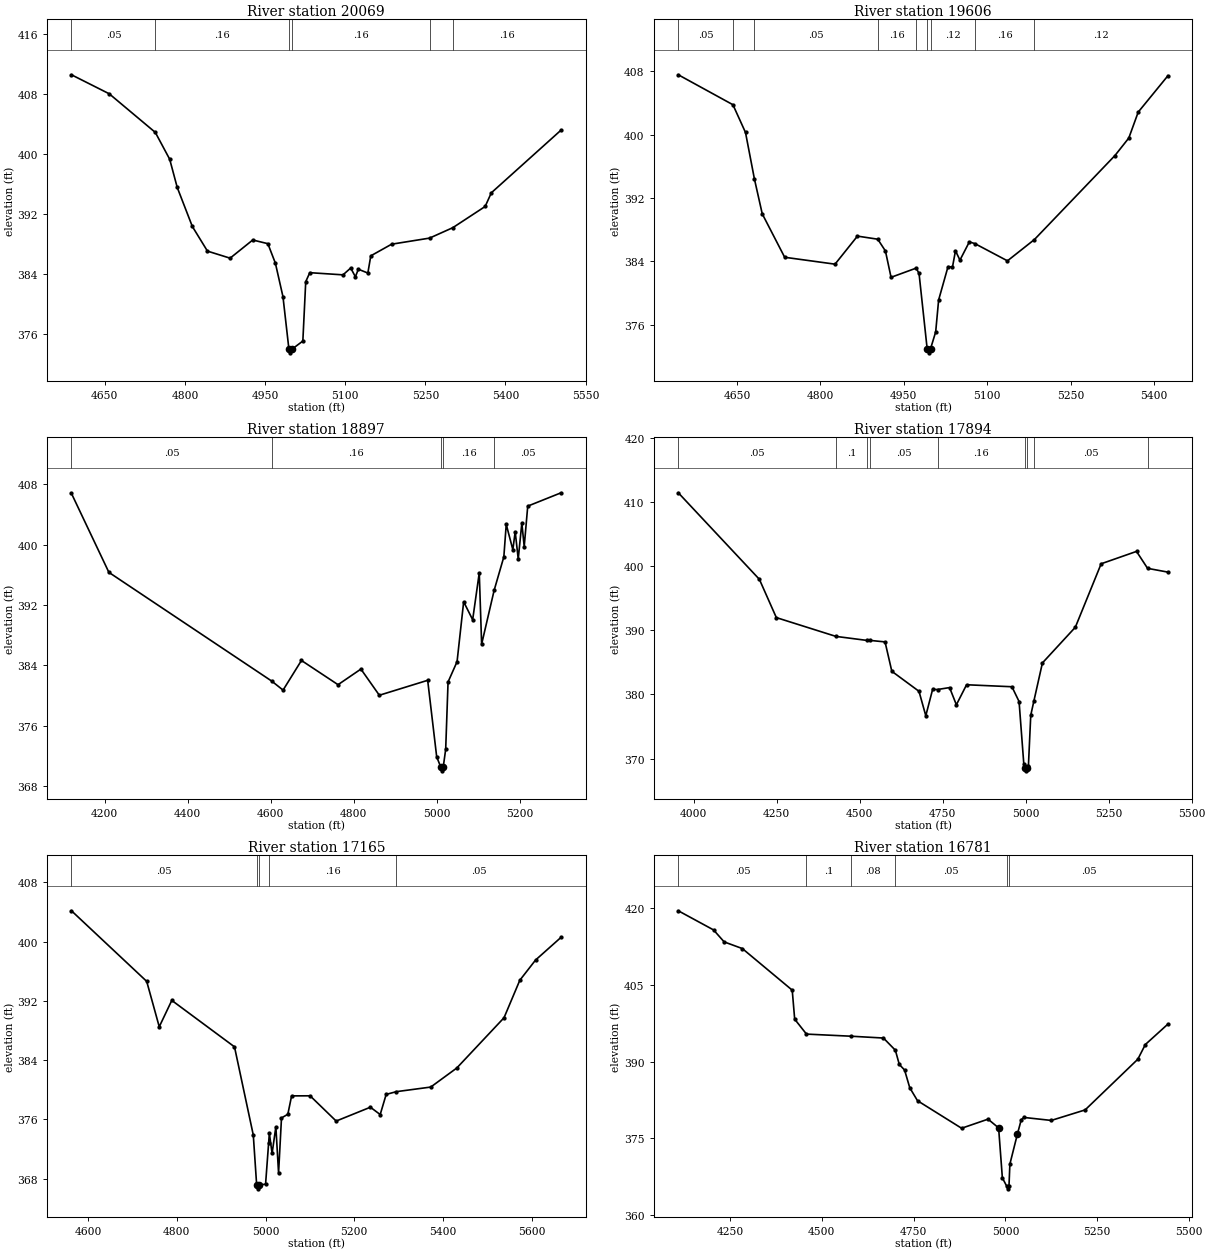
Type RM Length L Ch R = 1 ,20069   ,463,463,463
BEGIN DESCRIPTION:
UNT 069 IN UKCR 32.0
END DESCRIPTION:
XS GIS Cut Line= 3
      3619849.61     10599110.18      3619549.61     10599410.19
      3619099.62     10599610.18
#Sta/Elev= 30
  4587.5  410.52  4658.2  407.99  4744.5  402.85  4771.4  399.28  4785.5  395.53
  4813.8  390.33  4842.1  387.05  4884.5  386.11  4926.9  388.53  4955.2  388.04
  4969.3  385.44  4983.5  380.98  4994.6  374.01  4997.4  373.51  5000.6  374.01
  5020.7  375.08  5026.1  382.98  5033.7  384.18  5095.9  383.89  5110.3   384.8
  5119.1  383.63  5124.6  384.64  5142.4  384.13  5147.9  386.42  5186.9  387.97
  5257.9  388.78  5301.5  390.17    5362  392.99  5373.6  394.81  5504.2  403.16
#Mann= 6 ,-1 , 0
  4587.5     .05       0  4744.5     .16       0  4994.6     .07       0
  5000.6     .16       0  5257.9     .12       0  5301.5     .16       0
Bank Sta=4994.6,5000.6
XS Rating Curve= 0 ,0
Exp/Cntr=0.3,0.1

Type RM Length L Ch R = 1 ,19606   ,709,709,709
BEGIN DESCRIPTION:
UNT 069 IN UKCR 31.0
END DESCRIPTION:
XS GIS Cut Line= 3
      3619749.62     10599110.19      3619299.61     10599160.19
      3618899.59     10599310.19
#Sta/Elev= 30
  4544.7  407.54  4642.9  403.76  4665.5  400.26  4681.5   394.4  4695.6  389.99
  4735.9  384.51  4826.4  383.64  4866.7  387.18  4903.2  386.79    4917   385.3
  4927.1  381.98  4972.2  383.14  4977.4  382.47    4992  372.95  4994.7  372.45
    4998  372.95  5007.3  375.09  5012.6  379.12  5029.5  383.33  5037.5  383.28
  5042.9  385.33  5050.9  384.15  5067.8  386.45  5077.6  386.24  5136.3  384.06
  5184.8  386.75  5329.5  397.35  5354.4  399.56  5371.3  402.83  5424.7  407.42
#Mann= 9 ,-1 , 0
  4544.7     .05       0  4642.9     .16       0  4681.5     .05       0
  4903.2     .16       0  4972.2     .12       0    4992     .07       0
    4998     .12       0  5077.6     .16       0  5184.8     .12       0
Bank Sta=4992,4998
XS Rating Curve= 0 ,0
Exp/Cntr=0.3,0.1

Type RM Length L Ch R = 1 ,18897   ,1003,1003,1003
BEGIN DESCRIPTION:
UNT 069 IN UKCR 30.0
END DESCRIPTION:
XS GIS Cut Line= 3
      3619717.84     10598669.56      3618889.71     10598846.65
      3618599.59      10599010.2
#Sta/Elev= 30
  4119.7   406.8  4209.9  396.34  4602.2  381.93  4629.6  380.73  4673.9  384.66
  4762.1  381.45  4817.2  383.52  4861.6  380.05  4978.1  382.03  4999.8  371.89
  5009.6  370.53  5012.3  370.03  5015.6  370.53  5021.5  372.89  5027.2  381.81
  5048.9   384.5  5064.8  392.44  5086.5  390.06  5102.4  396.28  5108.1  386.82
  5138.3  393.97  5161.6  398.39  5167.4   402.7  5183.3  399.35    5189  401.73
  5196.3  398.12    5205  402.87  5210.7  399.75  5219.2  405.12  5299.6  406.89
#Mann= 5 ,-1 , 0
  4119.7     .05       0  4602.2     .16       0  5009.6     .07       0
  5015.6     .16       0  5138.3     .05       0
Bank Sta=5009.6,5015.6
XS Rating Curve= 0 ,0
Exp/Cntr=0.3,0.1

Type RM Length L Ch R = 1 ,17894   ,729,729,729
BEGIN DESCRIPTION:
UNT 069 IN UKCR 29.0
END DESCRIPTION:
XS GIS Cut Line= 3
      3619728.29      10598075.8      3618785.54     10598278.94
      3618412.03     10598626.51
#Sta/Elev= 30
  3953.9  411.44  4198.1  397.95  4249.2  391.98  4428.6  389.05  4522.6  388.42
  4530.7  388.43  4576.6  388.19    4597  383.61  4678.8  380.49  4699.3  376.68
  4719.8  380.78  4734.8  380.77  4770.9  381.07  4791.4  378.39  4822.1  381.51
  4958.7   381.2  4980.2   378.9  4994.4  369.21  4998.2  368.59  5000.9  368.09
  5004.2  368.59  5008.3  368.81  5015.4  376.76    5025  379.02  5050.5  384.91
  5149.7  390.48  5227.4  400.37  5333.9   402.3  5367.2  399.66  5428.5  399.07
#Mann= 9 ,-1 , 0
  3953.9     .05       0  4428.6      .1       0  4522.6     .08       0
  4530.7     .05       0  4734.8     .16       0  4998.2     .07       0
  5004.2     .16       0    5025     .05       0  5367.2      .1       0
Bank Sta=4998.2,5004.2
XS Rating Curve= 0 ,0
Exp/Cntr=0.3,0.1

Type RM Length L Ch R = 1 ,17165   ,384,384,384
BEGIN DESCRIPTION:
UNT 069 IN UKCR 28.0
END DESCRIPTION:
XS GIS Cut Line= 3
      3619149.59      10597510.2      3618849.61     10597810.19
      3618449.62     10598360.17
#Sta/Elev= 30
  4562.3  404.17    4732  394.64  4760.3  388.51  4788.6  392.07    4930   385.8
  4972.4  373.89    4980  367.13  4982.8  366.63    4986  367.13  5000.1  367.27
    5007  372.84  5008.6  374.13  5014.8  371.41  5023.3  375.01  5029.4  368.77
    5036   376.2  5050.3   376.7  5058.8  379.18  5100.5  379.19  5159.3  375.78
  5236.5  377.65  5258.6  376.66  5272.1  379.38  5295.1  379.75  5372.6  380.37
  5431.3  382.94  5537.9  389.73  5573.5  394.79    5609  397.52  5666.6  400.59
#Mann= 5 ,-1 , 0
  4562.3     .05       0    4980     .03       0    4986     .05       0
    5007     .16       0  5295.1     .05       0
Bank Sta=4980,4986
XS Rating Curve= 0 ,0
Exp/Cntr=0.3,0.1

Type RM Length L Ch R = 1 ,16781   ,538,538,538
BEGIN DESCRIPTION:
UNT 069 IN UKCR 27.0
END DESCRIPTION:
XS GIS Cut Line= 3
      3619092.81     10597127.92      3618551.17     10597804.98
       3618449.6     10598260.23
#Sta/Elev= 30
  4109.1  419.52  4205.2  415.77    4234  413.43  4283.6  412.12  4419.4  403.98
  4426.1   398.3  4458.2  395.38  4578.5  394.97  4667.8  394.61  4700.3  392.22
    4711  389.44  4725.4  388.35  4739.5  384.88  4760.6  382.34  4880.7  376.95
  4952.7  378.73  4981.5  377.02  4991.7  367.24  5003.7  365.59  5006.4  365.09
  5009.7  365.59  5012.2  369.94  5032.7  375.82    5043  378.58  5050.1  379.07
  5124.9  378.48  5217.1  380.54  5360.6  390.46  5381.1  393.34  5442.6  397.34
#Mann= 6 ,-1 , 0
  4109.1     .05       0  4458.2      .1       0  4578.5     .08       0
  4700.3     .05       0  5003.7     .03       0  5009.7     .05       0
Bank Sta=4981.5,5032.7
XS Rating Curve= 0 ,0
Exp/Cntr=0.3,0.1

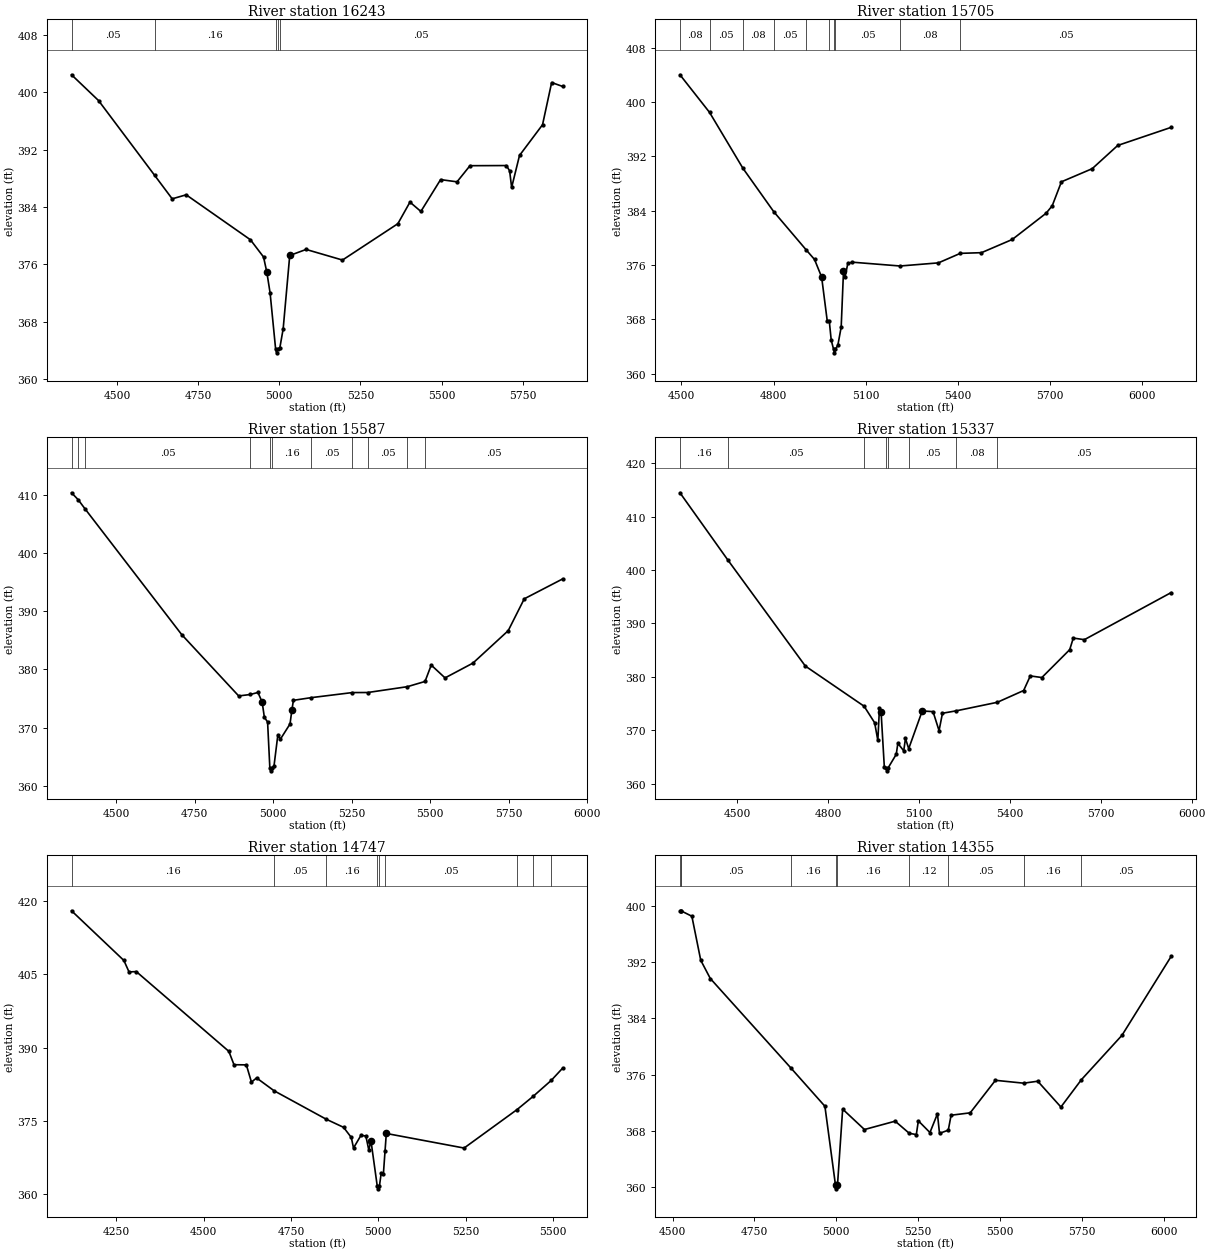
Type RM Length L Ch R = 1 ,16243   ,538,538,538
BEGIN DESCRIPTION:
UNT 069 IN UKCR 26.0
END DESCRIPTION:
XS GIS Cut Line= 4
        3618651.     10597155.67      3618352.38     10597523.73
      3618282.94     10598037.62      3618199.61     10598551.48
#Sta/Elev= 30
  4359.8  402.44  4442.9  398.85  4615.7  388.42  4669.9  385.14    4713   385.7
  4910.9  379.43  4951.3  377.03  4961.4  374.92  4971.5  372.02  4988.6  364.16
  4991.4  363.66  4994.6  364.16  5001.5  364.35  5011.8  367.01    5032  377.24
  5082.5  378.08  5194.5   376.6  5365.1  381.67  5402.4  384.68    5436  383.38
  5496.8  387.82  5547.4  387.51  5587.3  389.76  5699.4  389.78  5709.5  389.04
  5715.6  386.72  5739.9  391.19  5810.8  395.47  5838.9  401.36  5872.9  400.81
#Mann= 5 ,-1 , 0
  4359.8     .05       0  4615.7     .16       0  4988.6     .07       0
  4994.6     .16       0  5001.5     .05       0
Bank Sta=4961.4,5032
XS Rating Curve= 0 ,0
Exp/Cntr=0.3,0.1

Type RM Length L Ch R = 1 ,15705   ,118,118,118
BEGIN DESCRIPTION:
Mapping XS 4f3029b7
END DESCRIPTION:
XS GIS Cut Line= 4
       3618191.8     10597086.21      3618082.42     10597346.65
      3617957.42     10597643.52      3617905.42     10598636.77
#Sta/Elev= 30
  4495.2  403.99  4591.5  398.46  4700.1  390.24  4800.8  383.83  4905.5  378.26
  4933.4  376.81  4956.5  374.23  4974.8  367.76  4981.3  367.81  4987.7  364.95
  4995.5  363.57  4998.3  363.07  5001.5  363.57  5009.4  364.21  5020.2  366.87
  5027.7  375.07  5033.1   374.3  5041.9  376.25  5056.8  376.41    5212  375.85
  5336.8  376.31    5408  377.71    5477  377.81  5577.1  379.75  5687.3  383.61
  5707.3  384.71  5737.3  388.24  5837.5  390.17  5920.6  393.59  6094.4  396.25
#Mann= 10 ,-1 , 0
  4495.2     .08       0  4591.5     .05       0  4700.1     .08       0
  4800.8     .05       0  4905.5     .16       0  4981.3     .05       0
  4995.5     .04       0  5001.5     .05       0    5212     .08       0
    5408     .05       0
Bank Sta=4956.5,5027.7
XS Rating Curve= 0 ,0
Exp/Cntr=0.3,0.1

Type RM Length L Ch R = 1 ,15587   ,250,250,250
BEGIN DESCRIPTION:
UNT 069 IN UKCR 25.0
END DESCRIPTION:
XS GIS Cut Line= 3
       3618134.5      10596940.4      3617926.17     10597341.44
      3617697.01     10598429.95
#Sta/Elev= 30
  4357.8  410.32  4378.8  409.14  4400.2   407.6  4708.6  385.97  4890.2  375.43
    4927  375.68  4951.5  376.03  4964.9  374.38    4972  371.75  4982.2  370.97
  4989.4  363.07  4992.1  362.57  4995.4  363.07  5002.6  363.38  5014.7  368.65
    5023  368.01  5053.7  370.62  5059.4  372.94  5064.5  374.68  5121.3  375.14
    5252  376.01  5301.1  376.02  5427.3  377.02  5483.7  377.92  5503.4  380.73
  5547.4  378.53  5636.2  381.07  5748.6  386.64  5799.7  392.11  5922.1  395.53
#Mann= 11 ,-1 , 0
  4357.8     .05       0  4378.8     .16       0  4400.2     .05       0
    4927     .16       0  4989.4     .07       0  4995.4     .16       0
  5121.3     .05       0    5252     .16       0  5301.1     .05       0
  5427.3     .08       0  5483.7     .05       0
Bank Sta=4964.9,5059.4
XS Rating Curve= 0 ,0
Exp/Cntr=0.3,0.1

Type RM Length L Ch R = 1 ,15337   ,590,590,590
BEGIN DESCRIPTION:
UNT 069 IN UKCR 24.0
END DESCRIPTION:
XS GIS Cut Line= 4
      3618087.65     10596872.66      3617764.71      10597195.6
      3617608.46     10597617.48      3617452.23     10598315.32
#Sta/Elev= 30
  4310.4  414.44    4468  401.91  4724.5  382.03  4918.5  374.52  4953.3  371.43
  4963.8  368.12  4969.1   374.1  4974.6  373.38  4985.3  363.08  4991.2  362.94
  4993.9  362.44  4997.2  362.94  5024.6  365.53  5029.9  367.59  5049.3  366.18
    5055   368.5  5065.7  366.59  5110.4  373.64  5146.1  373.51  5165.9  369.96
  5177.2  373.21  5223.4  373.67  5358.4  375.26  5445.2  377.46  5467.2  380.19
  5505.4  379.89  5597.3   385.1  5609.2  387.27  5645.8  386.97  5932.1  395.77
#Mann= 8 ,-1 , 0
  4310.4     .16       0    4468     .05       0  4918.5     .16       0
  4991.2     .07       0  4997.2     .16       0  5065.7     .05       0
  5223.4     .08       0  5358.4     .05       0
Bank Sta=4974.6,5110.4
XS Rating Curve= 0 ,0
Exp/Cntr=0.3,0.1

Type RM Length L Ch R = 1 ,14747   ,392,392,392
BEGIN DESCRIPTION:
UNT 069 IN UKCR 23.0
END DESCRIPTION:
XS GIS Cut Line= 3
      3618045.33      10596656.1      3617253.64     10597242.92
      3617199.61     10597660.18
#Sta/Elev= 30
  4121.9  417.94  4271.8  407.79  4286.5  405.45  4307.3  405.52  4572.3  389.23
    4587   386.5  4622.4  386.47    4637  382.94  4651.7   383.8  4701.8  381.18
  4850.8  375.38  4900.8  373.71  4922.9  371.64  4929.2  369.49  4950.6  372.08
  4964.6  371.94    4973  369.08  4979.2  370.96  4997.3  361.65  5000.1  361.15
  5003.3  361.65  5008.5  364.36  5014.7  364.11  5019.6  368.98  5023.1  372.46
  5245.8  369.48  5397.5  377.34  5443.7  380.05  5495.1  383.28  5528.1  385.81
#Mann= 9 ,-1 , 0
  4121.9     .16       0  4701.8     .05       0  4850.8     .16       0
  4997.3     .07       0  5003.3     .16       0  5019.6     .05       0
  5397.5     .08       0  5443.7     .16       0  5495.1     .05       0
Bank Sta=4979.2,5023.1
XS Rating Curve= 0 ,0
Exp/Cntr=0.3,0.1

Type RM Length L Ch R = 1 ,14355   ,454,454,454
BEGIN DESCRIPTION:
UNT 069 IN UKCR 22.0
END DESCRIPTION:
XS GIS Cut Line= 3
       3617549.6      10596560.2      3617249.61     10596960.19
       3616649.6      10597760.2
#Sta/Elev= 30
  4522.5  399.36  4525.8  399.35  4527.2  399.32  4558.9  398.58    4586   392.3
  4615.2   389.7  4860.3  376.99  4965.2  371.48  4997.6   360.2  5000.4   359.7
  5003.6   360.2  5019.4  371.07    5086  368.16  5179.8  369.35  5222.9  367.62
  5244.4  367.44  5250.6   369.4    5286  367.73  5308.9   370.4  5315.2  367.61
    5342  368.07  5350.6   370.2  5408.9  370.54    5486  375.18  5572.4  374.77
  5615.2  375.05    5686  371.37  5748.6  375.27  5872.5   381.6  6022.5  392.84
#Mann= 10 ,-1 , 0
  4522.5      .1       0  4525.8     .08       0  4527.2     .05       0
  4860.3     .16       0  4997.6     .07       0  5003.6     .16       0
  5222.9     .12       0    5342     .05       0  5572.4     .16       0
  5748.6     .05       0
Bank Sta=4997.6,5003.6
XS Rating Curve= 0 ,0
Exp/Cntr=0.3,0.1

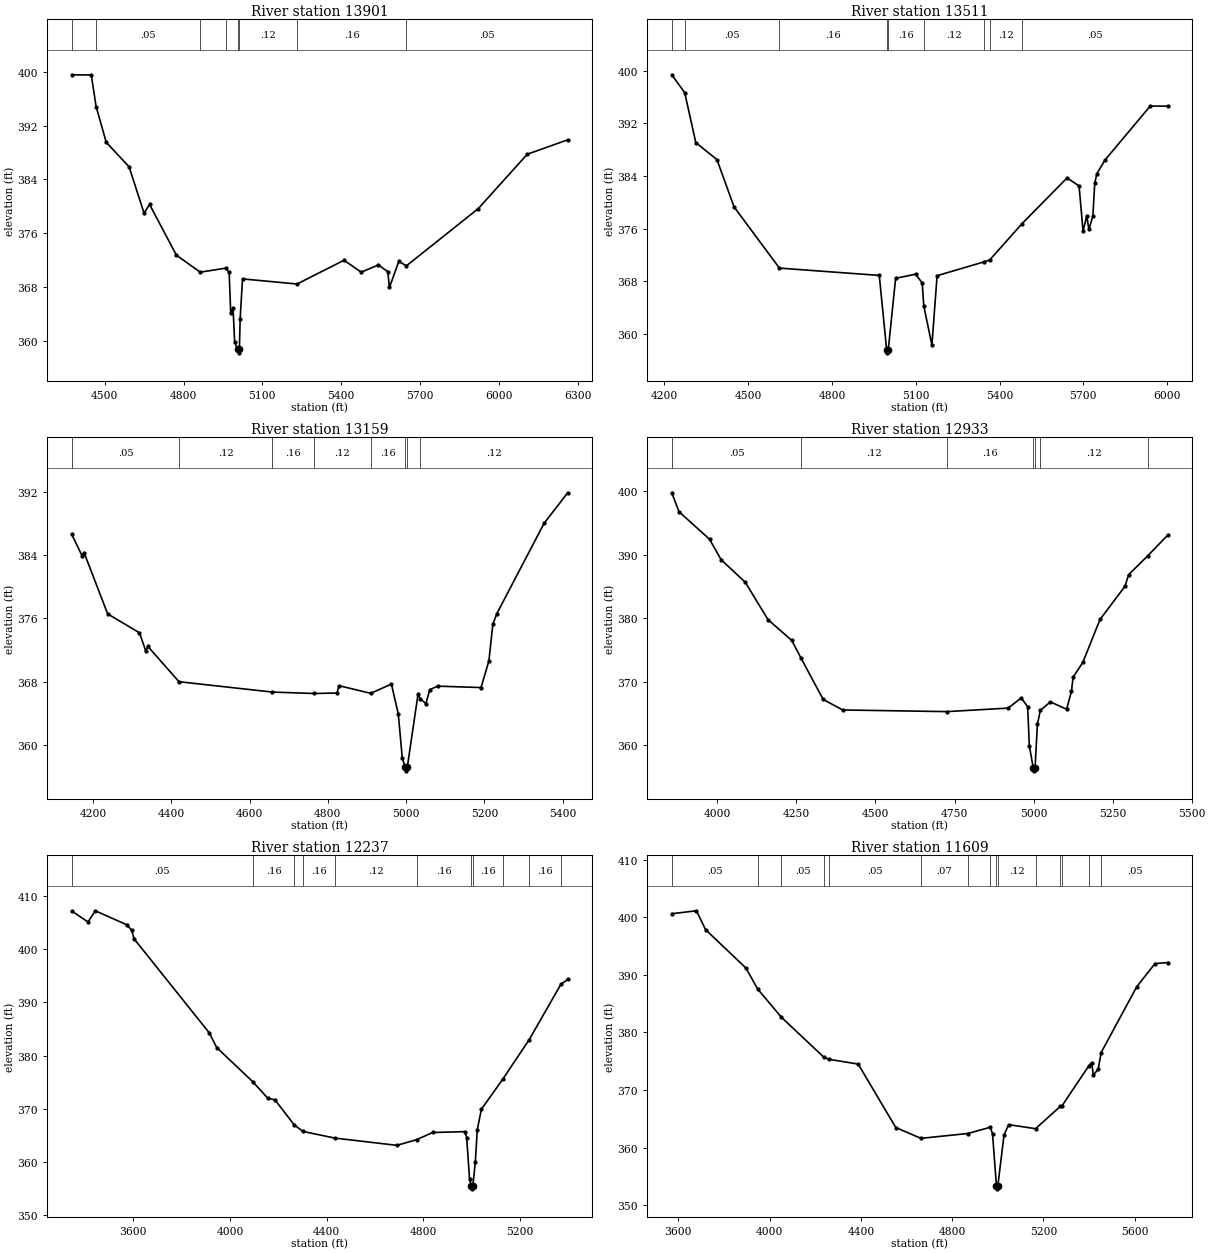
Type RM Length L Ch R = 1 ,13901   ,390,390,390
BEGIN DESCRIPTION:
UNT 069 IN UKCR 21.0
END DESCRIPTION:
XS GIS Cut Line= 3
      3617551.17     10596440.39        3616947.     10596846.65
      3616285.55     10597799.76
#Sta/Elev= 30
  4374.3  399.55  4448.5  399.52  4467.1  394.82  4505.5  389.52  4592.5  385.89
  4649.5  379.01  4670.5   380.3  4772.5  372.77  4863.4  370.24  4959.8  370.83
  4973.5  370.21  4979.5  364.21  4988.5  364.87  4994.5   359.8  5006.5  358.76
  5009.2  358.26  5012.5  358.76  5015.5  363.35  5024.5  369.24  5232.1  368.48
    5411  372.01  5476.4  370.24  5541.9  371.31  5577.7  370.31  5583.8  367.97
  5619.6  371.84  5648.5  371.18  5922.2  379.68  6108.6  387.75  6262.5  389.89
#Mann= 8 ,-1 , 0
  4374.3      .1       0  4467.1     .05       0  4863.4     .16       0
  4959.8     .12       0  5006.5     .07       0  5012.5     .12       0
  5232.1     .16       0  5648.5     .05       0
Bank Sta=5006.5,5012.5
XS Rating Curve= 0 ,0
Exp/Cntr=0.3,0.1

Type RM Length L Ch R = 1 ,13511   ,352,352,352
BEGIN DESCRIPTION:
Mapping XS 8e31d7be
END DESCRIPTION:
XS GIS Cut Line= 3
      3617499.08     10596398.73      3616374.08     10596867.48
        3615948.     10597226.01
#Sta/Elev= 30
  4226.4  399.37  4272.8  396.66  4312.5  389.08  4388.3  386.49  4449.5  379.32
  4611.9  370.03  4969.5  368.92  4995.8  357.67  4998.5  357.17  5001.8  357.67
    5028  368.48  5099.5  369.11  5123.4  367.77  5128.8   364.3    5158  358.34
  5176.5  368.88  5343.3  370.96    5365  371.27  5480.5  376.77    5642  383.72
  5684.9  382.49  5699.2  375.61  5712.4  377.99    5720   375.9  5734.3   377.9
  5740.9  382.89  5748.6  384.35  5777.2   386.4  5939.8  394.63    6002  394.61
#Mann= 9 ,-1 , 0
  4226.4      .1       0  4272.8     .05       0  4611.9     .16       0
  4995.8     .07       0  5001.8     .16       0  5128.8     .12       0
  5343.3     .16       0    5365     .12       0  5480.5     .05       0
Bank Sta=4995.8,5001.8
XS Rating Curve= 0 ,0
Exp/Cntr=0.3,0.1

Type RM Length L Ch R = 1 ,13159   ,226,226,226
BEGIN DESCRIPTION:
UNT 069 IN UKCR 20.0
END DESCRIPTION:
XS GIS Cut Line= 3
      3617349.63     10596360.18      3616549.61     10596510.19
      3616099.64     10596460.19
#Sta/Elev= 30
  4145.9  386.61  4172.2  383.91  4177.3  384.32  4237.5  376.57  4318.9  374.17
    4335  371.85  4340.1  372.46  4419.8  367.99  4658.2  366.68  4764.9   366.5
  4823.4  366.56  4828.4  367.49  4909.5  366.52  4962.4  367.69    4980   363.9
  4990.1  358.36  4997.1  357.22  4999.9  356.72  5003.1  357.22  5030.3  366.39
  5036.4  365.83  5050.4  365.21  5060.5  366.99  5080.6  367.43  5191.3  367.25
  5211.4  370.62  5221.5  375.25  5231.5  376.58  5352.3  388.01  5412.6  391.88
#Mann= 8 ,-1 , 0
  4145.9     .05       0  4419.8     .12       0  4658.2     .16       0
  4764.9     .12       0  4909.5     .16       0  4997.1     .07       0
  5003.1     .16       0  5036.4     .12       0
Bank Sta=4997.1,5003.1
XS Rating Curve= 0 ,0
Exp/Cntr=0.3,0.1

Type RM Length L Ch R = 1 ,12933   ,696,696,696
BEGIN DESCRIPTION:
UNT 069 IN UKCR 19.0
END DESCRIPTION:
XS GIS Cut Line= 2
       3617536.1     10596039.79      3616008.32     10596393.96
#Sta/Elev= 30
  3855.7  399.72  3878.7  396.74  3975.3  392.41  4011.8   389.2  4088.2  385.66
  4160.1  379.78  4235.5   376.5  4264.5  373.73  4334.6  367.24  4396.2  365.58
  4725.2  365.32  4919.7  365.87  4960.7  367.46  4981.3  366.11  4986.5  359.98
  4998.8  356.51  5001.5  356.01  5004.8  356.51  5012.1  363.31  5021.4  365.52
  5053.1  366.84  5104.5   365.7  5119.7  368.49    5125  370.74  5155.8  373.06
  5210.1   379.8  5289.2  385.03  5300.6  386.84  5360.4  389.78    5424  393.05
#Mann= 7 ,-1 , 0
  3855.7     .05       0  4264.5     .12       0  4725.2     .16       0
  4998.8     .07       0  5004.8     .16       0  5021.4     .12       0
  5360.4     .05       0
Bank Sta=4998.8,5004.8
XS Rating Curve= 0 ,0
Exp/Cntr=0.3,0.1

Type RM Length L Ch R = 1 ,12237   ,628,628,628
BEGIN DESCRIPTION:
UNT 069 IN UKCR 18.0
END DESCRIPTION:
XS GIS Cut Line= 3
      3617866.31     10595954.29      3616249.61     10595810.19
      3615849.61     10595960.19
#Sta/Elev= 30
  3346.2  407.23  3413.2  405.16  3443.3  407.27  3573.8  404.63  3593.9  403.61
  3603.9  401.98  3915.1  384.26  3945.3  381.52  4095.2  375.05  4156.1  371.99
  4186.2  371.67  4266.6  366.91  4303.1  365.71  4433.7  364.47  4690.5   363.1
  4771.7  364.17  4838.8  365.52    4972  365.68  4979.1  364.55  4990.7   356.8
  4998.3  355.41  5001.1  354.91  5004.3  355.41  5014.7  359.96  5022.7  365.98
  5039.6  369.88  5128.7  375.59    5237  382.97  5368.3  393.41  5396.5  394.34
#Mann= 11 ,-1 , 0
  3346.2     .05       0  4095.2     .16       0  4266.6     .05       0
  4303.1     .16       0  4433.7     .12       0  4771.7     .16       0
  4998.3     .07       0  5004.3     .16       0  5128.7     .05       0
    5237     .16       0  5368.3     .05       0
Bank Sta=4998.3,5004.3
XS Rating Curve= 0 ,0
Exp/Cntr=0.3,0.1

Type RM Length L Ch R = 1 ,11609   ,145,145,145
BEGIN DESCRIPTION:
UNT 069 IN UKCR 17.0
END DESCRIPTION:
XS GIS Cut Line= 4
      3617741.25     10595697.33      3616796.83     10595350.12
      3616199.61     10595280.67      3615714.07       10595572.
#Sta/Elev= 30
  3571.1  400.63  3679.4  401.14  3719.4  397.86  3896.9  391.17  3947.5  387.56
  4051.4  382.66  4238.5  375.68  4259.2  375.35  4388.3  374.51  4553.1  363.49
  4663.7  361.61  4868.6  362.45  4967.7  363.54  4977.2  362.39  4994.4  353.34
  4997.1  352.84  5000.4  353.34  5027.6  362.18  5047.7  363.99  5165.9  363.29
  5274.3  367.16  5281.6  367.25  5399.8  374.23  5411.8  374.77  5419.1  372.61
  5440.5  373.61  5453.3  376.51  5609.6  387.96  5689.3  391.96  5744.8  392.15
#Mann= 15 ,-1 , 0
  3571.1     .05       0  3947.5     .08       0  4051.4     .05       0
  4238.5     .08       0  4259.2     .05       0  4663.7     .07       0
  4868.6     .16       0  4967.7     .12       0  4994.4     .07       0
  5000.4     .12       0  5165.9     .05       0  5274.3     .12       0
  5281.6     .05       0  5399.8     .08       0  5453.3     .05       0
Bank Sta=4994.4,5000.4
XS Rating Curve= 0 ,0
Exp/Cntr=0.3,0.1