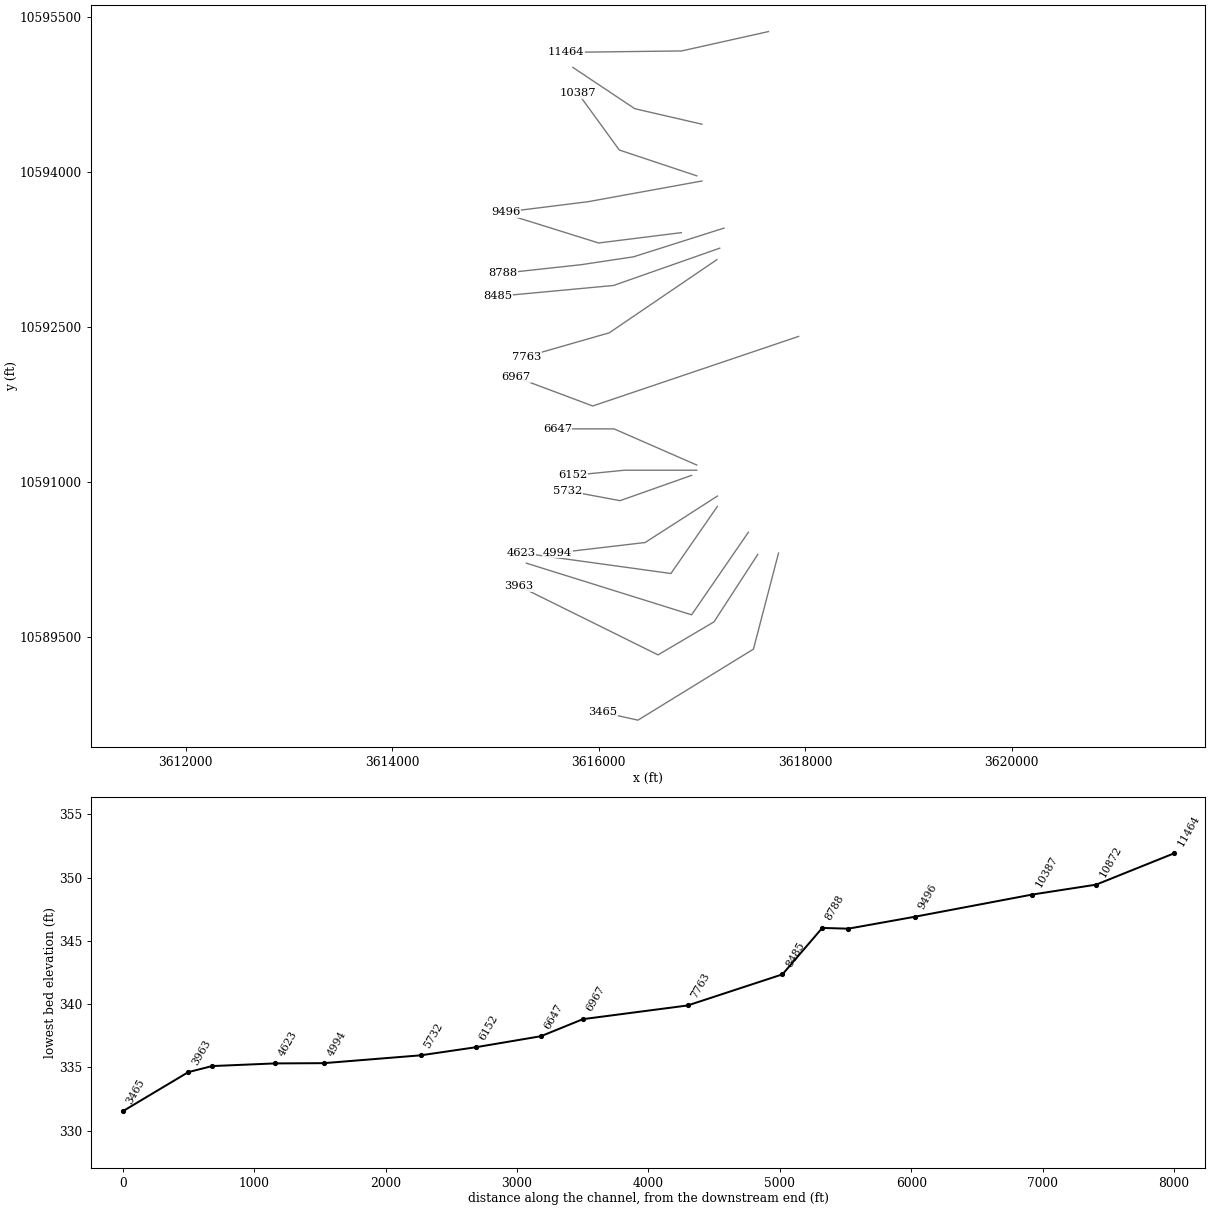
HEC-RAS study UNT 069 IN UKCR.prj: UNT 069 IN UKCR Base Level Engineering

--- UNT 069 IN UKCR.g01 (geometry) --- (continued)

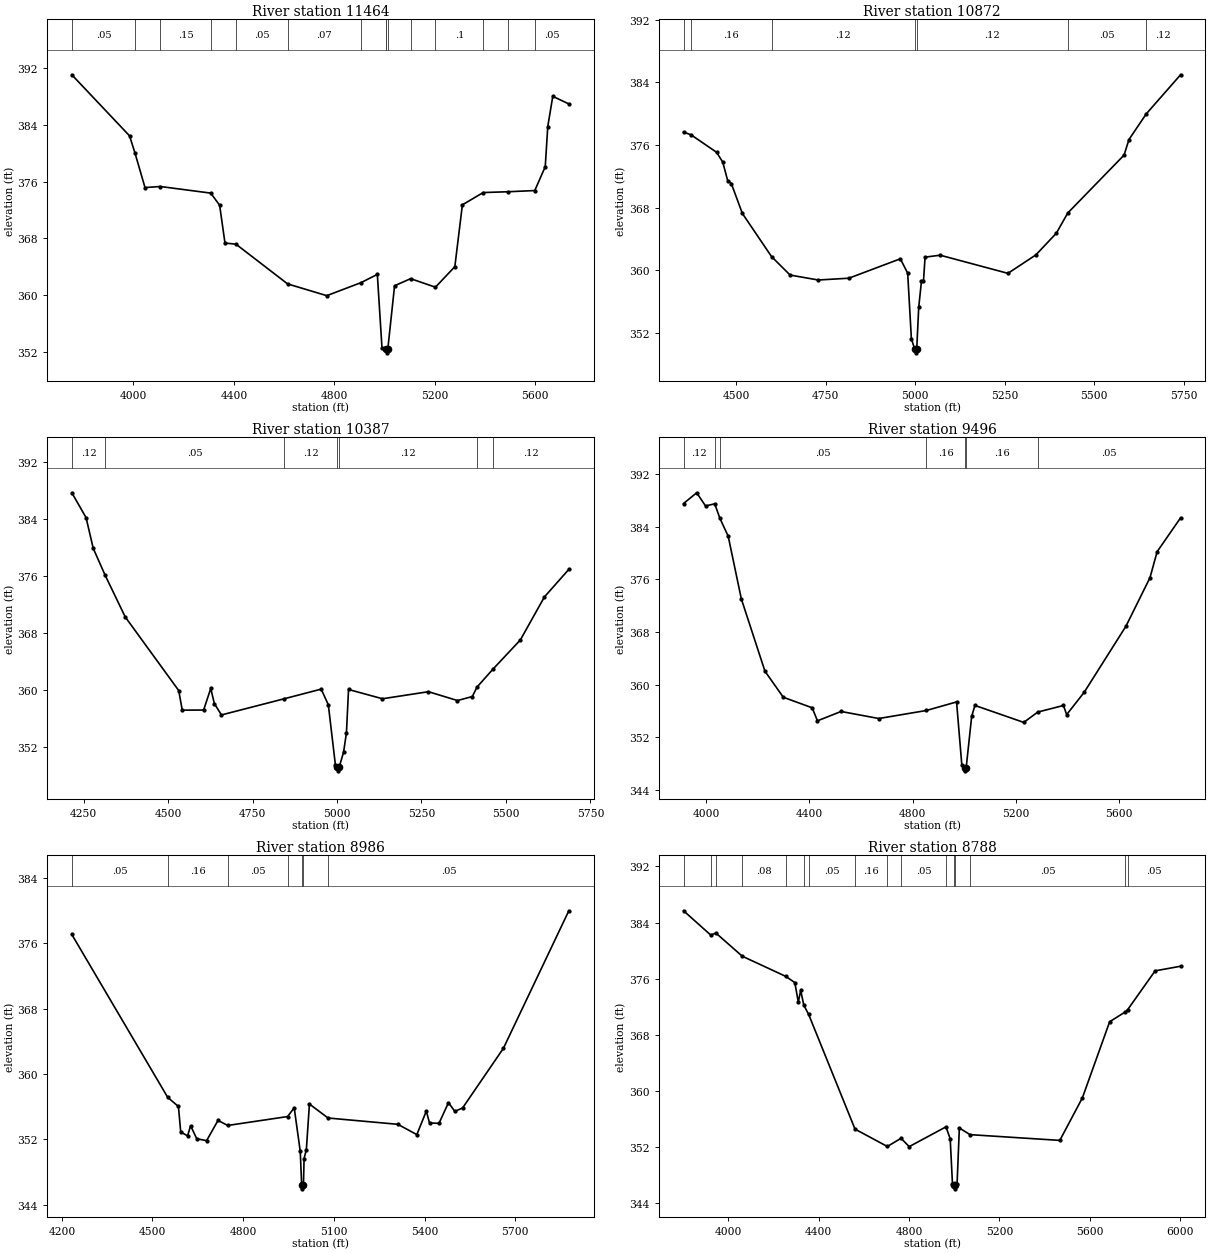
Type RM Length L Ch R = 1 ,11464   ,592,592,592
BEGIN DESCRIPTION:
UNT 069 IN UKCR 16.0
END DESCRIPTION:
XS GIS Cut Line= 3
        3617644.     10595357.05      3616803.77     10595169.56
      3615685.75     10595155.67
#Sta/Elev= 30
  3754.6  391.01  3984.5  382.42  4006.3  379.98    4046  375.15  4106.8   375.3
  4307.7  374.37  4343.1  372.67  4364.4  367.35  4408.2  367.19  4613.9   361.6
  4769.7  359.95  4905.9  361.78  4971.1  362.94  4989.7  352.56  5004.7  352.42
  5006.7  352.41  5009.4  351.91  5012.7  352.41  5039.7  361.34  5103.6  362.34
  5202.5  361.14  5279.7  364.03  5309.7  372.72  5392.6  374.45    5490  374.56
    5598  374.73  5639.7  378.09  5649.7  383.73  5669.7  387.98  5733.6  386.91
#Mann= 15 ,-1 , 0
  3754.6     .05       0  4006.3      .1       0  4106.8     .15       0
  4307.7      .1       0  4408.2     .05       0  4613.9     .07       0
  4905.9     .05       0  5004.7     .16       0  5006.7     .03       0
  5012.7     .16       0  5103.6     .07       0  5202.5      .1       0
  5392.6     .15       0    5490      .1       0    5598     .05       0
Bank Sta=5006.7,5012.7
XS Rating Curve= 0 ,0
Exp/Cntr=0.3,0.1

Type RM Length L Ch R = 1 ,10872   ,485,485,485
BEGIN DESCRIPTION:
UNT 069 IN UKCR 15.0
END DESCRIPTION:
XS GIS Cut Line= 3
      3616999.62     10594460.19      3616349.61     10594610.19
      3615749.61     10595010.19
#Sta/Elev= 30
  4353.3  377.66  4374.4   377.3  4445.7  375.07  4462.8  373.81  4476.5  371.46
  4486.7  371.08  4517.5  367.26  4599.1  361.74  4650.9  359.38  4729.6  358.75
  4815.1  358.98  4958.8  361.46  4979.3  359.62  4989.6  351.27  4998.6  349.94
  5001.3  349.44  5004.6  349.94  5010.1  355.25  5017.8   358.6  5023.4   358.6
  5027.9  361.67    5070  361.92  5259.3   359.6  5337.4  361.96  5394.5  364.73
  5426.4  367.31  5583.8  374.72  5597.3   376.7  5645.8  379.99  5741.5  384.98
#Mann= 7 ,-1 , 0
  4353.3     .12       0  4374.4     .16       0  4599.1     .12       0
  4998.6     .07       0  5004.6     .12       0  5426.4     .05       0
  5645.8     .12       0
Bank Sta=4998.6,5004.6
XS Rating Curve= 0 ,0
Exp/Cntr=0.3,0.1

Type RM Length L Ch R = 1 ,10387   ,891,891,891
BEGIN DESCRIPTION:
UNT 069 IN UKCR 14.0
END DESCRIPTION:
XS GIS Cut Line= 3
      3616949.63     10593960.18      3616199.61     10594210.19
      3615799.59     10594760.21
#Sta/Elev= 30
  4215.3  387.66  4257.5  384.17  4278.6  379.87  4313.9  376.09  4373.4  370.24
  4531.6  359.92  4542.1  357.17  4605.3  357.19  4626.4  360.22    4637   358.1
    4658   356.5  4843.9  358.77  4953.2  360.12  4974.3  357.93  4995.4  349.42
  5000.3  349.16    5003  348.66  5006.3  349.16  5019.4  351.27  5027.9  353.98
  5034.1  360.07  5134.6  358.77  5270.6  359.76  5356.4  358.52  5400.4  359.08
  5414.2   360.4  5461.2  362.91  5542.6  367.02  5613.7  373.05    5686  376.92
#Mann= 7 ,-1 , 0
  4215.3     .12       0  4313.9     .05       0  4843.9     .12       0
  5000.3     .07       0  5006.3     .12       0  5414.2     .16       0
  5461.2     .12       0
Bank Sta=5000.3,5006.3
XS Rating Curve= 0 ,0
Exp/Cntr=0.3,0.1

Type RM Length L Ch R = 1 ,9496    ,510,510,510
BEGIN DESCRIPTION:
UNT 069 IN UKCR 13.0
END DESCRIPTION:
XS GIS Cut Line= 3
       3616999.6     10593910.19      3615899.61     10593710.19
      3615099.56     10593610.18
#Sta/Elev= 30
  3913.4  387.53  3964.2  389.16  3998.5  387.16  4034.1  387.48  4053.9   385.3
  4086.2  382.56    4137  373.05  4228.5  362.05  4299.6  358.09  4411.4  356.49
  4431.8  354.51  4523.2  355.93  4669.3  354.86  4853.6  356.08  4970.4  357.38
  4990.8   347.8  5001.7  347.41  5004.5  346.91  5007.7  347.41  5028.9  355.18
  5041.5  356.85  5230.5  354.27  5284.8  355.84  5384.2  356.84  5396.7  355.45
  5464.8  358.86    5626  368.87  5719.2  376.25    5747  380.21  5837.7  385.35
#Mann= 7 ,-1 , 0
  3913.4     .12       0  4034.1     .08       0  4053.9     .05       0
  4853.6     .16       0  5001.7     .07       0  5007.7     .16       0
  5284.8     .05       0
Bank Sta=5001.7,5007.7
XS Rating Curve= 0 ,0
Exp/Cntr=0.3,0.1

Type RM Length L Ch R = 1 ,8986    ,198,198,198
BEGIN DESCRIPTION:
UNT 069 IN UKCR 12.0
END DESCRIPTION:
XS GIS Cut Line= 3
       3616799.6     10593410.19      3615999.61     10593310.19
      3615199.58      10593560.2
#Sta/Elev= 30
  4233.1  377.06  4550.4  357.14  4585.8  356.03  4593.4  352.91    4616  352.44
  4626.1  353.68  4646.3  352.09    4679  351.85  4716.8  354.33  4748.8  353.71
  4947.2   354.8  4968.8  355.88  4988.9  350.53  4993.5  346.46  4996.2  345.96
  4999.5  346.46  5001.5  349.66  5009.1  350.77  5019.2  356.33  5080.9  354.62
  5311.7  353.85  5374.6  352.59    5406  355.47  5416.5  354.01  5447.9  353.97
  5479.3   356.5  5500.3  355.43    5526  355.85  5661.1  363.15  5877.5  379.96
#Mann= 7 ,-1 , 0
  4233.1     .05       0  4550.4     .16       0  4748.8     .05       0
  4947.2     .16       0  4993.5     .07       0  4999.5     .16       0
  5080.9     .05       0
Bank Sta=4993.5,4999.5
XS Rating Curve= 0 ,0
Exp/Cntr=0.3,0.1

Type RM Length L Ch R = 1 ,8788    ,303,303,303
BEGIN DESCRIPTION:
UNT 069 IN UKCR 11.0
END DESCRIPTION:
XS GIS Cut Line= 4
      3617213.48     10593454.28      3616338.49     10593176.51
      3615831.55     10593100.12      3615067.66     10593016.78
#Sta/Elev= 30
  3802.1  385.68  3922.3  382.22  3945.7  382.49  4061.8   379.2  4253.2  376.34
  4294.4  375.44  4309.8  372.66  4320.3  374.32  4334.1  372.22  4355.7  370.89
  4560.7  354.54  4703.8  352.06  4764.3  353.23  4800.5  352.04  4963.2  354.86
  4981.9  353.16    4992  346.69  4999.3  346.52  5002.1  346.02  5005.3  346.52
  5012.3   346.7  5022.4   354.7  5069.6  353.75  5466.9  352.93  5566.7  358.99
  5687.4  369.85  5756.8  371.26  5767.4  371.59  5888.6  377.11  6001.2  377.77
#Mann= 16 ,-1 , 0
  3802.1     .05       0  3922.3     .08       0  3945.7     .05       0
  4061.8     .08       0  4253.2     .05       0  4334.1     .08       0
  4355.7     .05       0  4560.7     .16       0  4703.8     .08       0
  4764.3     .05       0  4963.2     .16       0  4999.3     .07       0
  5005.3     .16       0  5069.6     .05       0  5756.8     .08       0
  5767.4     .05       0
Bank Sta=4999.3,5005.3
XS Rating Curve= 0 ,0
Exp/Cntr=0.3,0.1

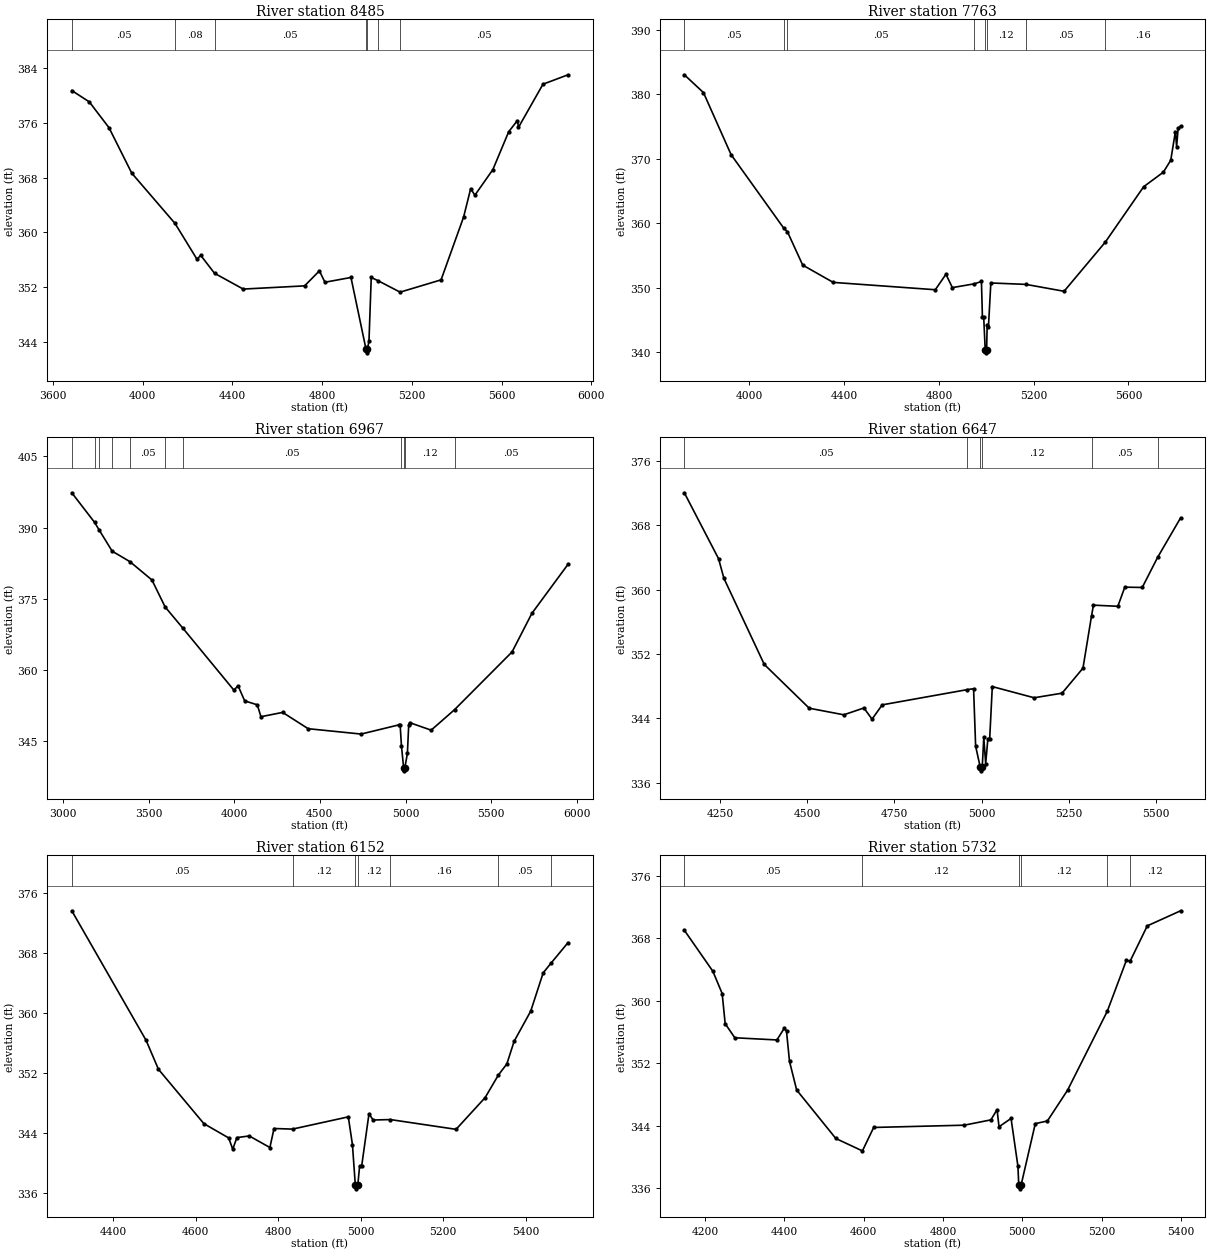
Type RM Length L Ch R = 1 ,8485    ,722,722,722
BEGIN DESCRIPTION:
UNT 069 IN UKCR 10.0
END DESCRIPTION:
XS GIS Cut Line= 3
      3617171.83     10593259.84      3616144.05     10592898.73
      3615025.97     10592794.56
#Sta/Elev= 30
  3684.3  380.77  3762.4  379.11  3850.1  375.33  3951.6  368.67  4144.6   361.3
  4242.2  356.07    4259  356.63  4320.7     354  4448.5  351.69  4722.1  352.16
  4788.2  354.36  4812.6  352.69  4928.8  353.39  4996.1  342.85  4998.8  342.35
  5002.1  342.85  5009.1   344.1  5019.2  353.39  5049.9  352.91  5147.9  351.24
  5330.5  353.04  5430.9  362.24  5462.4  366.39  5481.2  365.44  5561.5   369.2
  5631.8  374.73  5670.6  376.37  5675.6  375.38  5784.8   381.7  5896.6  383.08
#Mann= 7 ,-1 , 0
  3684.3     .05       0  4144.6     .08       0  4320.7     .05       0
  4996.1     .03       0  5002.1     .05       0  5049.9     .12       0
  5147.9     .05       0
Bank Sta=4996.1,5002.1
XS Rating Curve= 0 ,0
Exp/Cntr=0.3,0.1

Type RM Length L Ch R = 1 ,7763    ,796,796,796
BEGIN DESCRIPTION:
UNT 069 IN UKCR 9.0
END DESCRIPTION:
XS GIS Cut Line= 3
      3617144.06     10593148.73      3616102.38      10592440.4
      3615299.63      10592210.2
#Sta/Elev= 30
  3725.5  383.03  3806.2  380.27  3922.9  370.64  4144.4  359.27  4160.7  358.68
  4225.2   353.5    4354  350.82    4785  349.68  4829.8  352.08  4856.9  350.01
  4949.8   350.6  4979.6  350.96  4983.8  345.43  4989.2  345.43  4995.5  340.39
  4998.2  339.89  5001.5  340.39  5003.9  344.27  5009.1  343.85  5019.3  350.73
  5167.5  350.51  5328.4  349.44  5502.1  357.05  5664.3  365.66  5747.5  367.92
  5778.7  369.77  5798.3  374.21  5803.5   371.9  5809.9  374.74  5820.3  375.06
#Mann= 8 ,-1 , 0
  3725.5     .05       0  4144.4     .08       0  4160.7     .05       0
  4949.8     .12       0  4995.5     .07       0  5001.5     .12       0
  5167.5     .05       0  5502.1     .16       0
Bank Sta=4995.5,5001.5
XS Rating Curve= 0 ,0
Exp/Cntr=0.3,0.1

Type RM Length L Ch R = 1 ,6967    ,320,320,320
BEGIN DESCRIPTION:
UNT 069 IN UKCR 8.0
END DESCRIPTION:
XS GIS Cut Line= 3
       3617935.7     10592405.67      3615942.66     10591732.06
       3615199.6     10592010.19
#Sta/Elev= 30
  3051.8  397.33  3184.5  391.12  3211.1  389.53  3287.5  385.04  3390.6  382.85
  3519.6  378.98  3596.7   373.3  3699.7  368.86  3997.7  355.81  4022.8  356.69
    4061  353.54  4134.9   352.7    4156   350.2  4282.7  351.11  4431.6  347.68
  4740.8  346.55    4961  348.48  4968.8  348.41  4976.2  344.08  4989.4  339.31
  4992.2  338.81  4995.4  339.31    5011  342.46  5018.6  348.38  5023.9  348.96
  5149.7  347.37  5286.2  351.68  5622.1  363.84  5737.9  371.96    5949  382.29
#Mann= 11 ,-1 , 0
  3051.8     .05       0  3184.5     .08       0  3211.1     .05       0
  3287.5      .1       0  3390.6     .05       0  3596.7     .16       0
  3699.7     .05       0  4976.2     .12       0  4989.4     .07       0
  4995.4     .12       0  5286.2     .05       0
Bank Sta=4989.4,4995.4
XS Rating Curve= 0 ,0
Exp/Cntr=0.3,0.1

Type RM Length L Ch R = 1 ,6647    ,495,495,495
BEGIN DESCRIPTION:
UNT 069 IN UKCR 7.0
END DESCRIPTION:
XS GIS Cut Line= 3
       3616949.6     10591160.19      3616149.61     10591510.19
      3615599.61     10591510.19
#Sta/Elev= 30
  4147.5  372.05  4245.7  363.85  4260.9  361.42  4376.7   350.7  4505.7  345.25
  4604.8  344.43  4662.5  345.28  4685.8  343.89  4715.1  345.67  4958.6  347.56
    4977  347.68  4982.9  340.53  4995.9  337.96  4998.6  337.46  5001.9  337.96
  5006.3  341.61  5011.7  338.35    5018  341.45  5023.2  341.45  5030.7  347.94
  5150.7  346.55  5230.7  347.12  5290.7  350.23  5315.2  356.72  5320.7  358.07
  5390.7  357.93  5410.7  360.31  5460.7  360.27  5504.6     364  5570.7  368.93
#Mann= 6 ,-1 , 0
  4147.5     .05       0  4958.6     .12       0  4995.9     .07       0
  5001.9     .12       0  5315.2     .05       0  5504.6     .12       0
Bank Sta=4995.9,5001.9
XS Rating Curve= 0 ,0
Exp/Cntr=0.3,0.1

Type RM Length L Ch R = 1 ,6152    ,420,420,420
BEGIN DESCRIPTION:
UNT 069 IN UKCR 6.0
END DESCRIPTION:
XS GIS Cut Line= 3
      3616949.57     10591110.19      3616249.61     10591110.19
      3615749.56     10591060.18
#Sta/Elev= 30
    4300   373.6    4480  356.36    4510   352.5    4620  345.27    4680  343.37
    4690  341.87    4700  343.41    4730  343.63    4780  342.09    4790  344.62
  4834.8  344.54    4970  346.17    4980  342.48    4987  337.09  4989.7  336.59
    4993  337.09  4997.5  339.67  5002.5  339.67  5020.1  346.58  5030.1  345.75
  5071.8  345.81  5231.1  344.51  5301.5  348.73  5333.8  351.75  5354.2  353.22
  5371.8  356.23    5412  360.24  5442.2  365.34  5460.8   366.6  5502.5  369.37
#Mann= 7 ,-1 , 0
    4300     .05       0  4834.8     .12       0    4987     .07       0
    4993     .12       0  5071.8     .16       0  5333.8     .05       0
  5460.8     .12       0
Bank Sta=4987,4993
XS Rating Curve= 0 ,0
Exp/Cntr=0.3,0.1

Type RM Length L Ch R = 1 ,5732    ,738,738,738
BEGIN DESCRIPTION:
UNT 069 IN UKCR 5.0
END DESCRIPTION:
XS GIS Cut Line= 3
      3616899.59     10591060.18      3616206.55      10590815.4
      3615699.64     10590910.18
#Sta/Elev= 30
  4148.2  369.02  4220.2  363.77  4243.6  360.92  4251.1  357.08  4275.4  355.27
  4381.5  354.99  4400.4  356.51  4405.7   356.1  4413.3  352.24  4431.3  348.59
    4530  342.39    4597   340.8  4625.4   343.8  4853.6  344.09  4920.8  344.77
  4936.3  346.08  4941.3  343.89  4971.6  344.95  4988.9  338.85    4991  336.45
  4993.7  335.95    4997  336.45  5032.7  344.29  5063.2  344.63  5114.1  348.57
  5214.2  358.67  5262.3  365.18  5271.7  365.07  5314.9  369.58  5398.9  371.51
#Mann= 6 ,-1 , 0
  4148.2     .05       0    4597     .12       0    4991     .07       0
    4997     .12       0  5214.2     .05       0  5271.7     .12       0
Bank Sta=4991,4997
XS Rating Curve= 0 ,0
Exp/Cntr=0.3,0.1

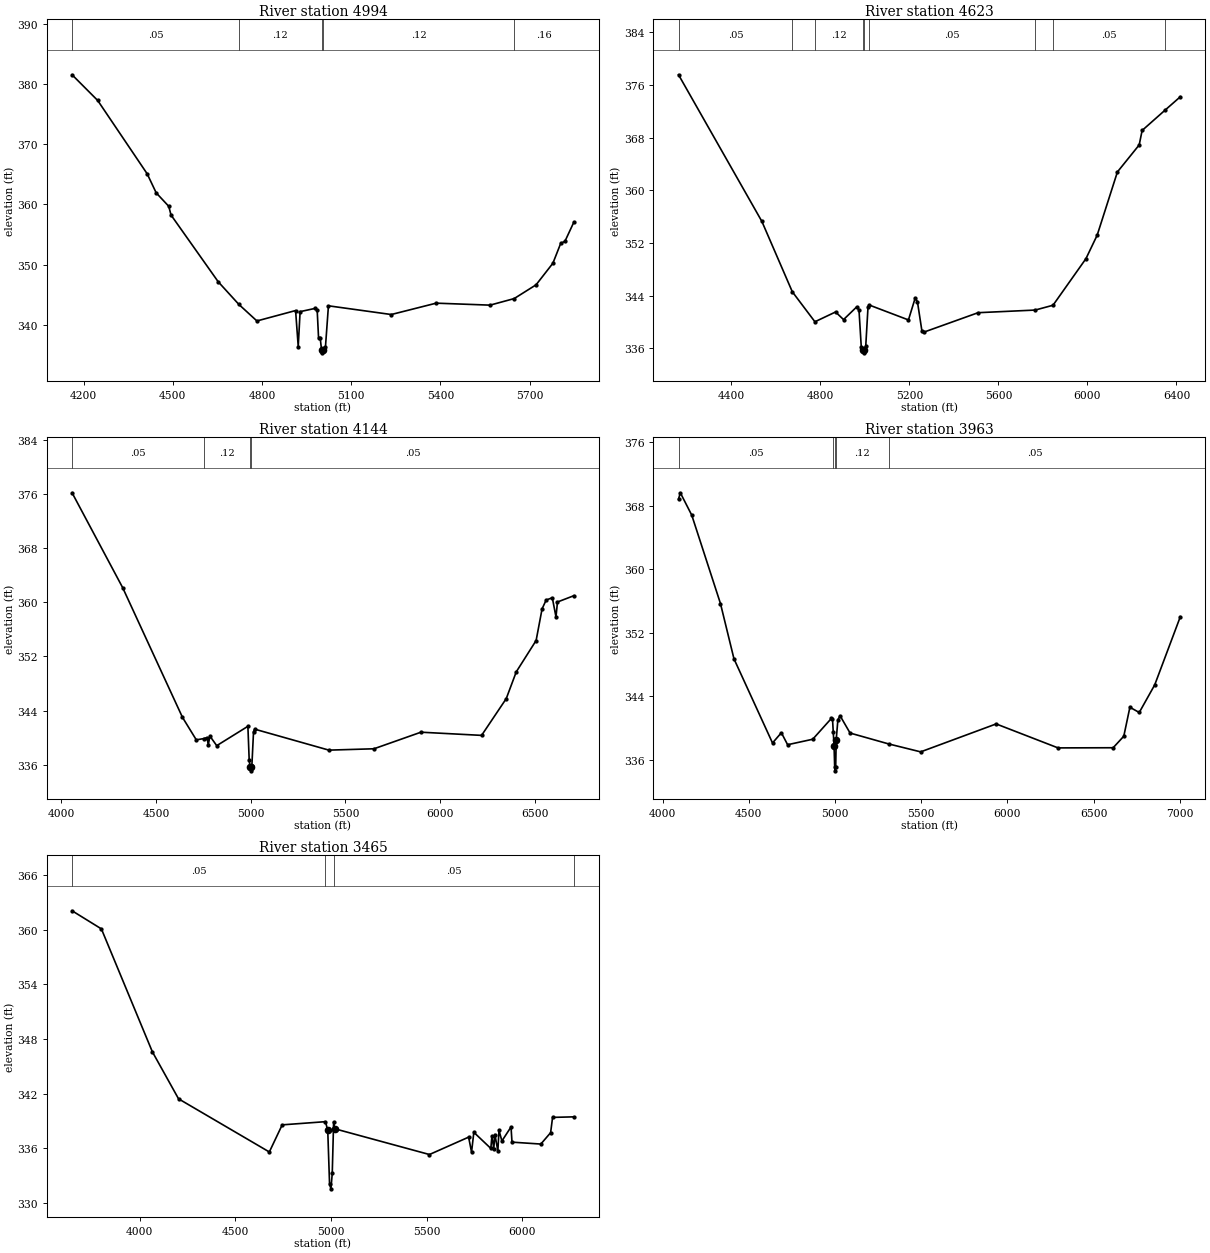
Type RM Length L Ch R = 1 ,4994    ,371,371,371
BEGIN DESCRIPTION:
UNT 069 IN UKCR 4.0
END DESCRIPTION:
XS GIS Cut Line= 3
      3617149.61     10590860.19      3616449.61     10590410.19
      3615599.64     10590310.19
#Sta/Elev= 30
    4161  381.56  4247.2  377.29  4413.6   365.1    4444  361.93  4486.3  359.69
  4493.9  358.24  4652.7  347.14  4722.3  343.37  4782.8  340.63  4912.9  342.36
  4921.8  336.38  4928.1  342.18  4979.6  342.73  4985.6  342.38  4990.2  337.79
  4995.7  337.79  5000.2  335.83    5003  335.33  5006.2  335.83  5013.3  336.25
  5023.4  343.15  5234.8   341.7  5385.9  343.59  5567.1  343.26  5648.2  344.35
  5721.9  346.64  5778.5  350.23    5805  353.56  5818.8  353.85    5849  357.06
#Mann= 5 ,-1 , 0
    4161     .05       0  4722.3     .12       0  5000.2     .07       0
  5006.2     .12       0  5648.2     .16       0
Bank Sta=5000.2,5006.2
XS Rating Curve= 0 ,0
Exp/Cntr=0.3,0.1

Type RM Length L Ch R = 1 ,4623    ,479,479,479
BEGIN DESCRIPTION:
UNT 069 IN UKCR 3.0
END DESCRIPTION:
XS GIS Cut Line= 3
      3617149.62     10590760.21      3616699.61     10590110.19
      3615249.63     10590310.19
#Sta/Elev= 30
  4162.9  377.56  4537.3  355.28    4674  344.59  4775.6  340.03  4868.4  341.52
  4904.2  340.36  4963.6   342.3  4973.7  341.78  4983.8  336.22  4991.5  335.81
  4994.3  335.31  4997.5  335.81    5004  336.35  5014.1  342.26  5020.7  342.56
  5195.8  340.31  5226.1  343.64  5236.1  343.09  5256.3  338.63  5266.4  338.47
  5508.7  341.41  5765.1  341.81  5845.2  342.54  5993.2  349.62  6043.7  353.19
  6134.6   362.8  6232.4   366.9  6245.6   369.1  6348.1  372.17  6417.2  374.22
#Mann= 9 ,-1 , 0
  4162.9     .05       0    4674     .16       0  4775.6     .12       0
  4991.5     .07       0  4997.5     .12       0  5020.7     .05       0
  5765.1     .16       0  5845.2     .05       0  6348.1     .12       0
Bank Sta=4991.5,4997.5
XS Rating Curve= 0 ,0
Exp/Cntr=0.3,0.1

Type RM Length L Ch R = 1 ,4144    ,181,181,181
BEGIN DESCRIPTION:
UNT 069 IN UKCR 2.0
END DESCRIPTION:
XS GIS Cut Line= 3
      3617449.59     10590510.16      3616899.61     10589710.19
      3615299.61     10590210.19
#Sta/Elev= 30
  4057.7  376.19  4324.6  362.17  4640.2     343    4713  339.68  4751.3  339.86
  4770.1  340.01  4776.1  338.92    4785  340.23  4820.8  338.82  4985.2  341.68
  4992.1  336.68  4997.1   335.6  4999.8   335.1  5003.1   335.6  5006.2  335.85
    5015  340.89    5021  341.26  5412.5  338.16  5650.3  338.36  5898.1  340.81
  6218.1  340.34  6348.1  345.77    6401  349.73  6505.7  354.36  6537.2  359.04
  6558.6  360.34  6591.1  360.68  6610.5  357.85  6618.4  360.05  6704.8  360.98
#Mann= 4 ,-1 , 0
  4057.7     .05       0  4751.3     .12       0  4997.1     .03       0
  5003.1     .05       0
Bank Sta=4997.1,5003.1
XS Rating Curve= 0 ,0
Exp/Cntr=0.3,0.1

Type RM Length L Ch R = 1 ,3963    ,498,498,498
BEGIN DESCRIPTION:
Mapping XS 417d43b8
END DESCRIPTION:
XS GIS Cut Line= 4
      3617539.87     10590294.54      3617116.27     10589641.78
      3616574.61     10589322.34      3615227.42     10589988.99
#Sta/Elev= 30
  4092.5  368.86  4102.9  369.65  4169.2  366.83  4335.6   355.7    4414  348.73
  4637.5  338.13  4688.9  339.42  4725.1  337.91  4870.7   338.6  4979.6  341.24
  4985.4  341.18  4989.9  339.47  4994.5  337.73    4998  335.12  5000.8  334.62
    5004  335.12  5006.8  338.51  5016.7  341.05  5029.3  341.56  5087.4  339.38
  5311.2  338.01  5496.7  337.01  5934.5  340.53  6293.4  337.51    6613  337.53
  6674.7  338.98  6710.1  342.63  6764.4  341.97  6854.1  345.45  7002.6  354.04
#Mann= 5 ,-1 , 0
  4092.5     .05       0  4989.9     .12       0    4998     .07       0
    5004     .12       0  5311.2     .05       0
Bank Sta=4994.5,5006.8
XS Rating Curve= 0 ,0
Exp/Cntr=0.3,0.1

Type RM Length L Ch R = 1 ,3465    ,1558,1558,1558
BEGIN DESCRIPTION:
Mapping XS 4a6b6a99
END DESCRIPTION:
XS GIS Cut Line= 4
      3617741.27     10590308.43      3617498.22      10589377.9
      3616380.16      10588690.4      3616041.06     10588765.55
#Sta/Elev= 30
  3647.4  362.08  3800.6  360.09  4066.8  346.59  4203.7  341.42    4678  335.58
  4745.2  338.56  4971.3  338.91  4983.2  337.95  4992.6  332.08  4999.8  331.53
  5006.7  333.22  5013.9   338.9  5019.7  338.13  5514.5   335.3  5719.2  337.21
  5734.5  335.56  5746.4  337.74  5835.2  335.97  5841.1  337.36  5850.6  335.96
  5856.5   337.5  5871.9  335.69  5877.8  337.95  5893.2  336.79  5940.7  338.33
  5945.8  336.66  6096.4  336.45  6147.6   337.7  6157.8  339.38    6269  339.44
#Mann= 4 ,-1 , 0
  3647.4     .05       0  4971.3     .03       0  5013.9     .05       0
    6269      .1       0
Bank Sta=4983.2,5019.7
XS Rating Curve= 0 ,0
Exp/Cntr=0.3,0.1