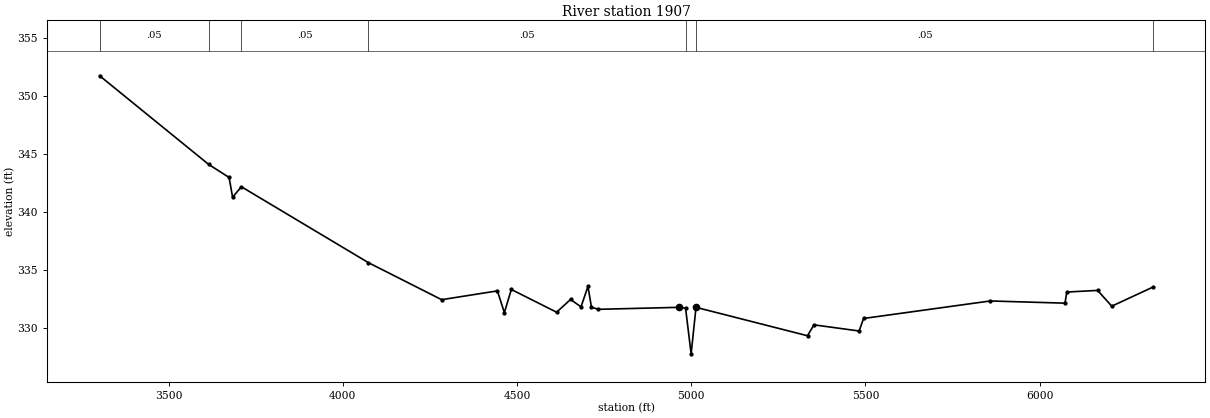
HEC-RAS study UNT 069 IN UKCR.prj: UNT 069 IN UKCR Base Level Engineering

--- UNT 069 IN UKCR.g01 (geometry) --- (continued)

Type RM Length L Ch R = 1 ,1907    ,0,0,0
BEGIN DESCRIPTION:
UNT 069 IN UKCR 1.0
END DESCRIPTION:
XS GIS Cut Line= 3
      3618116.27     10590141.75      3618147.02     10588099.25
      3617184.03     10588281.44
#Sta/Elev= 30
    3302  351.75  3614.8  344.11  3673.6  342.98  3683.6  341.28  3708.9  342.18
  4073.6  335.63  4283.7  332.44  4443.7   333.2  4463.7  331.32  4483.7  333.32
  4613.7  331.36  4653.7  332.46  4683.7  331.82  4703.7  333.59  4713.7  331.79
  4733.7  331.61  4963.7  331.78  4983.8  331.71  4999.8  327.77  5013.8  331.78
  5333.8  329.33  5352.3  330.27  5481.9  329.74  5494.8  330.82  5858.4  332.33
  6072.9  332.14    6078   333.1  6166.5  333.24  6207.2  331.88  6324.8  333.52
#Mann= 7 ,-1 , 0
    3302     .05       0  3614.8     .08       0  3708.9     .05       0
  4073.6     .05       0  4983.8     .03       0  5013.8     .05       0
  6324.8     .05       0
Bank Sta=4963.7,5013.8
XS Rating Curve= 0 ,0
Exp/Cntr=0.3,0.1

Chan Stop Cuts=-1
Use User Specified Reach Order=0
Composite Channel Slope=5