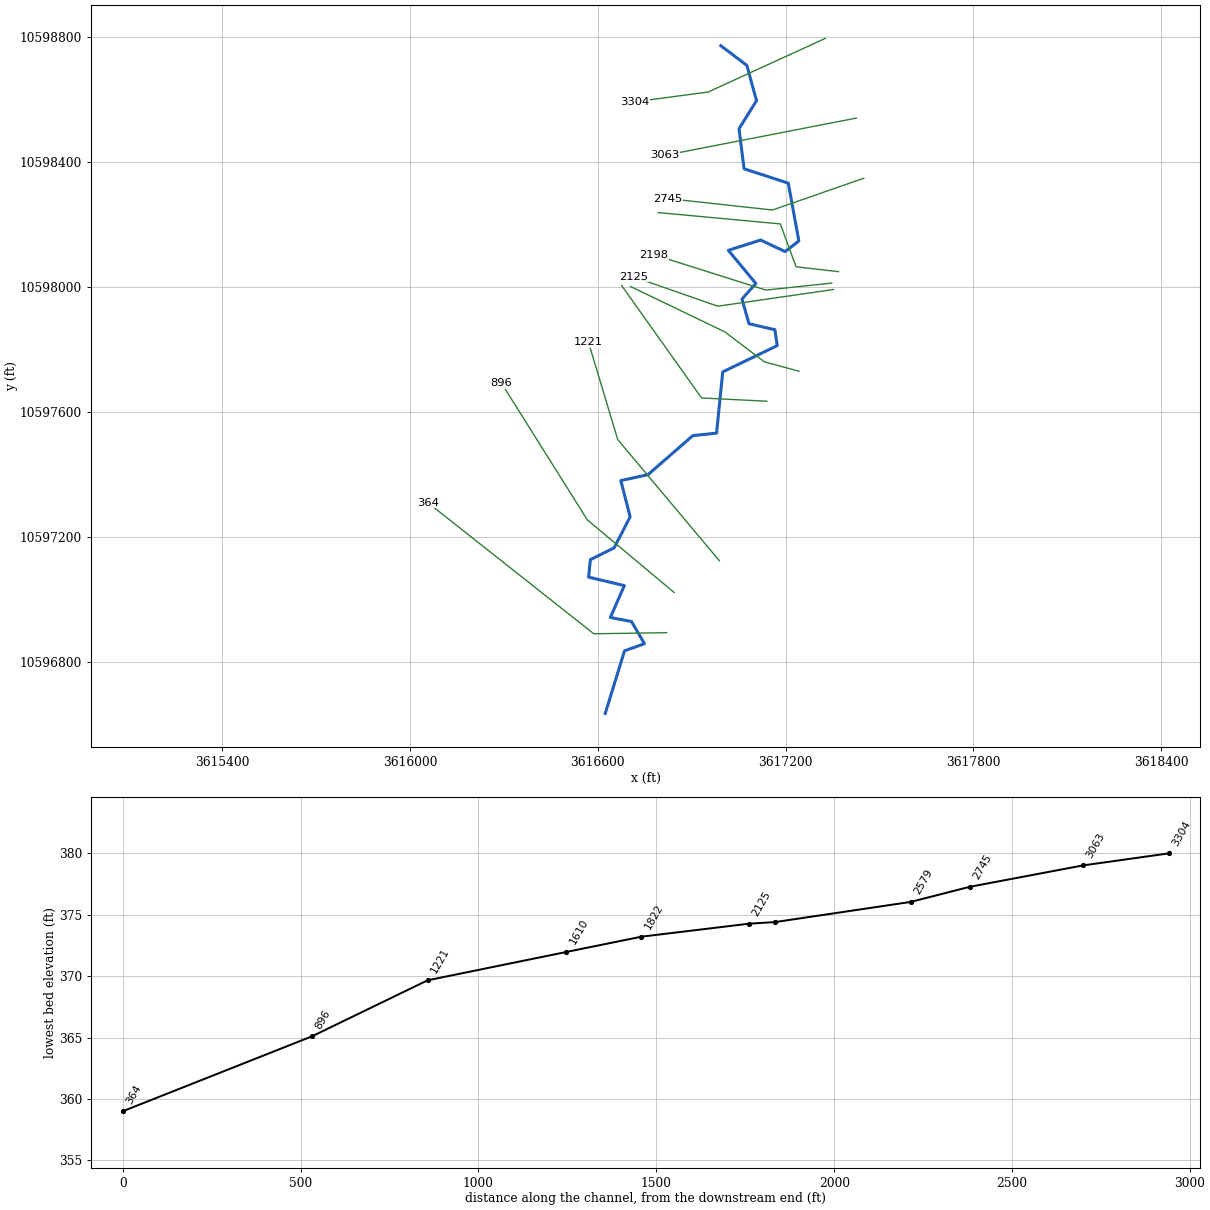
--- UNT 070 IN UKCR.prj (project) ---

Proj Title=UNT 070 IN UKCR Base Level Engineering
Current Plan=p01
Default Exp/Contr=0.3,0.1
English Units
Geom File=g01
Flow File=f01
Plan File=p01
Y Axis Title=Elevation
X Axis Title(PF)=Main Channel Distance
X Axis Title(XS)=Station
BEGIN DESCRIPTION:
UNT 070 IN UKCR
END DESCRIPTION:
DSS Export Rating Curves= 0
DSS Export Rating Curve Sorted= 0
DSS Export Volume Flow Curves= 0
DXF OffsetX= 0
DXF OffsetY= 0
DXF ScaleX= 1
DXF ScaleY= 10

--- UNT 070 IN UKCR.p01 (plan) ---

Plan Title=Multiple Run
Short Identifier=Multiple
Geom File=g01
Flow File=f01
Subcritical Flow
K Sum by GR= 0
Std Step Tol= 0.01
Critical Tol= 0.01
Num of Std Step Trials= 20
Max Error Tol= 0.3
Flow Tol Ratio= 0.001
Split Flow NTrial= 30
Split Flow Tol= 0.02
Split Flow Ratio= 0.02
Log Output Level= 0
Friction Slope Method= 1
Unsteady Friction Slope Method= 2
Unsteady Bridges Friction Slope Method= 1
Parabolic Critical Depth
Global Vel Dist=  1 , 1 , 1
Global Log Level= 0
CheckData=True
Encroach Param= -1, 0, 0, 0
BEGIN DESCRIPTION:
Multiple Run
END DESCRIPTION:

--- UNT 070 IN UKCR.f01 (steady flow) ---

Flow Title=Multiple
Program Version=4.10
Number of Profiles= 7
Profile Names=10-year,25-year,50-year,1pct_min,100-year,1pct_plu,500-year
River Rch & RM=UNT 070 IN UKCR,Reach-1         ,3304
     498     653     775     674     911    1233    1253
Boundary for River Rch & Prof#=UNT 070 IN UKCR,Reach-1         , 1
Up Type= 0
Dn Type= 3
Dn Slope=0.005
Boundary for River Rch & Prof#=UNT 070 IN UKCR,Reach-1         , 2
Up Type= 0
Dn Type= 3
Dn Slope=0.005
Boundary for River Rch & Prof#=UNT 070 IN UKCR,Reach-1         , 3
Up Type= 0
Dn Type= 3
Dn Slope=0.005
Boundary for River Rch & Prof#=UNT 070 IN UKCR,Reach-1         , 4
Up Type= 0
Dn Type= 3
Dn Slope=0.005
Boundary for River Rch & Prof#=UNT 070 IN UKCR,Reach-1         , 5
Up Type= 0
Dn Type= 3
Dn Slope=0.005
Boundary for River Rch & Prof#=UNT 070 IN UKCR,Reach-1         , 6
Up Type= 0
Dn Type= 3
Dn Slope=0.005
Boundary for River Rch & Prof#=UNT 070 IN UKCR,Reach-1         , 7
Up Type= 0
Dn Type= 3
Dn Slope=0.005
DSS Import GetInterval= 0
DSS Import GetPeak= 0
DSS Import FillOption= 0

--- UNT 070 IN UKCR.g01 (geometry) ---

Geom Title=Existing Conditions

River Reach=UNT 070 IN UKCR,Reach-1
Reach XY= 30
      3616992.75     10598771.00      3617076.00     10598708.00
      3617107.00     10598595.00      3617051.00     10598505.00
      3617067.25     10598377.00      3617208.50     10598331.00
      3617242.25     10598146.00      3617198.50     10598112.00
      3617120.00     10598149.00      3617017.00     10598116.00
      3617104.75     10598010.00      3617060.50     10597960.00
      3617083.00     10597881.00      3617165.50     10597862.00
      3617173.25     10597811.00      3616999.00     10597727.00
      3616979.25     10597531.00      3616903.50     10597523.00
      3616760.00     10597398.00      3616673.25     10597379.00
      3616703.00     10597263.00      3616652.00     10597164.00
      3616576.00     10597126.00      3616570.25     10597070.00
      3616684.50     10597043.00      3616639.75     10596941.00
      3616707.25     10596928.00      3616748.75     10596857.00
      3616685.00     10596834.00      3616623.50     10596634.00

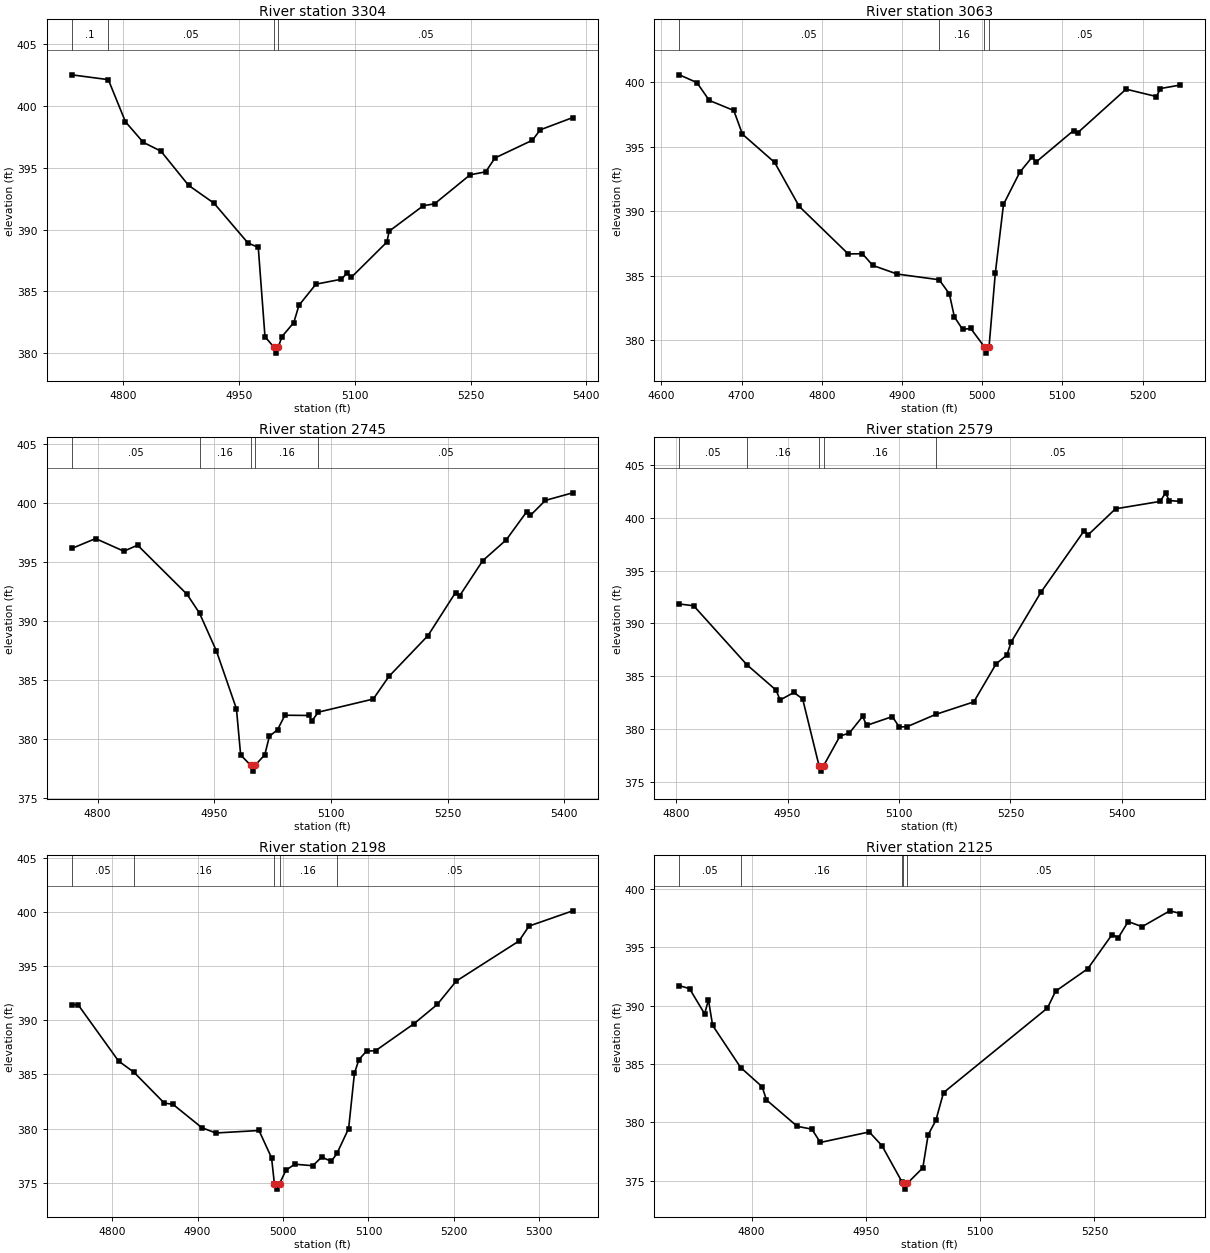
Type RM Length L Ch R = 1,3304,241,241,241
BEGIN DESCRIPTION:
UNT 070 IN UKCR 3.0
END DESCRIPTION:
XS GIS Cut Line= 3
      3617327.17     10598794.55      3616952.21     10598622.69
      3616717.85     10598591.44
#Sta/Elev= 30
  4733.5  402.52  4780.9  402.13  4803.1  398.72  4826.1  397.06  4849.1  396.34
  4884.8  393.58  4917.8  392.13  4961.8  388.91  4975.1  388.56  4983.8  381.33
  4995.1  380.50  4997.9  380.00  5001.1  380.50  5005.8  381.34  5021.1  382.47
  5027.8  383.87  5049.8  385.58  5082.8  385.98  5090.1  386.49  5095.6  386.13
  5141.6  388.98  5144.7  389.87  5188.9  391.93  5203.4  392.08  5249.5  394.43
  5269.7  394.67  5281.6  395.79  5330.2  397.23  5340.3  398.07  5382.4  399.06
#Mann=4,-1,0
  4733.5     0.1       0  4780.9    0.05       0  4995.1    0.03       0
  5001.1    0.05       0
Bank Sta=4995.1,5001.1
Exp/Cntr=0.3,0.1

Type RM Length L Ch R = 1,3063,318,318,318
BEGIN DESCRIPTION:
Mapping XS 867403fa
END DESCRIPTION:
XS GIS Cut Line= 2
      3617426.21     10598539.36      3616813.14     10598419.87
#Sta/Elev= 30
  4622.5  400.56  4644.4  399.96  4659.8  398.58  4690.4  397.80  4701.1  395.97
  4741.3  393.78  4771.9  390.38  4833.0  386.70  4850.8  386.71  4863.6  385.81
  4894.1  385.14  4946.4  384.70  4959.1  383.61  4965.4  381.82  4975.6  380.86
  4985.8  380.93  5002.6  379.52  5005.4  379.02  5008.6  379.52  5016.4  385.21
  5026.6  390.53  5046.9  393.02  5062.3  394.19  5067.4  393.82  5114.0  396.25
  5119.0  396.07  5179.4  399.45  5217.2  398.88  5222.3  399.50  5247.1  399.77
#Mann=4,-1,0
  4622.5    0.05       0  4946.4    0.16       0  5002.6    0.07       0
  5008.6    0.05       0
Bank Sta=5002.6,5008.6
Exp/Cntr=0.3,0.1

Type RM Length L Ch R = 1,2745,166,166,166
BEGIN DESCRIPTION:
Mapping XS 4ed56d50
END DESCRIPTION:
XS GIS Cut Line= 3
      3617449.62     10598346.65      3617157.94     10598245.08
      3616824.58     10598281.54
#Sta/Elev= 30
  4766.7  396.12  4797.4  396.96  4833.7  395.89  4851.4  396.40  4915.0  392.24
  4931.0  390.65  4952.8  387.44  4978.5  382.55  4983.9  378.65  4996.7  377.78
  4999.4  377.28  5002.7  377.78  5015.0  378.67  5020.8  380.22  5031.4  380.79
  5040.8  382.01  5071.9  381.99  5075.4  381.52  5083.8  382.27  5154.4  383.38
  5174.5  385.29  5224.8  388.75  5260.2  392.39  5265.3  392.10  5295.2  395.09
  5325.4  396.85  5351.5  399.21  5356.5  398.92  5375.7  400.19  5410.9  400.83
#Mann=5,-1,0
  4766.7    0.05       0  4931.0    0.16       0  4996.7    0.07       0
  5002.7    0.16       0  5083.8    0.05       0
Bank Sta=4996.7,5002.7
Exp/Cntr=0.3,0.1

Type RM Length L Ch R = 1,2579,381,381,381
BEGIN DESCRIPTION:
Mapping XS cefafe03
END DESCRIPTION:
XS GIS Cut Line= 4
      3617368.82     10598047.79      3617233.36     10598063.42
      3617183.01     10598200.58      3616792.65     10598236.85
#Sta/Elev= 30
  4804.3  391.84  4823.6  391.67  4895.2  386.10  4934.4  383.71  4940.0  382.77
  4958.5  383.48  4970.3  382.87  4992.4  376.55  4995.2  376.05  4998.4  376.55
  5020.6  379.37  5033.1  379.64  5051.1  381.22  5056.4  380.37  5091.0  381.20
  5100.2  380.24  5110.3  380.23  5149.5  381.41  5200.7  382.59  5230.8  386.19
  5245.3  387.01  5250.9  388.23  5291.0  392.94  5349.5  398.78  5354.5  398.36
  5391.5  400.83  5451.7  401.53  5458.8  402.34  5463.8  401.61  5478.8  401.53
#Mann=5,-1,0
  4804.3    0.05       0  4895.2    0.16       0  4992.4    0.07       0
  4998.4    0.16       0  5149.5    0.05       0
Bank Sta=4992.4,4998.4
Exp/Cntr=0.3,0.1

Type RM Length L Ch R = 1,2198,73,73,73
BEGIN DESCRIPTION:
Mapping XS de11c1a7
END DESCRIPTION:
XS GIS Cut Line= 3
      3617347.30     10598011.17      3617136.83     10597988.77
      3616779.54     10598101.79
#Sta/Elev= 30
  4752.7  391.44  4760.4  391.40  4807.5  386.23  4825.6  385.19  4861.0  382.35
  4871.1  382.24  4905.0  380.08  4921.3  379.59  4971.9  379.82  4986.6  377.30
  4989.9  374.91  4992.7  374.41  4995.9  374.91  5003.4  376.15  5013.7  376.71
  5034.9  376.57  5045.3  377.37  5056.5  376.97  5063.1  377.70  5076.8  380.00
  5083.6  385.10  5088.8  386.36  5097.8  387.15  5108.3  387.18  5153.4  389.68
  5180.5  391.45  5202.7  393.60  5276.1  397.30  5287.9  398.68  5339.1  400.09
#Mann=5,-1,0
  4752.7    0.05       0  4825.6    0.16       0  4989.9    0.07       0
  4995.9    0.16       0  5063.1    0.05       0
Bank Sta=4989.9,4995.9
Exp/Cntr=0.3,0.1

Type RM Length L Ch R = 1,2125,303,303,303
BEGIN DESCRIPTION:
UNT 070 IN UKCR 2.0
END DESCRIPTION:
XS GIS Cut Line= 3
      3617352.86     10597990.59      3616983.10     10597937.21
      3616714.90     10598030.95
#Sta/Elev= 30
  4705.1  391.72  4718.5  391.46  4738.3  389.30  4743.3  390.50  4748.8  388.31
  4785.6  384.70  4813.7  383.06  4819.5  381.92  4859.9  379.66  4879.0  379.42
  4890.2  378.28  4954.4  379.18  4971.1  378.00  4997.8  374.85  4998.4  374.78
  5001.1  374.28  5004.4  374.78  5024.7  376.10  5031.7  378.93  5041.8  380.17
  5051.9  382.55  5188.3  389.80  5199.0  391.24  5241.3  393.17  5273.1  396.09
  5281.5  395.84  5294.3  397.21  5312.6  396.77  5348.9  398.13  5362.8  397.90
#Mann=5,-1,0
  4705.1    0.05       0  4785.6    0.16       0  4997.8    0.05       0
  4998.4    0.03       0  5004.4    0.05       0
Bank Sta=4998.4,5004.4
Exp/Cntr=0.3,0.1

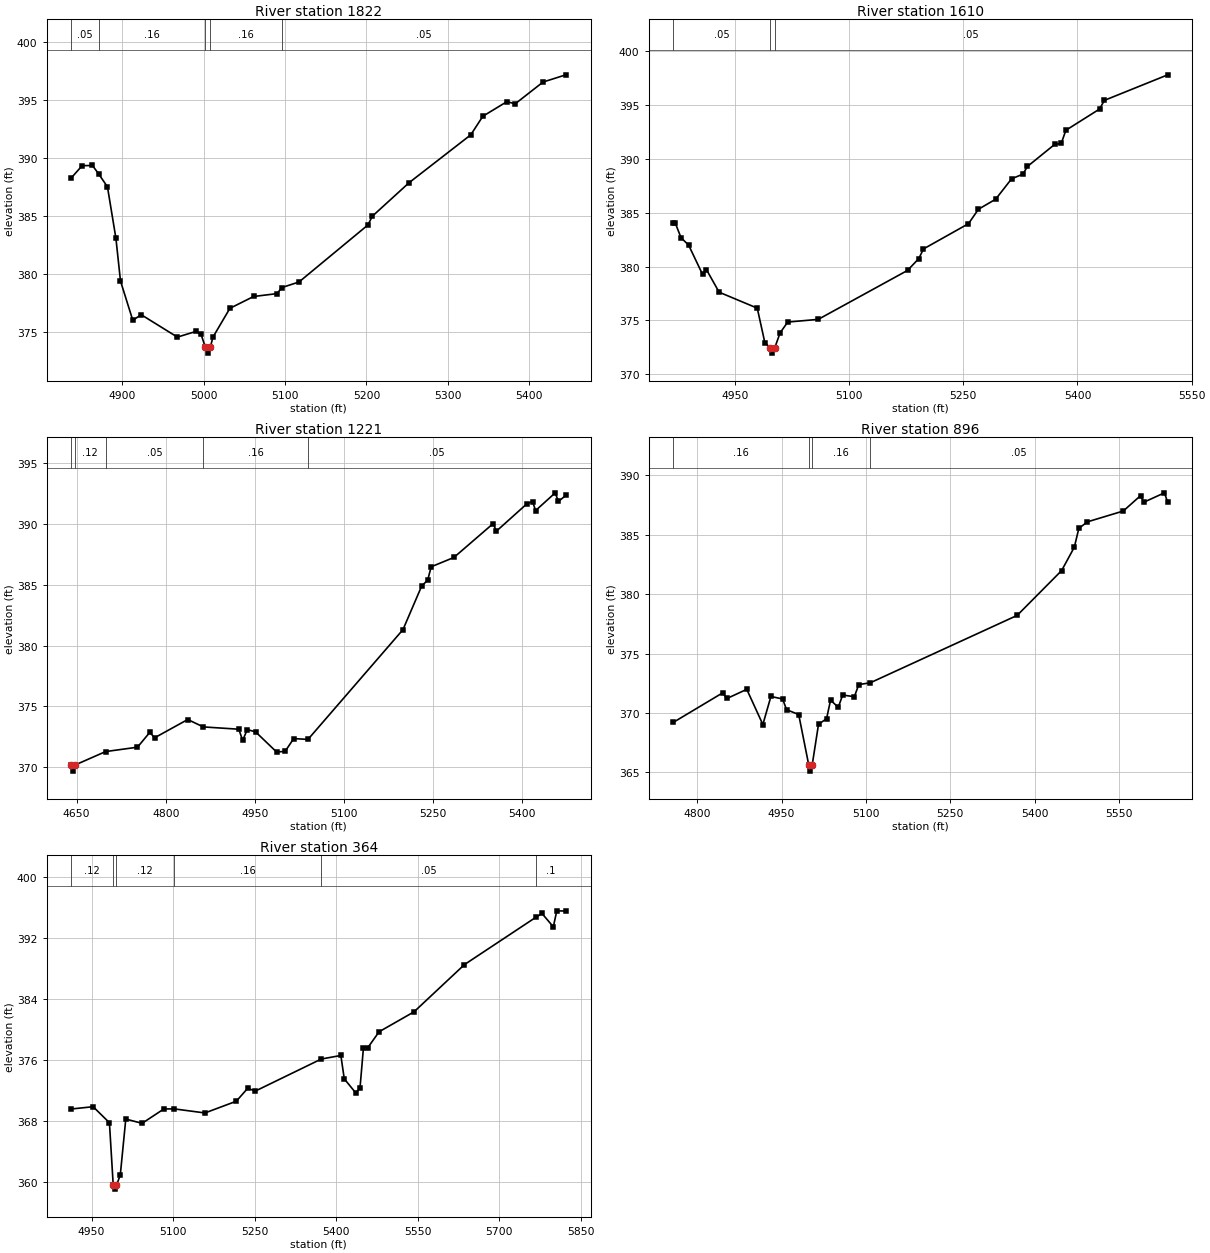
Type RM Length L Ch R = 1,1822,212,212,212
BEGIN DESCRIPTION:
Mapping XS b6359b66
END DESCRIPTION:
XS GIS Cut Line= 4
      3617242.35     10597729.09      3617131.63     10597759.48
      3617005.76     10597854.97      3616704.35     10598000.25
#Sta/Elev= 30
  4837.6  388.33  4850.8  389.37  4863.5  389.39  4871.3  388.64  4881.9  387.55
  4892.3  383.11  4897.9  379.44  4913.0  376.05  4923.4  376.53  4967.8  374.60
  4990.6  375.09  4996.9  374.83  5002.2  373.72  5004.9  373.22  5008.2  373.72
  5011.5  374.60  5032.3  377.08  5061.4  378.10  5090.5  378.35  5095.7  378.86
  5117.2  379.35  5201.8  384.26  5207.3  385.02  5252.5  387.91  5328.2  392.03
  5343.0  393.63  5372.6  394.89  5382.7  394.70  5417.0  396.58  5445.0  397.20
#Mann=5,-1,0
  4837.6    0.05       0  4871.3    0.16       0  5002.2    0.07       0
  5008.2    0.16       0  5095.7    0.05       0
Bank Sta=5002.2,5008.2
Exp/Cntr=0.3,0.1

Type RM Length L Ch R = 1,1610,389,389,389
BEGIN DESCRIPTION:
Mapping XS 0a74b241
END DESCRIPTION:
XS GIS Cut Line= 3
      3617139.76     10597633.10      3616931.38     10597643.52
      3616676.18     10598002.88
#Sta/Elev= 30
  4869.2  384.03  4871.8  384.03  4879.4  382.67  4889.4  381.98  4907.7  379.26
  4912.7  379.72  4929.4  377.62  4979.5  376.14  4989.5  372.93  4996.5  372.47
  4999.3  371.97  5002.5  372.47  5009.5  373.85  5019.5  374.85  5059.6  375.10
  5176.9  379.64  5191.7  380.74  5197.8  381.63  5256.9  383.97  5270.0  385.31
  5292.6  386.24  5313.5  388.13  5328.3  388.56  5334.4  389.28  5370.1  391.32
  5378.7  391.41  5384.8  392.63  5429.1  394.60  5435.3  395.40  5518.6  397.77
#Mann=3,-1,0
  4869.2    0.05       0  4996.5    0.03       0  5002.5    0.05       0
Bank Sta=4996.5,5002.5
Exp/Cntr=0.3,0.1

Type RM Length L Ch R = 1,1221,325,325,325
BEGIN DESCRIPTION:
UNT 070 IN UKCR 1.2
END DESCRIPTION:
XS GIS Cut Line= 3
      3616988.24     10597122.53      3616663.36     10597510.28
      3616569.62     10597822.76
#Sta/Elev= 30
  4641.2  370.17  4644.0  369.67  4647.2  370.17  4698.8  371.28  4752.4  371.64
  4773.3  372.87  4781.1  372.41  4837.0  373.92  4863.1  373.31  4922.9  373.12
  4929.4  372.20  4937.2  373.09  4951.2  372.90  4986.6  371.24  5000.9  371.30
  5015.3  372.35  5039.3  372.28  5199.2  381.32  5230.5  384.89  5240.9  385.41
  5246.6  386.49  5284.9  387.26  5351.0  390.05  5356.3  389.42  5408.0  391.69
  5417.2  391.86  5422.4  391.12  5455.4  392.58  5460.7  391.87  5473.3  392.37
#Mann=5,-1,0
  4641.2    0.07       0  4647.2    0.12       0  4698.8    0.05       0
  4863.1    0.16       0  5039.3    0.05       0
Bank Sta=4641.2,4647.2
Exp/Cntr=0.3,0.1

Type RM Length L Ch R = 1,896,532,532,532
BEGIN DESCRIPTION:
Mapping XS b1aa6618
END DESCRIPTION:
XS GIS Cut Line= 3
      3616843.91     10597020.71      3616566.14     10597253.34
      3616291.83     10597690.84
#Sta/Elev= 30
  4757.6  369.21  4845.2  371.69  4853.0  371.22  4888.2  371.99  4916.8  369.03
  4931.1  371.39  4951.9  371.18  4958.9  370.28  4980.5  369.87  4998.4  365.61
  5001.1  365.11  5004.4  365.61  5015.7  369.05  5030.0  369.52  5037.1  371.08
  5050.8  370.48  5058.6  371.51  5079.4  371.37  5087.2  372.39  5107.6  372.54
  5368.7  378.21  5447.7  381.98  5470.3  383.95  5478.3  385.53  5493.6  386.08
  5557.3  386.99  5587.9  388.28  5593.8  387.73  5630.4  388.52  5636.3  387.71
#Mann=4,-1,0
  4757.6    0.16       0  4998.4    0.07       0  5004.4    0.16       0
  5107.6    0.05       0
Bank Sta=4998.4,5004.4
Exp/Cntr=0.3,0.1

Type RM Length L Ch R = 1,364,0,0,0
BEGIN DESCRIPTION:
UNT 070 IN UKCR 1.0
END DESCRIPTION:
XS GIS Cut Line= 3
      3616819.65     10596892.23      3616586.97     10596888.76
      3616055.73     10597308.89
#Sta/Elev= 30
  4912.9  369.52  4952.9  369.82  4982.9  367.72  4989.9  359.51  4992.7  359.01
  4995.9  359.51  5002.9  360.87  5013.0  368.20  5043.0  367.64  5083.0  369.52
  5101.5  369.54  5158.7  369.00  5216.4  370.54  5237.2  372.22  5251.7  371.88
  5372.7  376.07  5408.8  376.54  5415.1  373.47  5435.9  371.66  5444.0  372.24
  5450.4  377.58  5458.4  377.56  5479.2  379.65  5543.4  382.26  5636.3  388.46
  5767.2  394.64  5779.0  395.16  5799.8  393.41  5806.2  395.51  5822.9  395.48
#Mann=6,-1,0
  4912.9    0.12       0  4989.9    0.07       0  4995.9    0.12       0
  5101.5    0.16       0  5372.7    0.05       0  5767.2     0.1       0
Bank Sta=4989.9,4995.9
Exp/Cntr=0.3,0.1

Chan Stop Cuts=-1