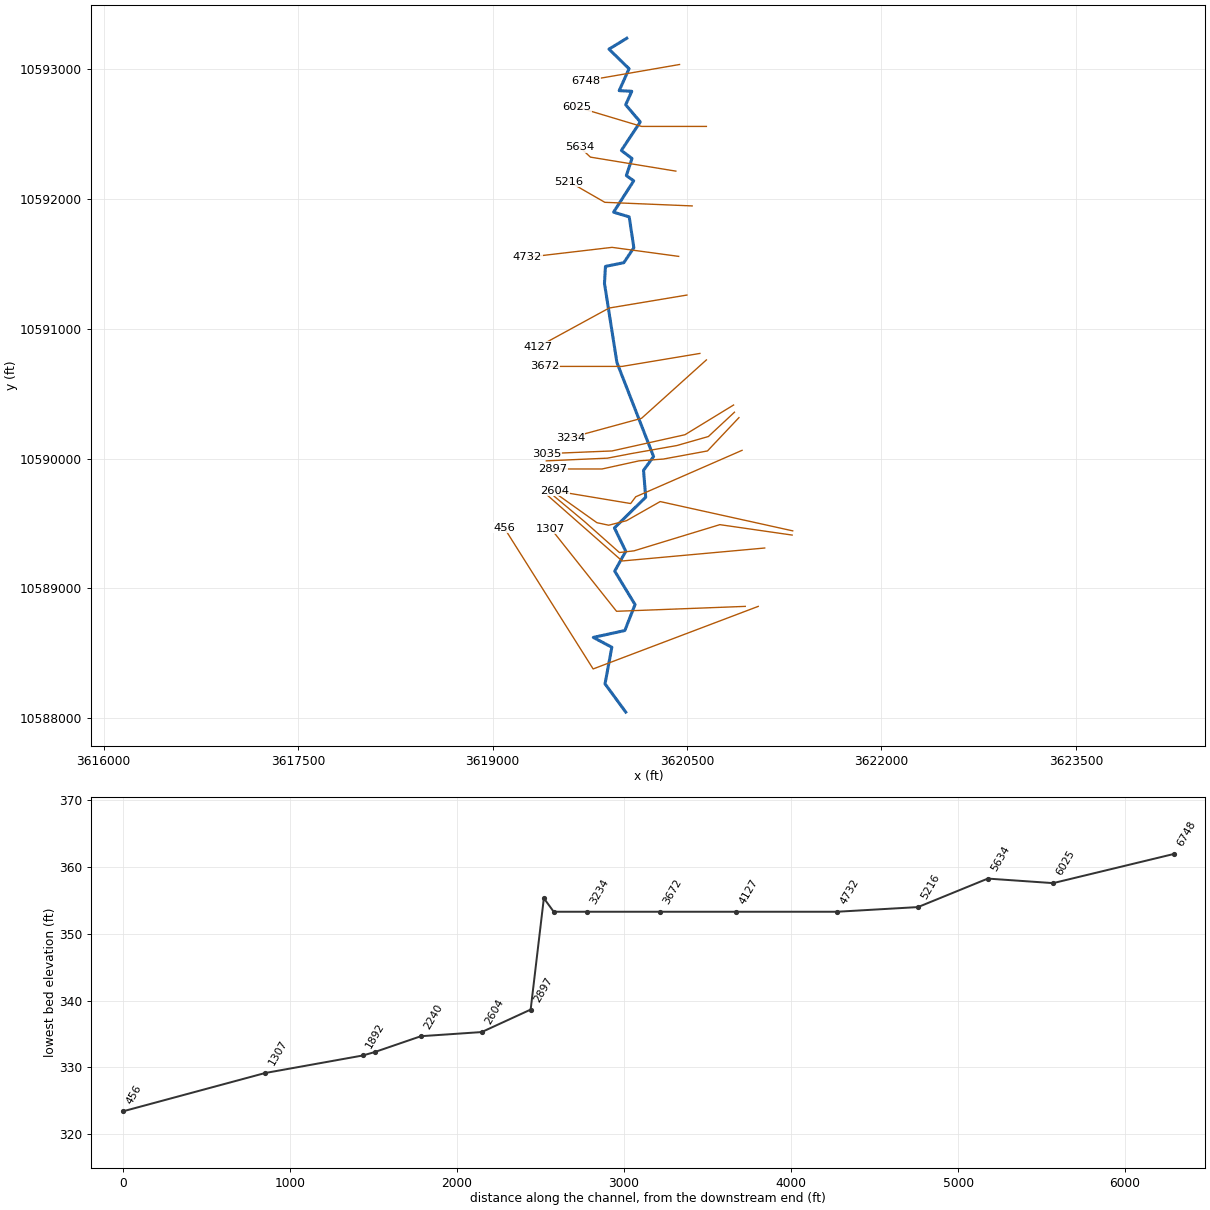
--- UNT 072 IN UKCR.prj (project) ---

Proj Title=UNT 072 IN UKCR Base Level Engineering
Current Plan=p01
Default Exp/Contr=0.3,0.1
English Units
Geom File=g01
Flow File=f01
Plan File=p01
Y Axis Title=Elevation
X Axis Title(PF)=Main Channel Distance
X Axis Title(XS)=Station
BEGIN DESCRIPTION:
UNT 072 IN UKCR
END DESCRIPTION:
DSS Export Rating Curves= 0
DSS Export Rating Curve Sorted= 0
DSS Export Volume Flow Curves= 0
DXF OffsetX= 0
DXF OffsetY= 0
DXF ScaleX= 1
DXF ScaleY= 10

--- UNT 072 IN UKCR.p01 (plan) ---

Plan Title=Multiple Run
Program Version=4.10
Short Identifier=Multiple
Geom File=g01
Flow File=f01
Subcritical Flow
K Sum by GR= 0
Std Step Tol= 0.01
Critical Tol= 0.01
Num of Std Step Trials= 20
Max Error Tol= 0.3
Flow Tol Ratio= 0.001
Split Flow NTrial= 30
Split Flow Tol= 0.02
Split Flow Ratio= 0.02
Log Output Level= 0
Friction Slope Method= 1
Unsteady Friction Slope Method= 2
Unsteady Bridges Friction Slope Method= 1
Parabolic Critical Depth
Global Vel Dist= 1 , 1 , 1
Global Log Level= 0
CheckData=True
Encroach Param=-1 ,0,0, 0
BEGIN DESCRIPTION:
Multiple Run
END DESCRIPTION:
Computation Interval=1HOUR
Output Interval=1HOUR
Run HTab= 0
Run UNet= 0
Run PostProcess= 0
Run WQNet= 0
UNET Theta= 1
UNET Theta Warmup= 1
UNET ZTol= 0.02
UNET ZSATol= 0.05
UNET MxIter= 20
UNET MaxInSteps= 0
UNET DtIC= 0
UNET DtMin= 0
UNET MaxCRTS= 20
UNET WFStab= 2
UNET SFStab= 1
UNET WFX= 1
UNET SFX= 1
UNET DSS MLevel= 4
UNET DZMax Abort= 100
UNET Convert EG Bridges= 0
UNET Use Existing IB Tables=-1
UNET Froude Reduction=False
UNET Froude Limit= 1
UNET Froude Power= 10
UNET Time Slicing=0,0, 5
UNET Junction Losses=0
Instantaneous Interval=1HOUR
Write IC File= 0
Write IC File at Sim End=0
Echo Input=False
Echo Parameters=False
Echo Output=False
Write Detailed= 0
WQ AD Non Conservative
WQ ULTIMATE=-1
WQ Max Comp Step=1HOUR
WQ Output Interval=15MIN
WQ Output Selected Increments= 0
WQ Output face flow=0
WQ Output face velocity=0
WQ Output face area=0
WQ Output face dispersion=0
WQ Output cell volume=0
WQ Output cell surface area=0
WQ Output cell continuity=0
WQ Output cumulative cell continuity=0
WQ Output face conc=0
WQ Output face dconc_dx=0
WQ Output face courant=0
WQ Output face peclet=0
WQ Output face adv mass=0
WQ Output face disp mass=0
WQ Output cell mass=0
WQ Output cell source sink temp=0
WQ Output cell source sink nsm=0
WQ Output MaxMinRange=-1
WQ Daily Max Min Mean=-1
WQ Daily Range=0
WQ Daily Time=0
WQ Create Restart=0
WQ Fixed Restart=0
WQ System Summary=0
WQ Use Fixed Temperature=0
Sorting and Armoring Iterations= 10
XS Update Threshold= 0.02
Hydraulics Update Threshold= 0.02
Energy Slope Method= 1
Volume Change Method= 0
XS Weighting Method= 0
Number of US Weighted Cross Sections= 1
Number of DS Weighted Cross Sections= 1
Upstream XS Weight=0.25
Main XS Weight=0.5
Downstream XS Weight=0.25
Number of DS XS's Weighted with US Boundary= 1
Upstream Boundary Weight= 1
Weight of XSs Associated with US Boundary= 0
Number of US XS's Weighted with DS Boundary= 1
Downstream Boundary Weight= 0.5
Weight of XSs Associated with DS Boundary= 0.5
Sediment Output Level= 4
Mass or Volume Output= 0
Output Increment Type= 1
Profile and TS Output Increment= 10
XS Output Flag= 0
XS Output Increment= 10
Disregard all LS=0
Disregard all Conn=0
Disregard all Breaches=0
Disregard all Pumps=0

--- UNT 072 IN UKCR.f01 (steady flow) ---

Flow Title=Multiple
Number of Profiles=7
Profile Names=10-year,25-year,50-year,1pct_min,100-year,1pct_plu,500-year
River Rch & RM= UNT 072 IN UKCR,Reach-1,6748
     922    1259    1536    1369    1852    2504    2680
Boundary for River Rch & Prof#=UNT 072 IN UKCR,Reach-1,1
Up Type=0
Dn Type=3
Dn Slope=0.005
Boundary for River Rch & Prof#=UNT 072 IN UKCR,Reach-1,2
Up Type=0
Dn Type=3
Dn Slope=0.005
Boundary for River Rch & Prof#=UNT 072 IN UKCR,Reach-1,3
Up Type=0
Dn Type=3
Dn Slope=0.005
Boundary for River Rch & Prof#=UNT 072 IN UKCR,Reach-1,4
Up Type=0
Dn Type=3
Dn Slope=0.005
Boundary for River Rch & Prof#=UNT 072 IN UKCR,Reach-1,5
Up Type=0
Dn Type=3
Dn Slope=0.005
Boundary for River Rch & Prof#=UNT 072 IN UKCR,Reach-1,6
Up Type=0
Dn Type=3
Dn Slope=0.005
Boundary for River Rch & Prof#=UNT 072 IN UKCR,Reach-1,7
Up Type=0
Dn Type=3
Dn Slope=0.005

--- UNT 072 IN UKCR.g01 (geometry) ---

Geom Title=Existing Conditions
Program Version=4.10

River Reach=UNT 072 IN UKCR ,Reach-1
Reach XY= 30
      3620035.39     10593239.73      3619898.25       10593156.
      3620053.25       10593005.        3619977.       10592836.
        3620074.       10592831.        3620027.       10592727.
       3620139.5       10592595.      3619993.75       10592375.
      3620075.75       10592313.      3620032.25       10592181.
        3620089.       10592141.      3619933.75       10591899.
      3620054.25       10591863.        3620090.       10591625.
        3620013.       10591510.        3619871.       10591481.
       3619863.5       10591350.       3619959.5       10590740.
      3620242.25       10590015.      3620164.75       10589909.
       3620181.5       10589702.      3619940.25       10589465.
      3620027.75       10589285.       3619942.5       10589132.
      3620099.25       10588874.       3620020.5       10588674.
       3619777.5       10588621.      3619920.25       10588545.
      3619867.75       10588263.      3620027.75       10588045.

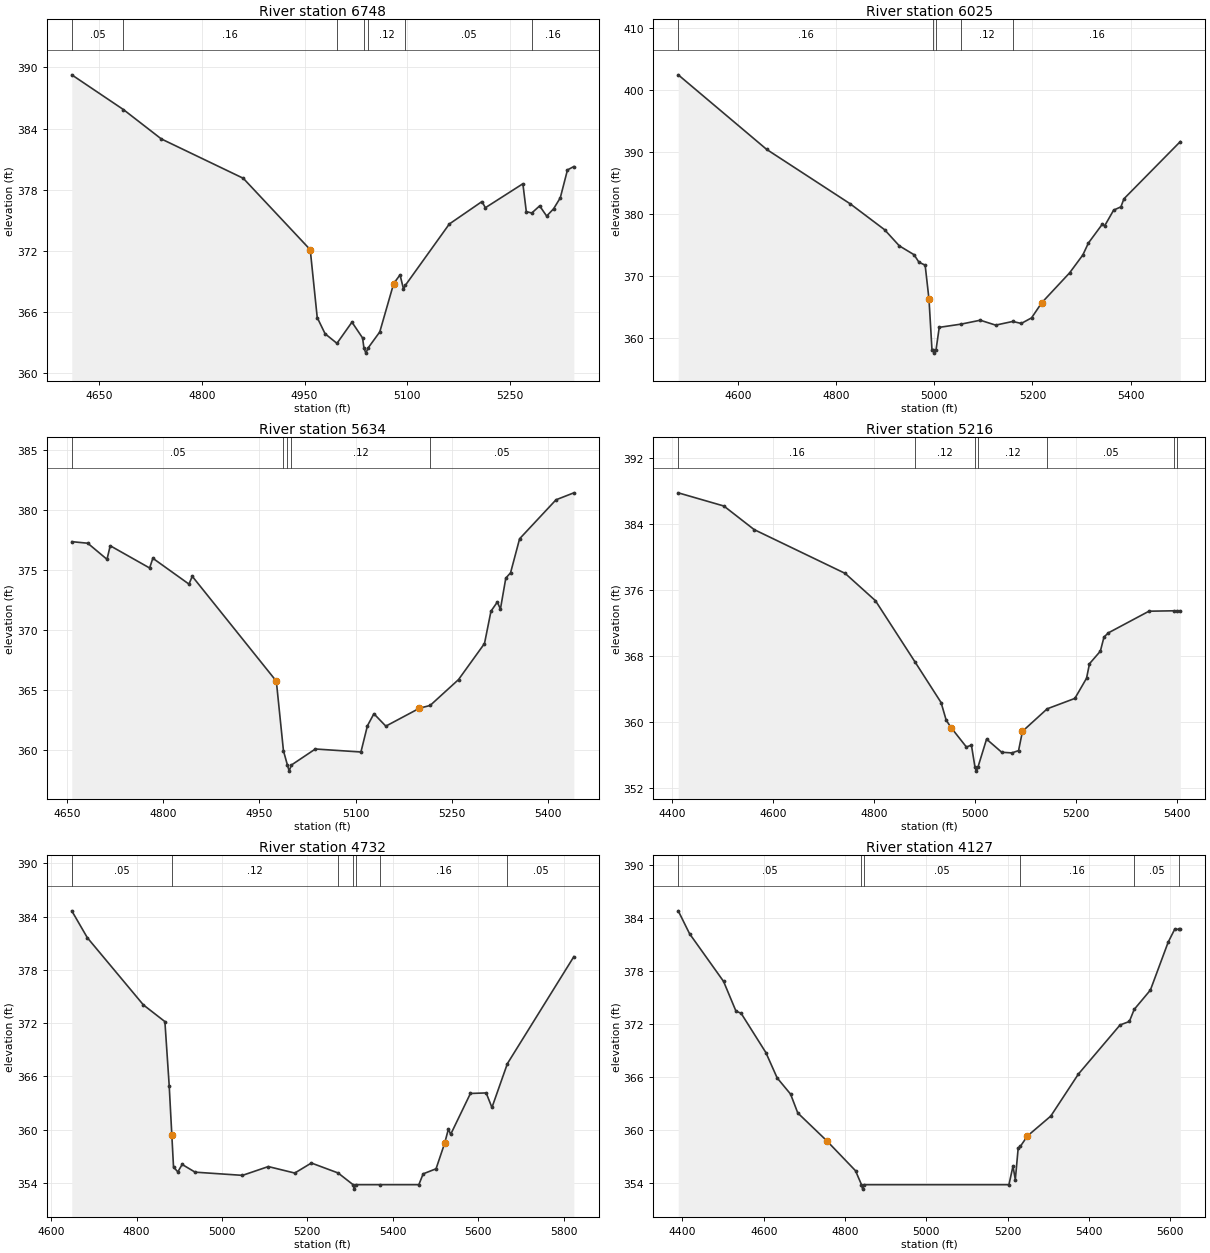
Type RM Length L Ch R = 1 ,6748    ,723,723,723
BEGIN DESCRIPTION:
UNT 072 IN UKCR 13.0
END DESCRIPTION:
XS GIS Cut Line= 2
      3620442.65     10593037.62      3619720.48     10592912.63
#Sta/Elev= 30
  4610.1  389.28  4685.5  385.87  4740.8  382.99  4860.4  379.13  4958.2  372.12
  4968.4  365.46  4979.9  363.87  4997.2  362.93  5019.1  365.01  5034.6  363.46
  5036.6  362.47  5039.4  361.97  5042.6  362.47  5059.7  364.05    5080   368.8
  5089.3  369.65  5094.3  368.27  5096.9  368.61  5161.2  374.64  5208.8  376.84
  5213.9  376.24  5268.6  378.59  5273.6  375.86  5281.6  375.72  5293.1  376.42
  5303.3  375.42  5313.4  376.13  5323.2  377.21  5333.7  379.95    5343  380.28
#Mann= 7 ,-1 , 0
  4610.1     .05       0  4685.5     .16       0  4997.2     .12       0
  5036.6     .07       0  5042.6     .12       0  5096.9     .05       0
  5281.6     .16       0
Bank Sta=4958.2,5080
XS Rating Curve= 0 ,0
Exp/Cntr=0.3,0.1

Type RM Length L Ch R = 1 ,6025    ,391,391,391
BEGIN DESCRIPTION:
UNT 072 IN UKCR 12.0
END DESCRIPTION:
XS GIS Cut Line= 3
      3620649.59     10592560.19      3620149.61     10592560.19
       3619649.6     10592710.19
#Sta/Elev= 30
  4478.9  402.42  4658.9  390.41  4828.9  381.65  4898.9  377.48  4928.9  374.88
  4958.9  373.45  4968.9  372.24  4981.5  371.77  4989.3   366.3  4995.4  358.16
  4997.6   358.1  5000.4   357.6  5003.6   358.1  5010.2  361.75  5055.3  362.28
  5093.7   362.9    5125  362.11  5159.8   362.7  5177.2  362.38  5198.1  363.28
    5219  365.73  5275.6  370.53  5302.5  373.41  5313.8  375.33  5341.7  378.32
  5346.9   378.1  5365.2  380.63    5380  381.16  5386.1  382.45  5500.9  391.67
#Mann= 5 ,-1 , 0
  4478.9     .16       0  4997.6     .07       0  5003.6     .16       0
  5055.3     .12       0  5159.8     .16       0
Bank Sta=4989.3,5219
XS Rating Curve= 0 ,0
Exp/Cntr=0.3,0.1

Type RM Length L Ch R = 1 ,5634    ,418,418,418
BEGIN DESCRIPTION:
UNT 072 IN UKCR 11.0
END DESCRIPTION:
XS GIS Cut Line= 3
      3620414.15     10592215.57      3619755.13     10592323.49
      3619671.57     10592401.62
#Sta/Elev= 30
  4657.8  377.36  4682.7  377.23  4712.7  375.89  4717.7  377.02  4779.1  375.17
  4784.1  375.98  4840.4  373.83  4845.5  374.48  4976.5  365.76  4987.6  359.97
  4993.8  358.78  4996.5  358.28  4999.8  358.78  5037.3  360.12  5108.3  359.87
  5118.4  362.05  5128.5  363.05  5147.1  362.02  5199.5  363.51  5216.1  363.74
  5260.3  365.89  5300.8  368.89  5310.9  371.58  5320.8  372.34  5325.6  371.75
    5334  374.33  5341.4  374.77  5355.5   377.6  5412.2  380.84    5440  381.42
#Mann= 5 ,-1 , 0
  4657.8     .05       0  4987.6     .12       0  4993.8     .07       0
  4999.8     .12       0  5216.1     .05       0
Bank Sta=4976.5,5199.5
XS Rating Curve= 0 ,0
Exp/Cntr=0.3,0.1

Type RM Length L Ch R = 1 ,5216    ,484,484,484
BEGIN DESCRIPTION:
UNT 072 IN UKCR 10.0
END DESCRIPTION:
XS GIS Cut Line= 3
      3620539.91     10591947.34      3619866.27     10591975.12
      3619588.53     10592134.82
#Sta/Elev= 30
  4411.7  387.77  4502.1  386.17  4562.1  383.31  4742.3     378  4802.3  374.69
  4880.3   367.3  4932.4  362.33  4942.5  360.19  4952.5  359.27  4982.5  356.94
  4992.5  357.16  4999.5  354.51  5002.3  354.01  5005.5  354.51  5022.5  357.89
  5052.5   356.3  5072.6  356.22  5085.9   356.5  5093.6  358.84  5142.6  361.57
  5197.4  362.83  5220.5  365.27  5226.4  367.04  5247.9  368.56  5255.1  370.27
  5263.7  370.78  5344.2  373.41  5393.5  373.46    5399  373.46  5406.3  373.46
#Mann= 7 ,-1 , 0
  4411.7     .16       0  4880.3     .12       0  4999.5     .07       0
  5005.5     .12       0  5142.6     .05       0  5393.5      .1       0
    5399     .15       0
Bank Sta=4952.5,5093.6
XS Rating Curve= 0 ,0
Exp/Cntr=0.3,0.1

Type RM Length L Ch R = 1 ,4732    ,605,605,605
BEGIN DESCRIPTION:
UNT 072 IN UKCR 9.0
END DESCRIPTION:
XS GIS Cut Line= 3
      3620435.76     10591558.44      3619921.83      10591627.9
      3619269.09     10591551.51
#Sta/Elev= 30
  4648.3  384.64  4684.8  381.61    4816  374.05  4866.4  372.17  4876.5  364.94
  4882.6  359.41  4886.6  355.79  4896.7  355.25  4906.8  356.09  4937.1  355.22
  5048.1  354.86  5108.6  355.85  5170.5  355.12  5209.4  356.25    5272  355.13
  5307.1  353.81  5309.8  353.31  5313.1  353.81  5371.1  353.81  5461.1  353.81
  5471.2  355.03  5501.4   355.6  5521.5  358.47  5530.5   360.1  5535.5  359.46
  5581.9  364.08  5618.8  364.14  5632.3   362.5  5668.5  367.44  5824.1  379.48
#Mann= 7 ,-1 , 0
  4648.3     .05       0  4882.6     .12       0    5272     .05       0
  5307.1     .07       0  5313.1     .05       0  5371.1     .16       0
  5668.5     .05       0
Bank Sta=4882.6,5521.5
XS Rating Curve= 0 ,0
Exp/Cntr=0.3,0.1

Type RM Length L Ch R = 1 ,4127    ,455,455,455
BEGIN DESCRIPTION:
UNT 072 IN UKCR 8.0
END DESCRIPTION:
XS GIS Cut Line= 3
      3620499.64     10591260.19      3619899.61     10591160.19
      3619349.61     10590860.19
#Sta/Elev= 30
  4389.6  384.77  4417.5  382.18  4501.1  376.79  4531.6  373.43  4544.2  373.19
  4605.1  368.75  4632.9  365.88  4665.9  364.05  4683.6  361.92  4754.6  358.79
  4825.6  355.39  4840.3  353.81  4843.1  353.31  4846.3  353.81  5202.9  353.81
  5212.9  355.91  5218.6  354.38  5225.7  357.96  5231.1  358.15  5248.5  359.32
  5305.9  361.57  5373.8  366.32  5476.3  371.87  5499.1  372.26  5510.9  373.62
  5550.8  375.81  5594.5  381.22  5610.6  382.69  5621.2  382.68  5624.4  382.68
#Mann= 6 ,-1 , 0
  4389.6     .05       0  4840.3    .033       0  4846.3     .05       0
  5231.1     .16       0  5510.9     .05       0  5621.2      .1       0
Bank Sta=4754.6,5248.5
XS Rating Curve= 0 ,0
Exp/Cntr=0.3,0.1

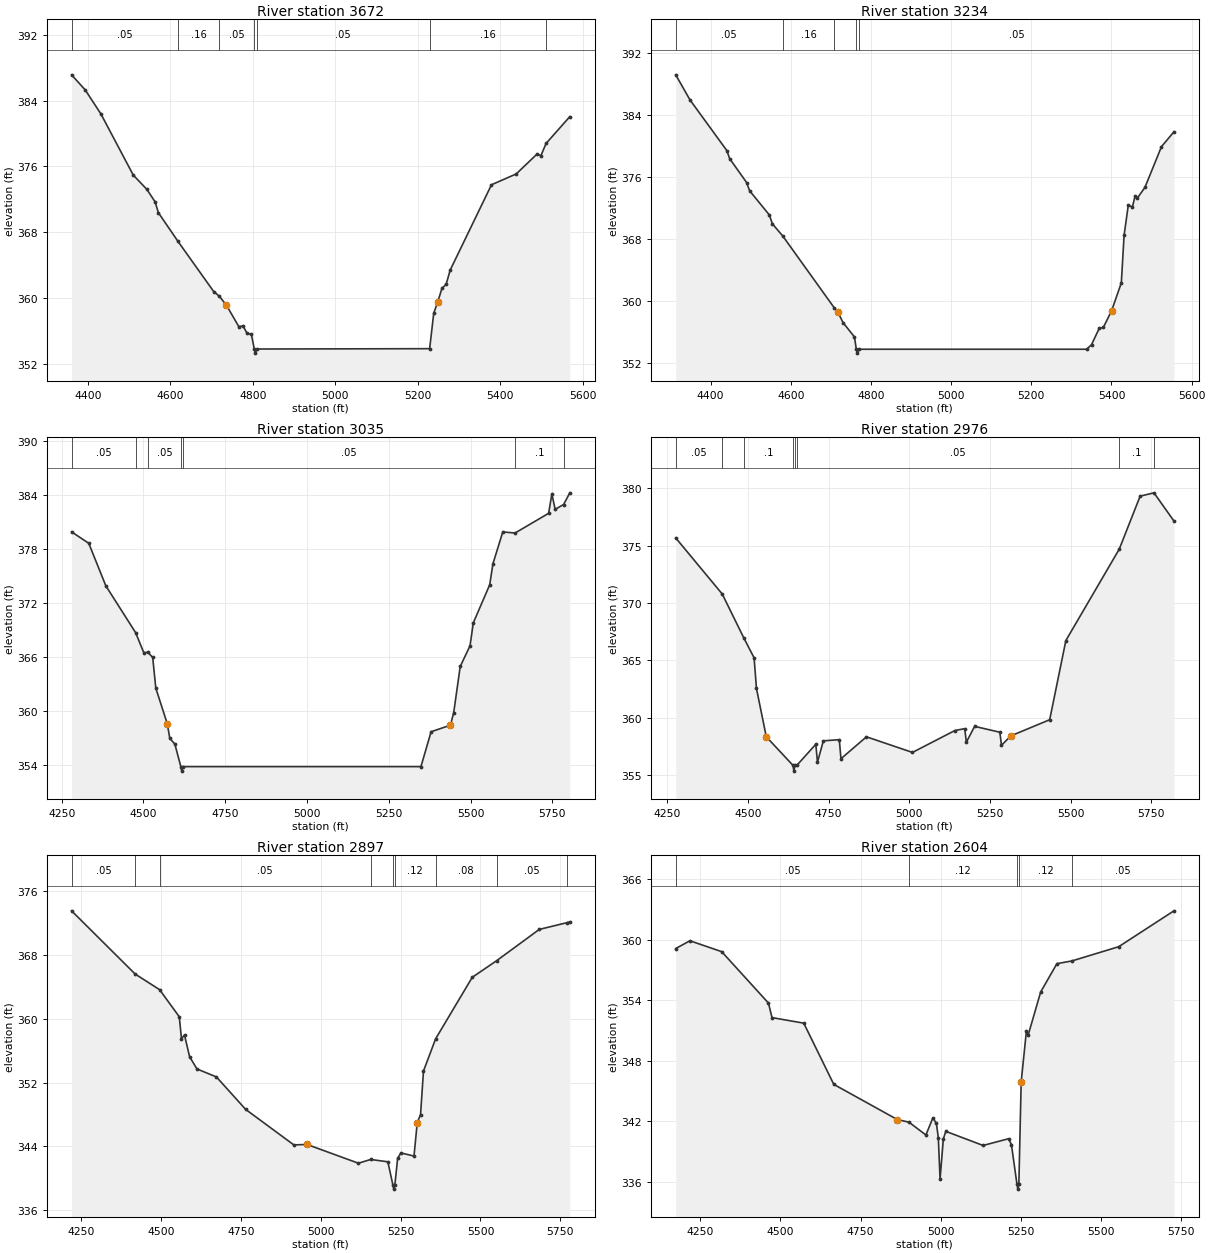
Type RM Length L Ch R = 1 ,3672    ,438,438,438
BEGIN DESCRIPTION:
UNT 072 IN UKCR 7.0
END DESCRIPTION:
XS GIS Cut Line= 3
      3620599.66      10590810.2      3619999.61     10590710.19
      3619399.63     10590710.19
#Sta/Elev= 30
  4360.1  387.12  4393.1  385.29  4431.1  382.38  4509.7  374.94  4542.6  373.21
  4562.9  371.67  4570.5  370.38  4618.1  366.89  4704.8  360.79  4717.7  360.26
  4735.3  359.16  4765.7  356.53  4775.8  356.62  4785.9   355.7  4796.1   355.6
  4803.2  353.81    4806  353.31  4809.2  353.81  5228.5  353.85  5238.4  358.15
  5248.4  359.58  5258.4  361.19  5268.4  361.66  5278.4  363.41  5378.4  373.76
  5438.4  375.08  5488.4  377.47  5498.4  377.31  5510.8  378.78  5568.4  382.04
#Mann= 7 ,-1 , 0
  4360.1     .05       0  4618.1     .16       0  4717.7     .05       0
  4803.2    .033       0  4809.2     .05       0  5228.5     .16       0
  5510.8     .05       0
Bank Sta=4735.3,5248.4
XS Rating Curve= 0 ,0
Exp/Cntr=0.3,0.1

Type RM Length L Ch R = 1 ,3234    ,199,199,199
BEGIN DESCRIPTION:
UNT 072 IN UKCR 6.0
END DESCRIPTION:
XS GIS Cut Line= 3
      3620649.64     10590760.22      3620149.61     10590310.19
      3619599.62     10590160.19
#Sta/Elev= 30
  4313.1  389.13  4348.7   385.9  4440.6  379.38  4447.7  378.34  4489.9  375.27
  4497.4  374.21  4546.7  371.09  4554.2  369.95  4579.9   368.4  4708.4  359.15
  4716.8  358.66  4730.6  357.23    4759  355.39  4763.5  353.81  4766.2  353.31
  4769.5  353.81  5338.2  353.81  5350.3   354.4  5369.3  356.48  5379.7  356.61
  5400.4  358.77  5424.6  362.35  5431.5  368.47  5441.9  372.32  5452.3  372.14
  5459.2  373.57  5464.4  373.25  5483.4  374.63  5524.8  379.89  5555.9   381.8
#Mann= 5 ,-1 , 0
  4313.1     .05       0  4579.9     .16       0  4708.4     .05       0
  4763.5    .033       0  4769.5     .05       0
Bank Sta=4716.8,5400.4
XS Rating Curve= 0 ,0
Exp/Cntr=0.3,0.1

Type RM Length L Ch R = 1 ,3035    ,59,59,59
BEGIN DESCRIPTION:
UNT 072 IN UKCR 5.0
END DESCRIPTION:
XS GIS Cut Line= 4
      3620859.35     10590412.63      3620484.33     10590183.45
      3619921.83     10590058.45      3619414.88     10590037.62
#Sta/Elev= 30
  4280.4  379.92  4332.9  378.65  4385.1  373.92  4476.2  368.71  4501.3  366.47
  4513.4  366.54  4528.4  365.95  4537.9  362.54  4573.1  358.56  4580.6  356.96
  4596.1  356.32  4614.4  353.81  4617.1  353.31  4620.4  353.81  5348.4  353.81
  5379.5  357.69  5438.5  358.42  5448.5   359.8  5468.5  364.95  5498.5  367.25
  5508.5   369.8  5558.6  374.03  5568.6  376.38  5598.6  379.91  5636.1  379.79
  5738.7  381.98  5748.7  384.13  5758.7  382.42  5784.5  382.96  5803.5  384.26
#Mann= 7 ,-1 , 0
  4280.4     .05       0  4476.2     .08       0  4513.4     .05       0
  4614.4    .033       0  4620.4     .05       0  5636.1      .1       0
  5784.5     .05       0
Bank Sta=4573.1,5438.5
XS Rating Curve= 0 ,0
Exp/Cntr=0.3,0.1

Type RM Length L Ch R = 1 ,2976    ,79,79,79
BEGIN DESCRIPTION:
Mapping XS 2f329df0
END DESCRIPTION:
XS GIS Cut Line= 6
      3620866.28     10590357.07      3620664.88     10590169.56
      3620421.83     10590100.12      3620067.66     10590037.62
      3619887.11      10590002.9      3619414.93     10589982.06
#Sta/Elev= 30
  4276.4  375.66  4420.6  370.77  4487.5  366.94  4519.3  365.21  4526.6  362.54
  4557.1  358.33  4639.9  355.84  4642.6  355.34  4645.9  355.84  4652.9  355.88
  4710.5  357.68  4715.7  356.12  4733.9  357.98  4783.3  358.08  4788.5  356.42
  4867.5  358.33  5010.1  356.97  5141.7  358.88    5172  359.04  5177.1  357.86
  5202.7  359.24  5280.9  358.73    5286  357.59  5314.8  358.41  5435.4  359.82
  5485.5  366.72  5650.9  374.68  5715.7   379.3  5758.6  379.59  5820.5  377.13
#Mann= 8 ,-1 , 0
  4276.4     .05       0  4420.6     .08       0  4487.5      .1       0
  4639.9     .03       0  4645.9      .1       0  4652.9     .05       0
  5650.9      .1       0  5758.6     .05       0
Bank Sta=4557.1,5314.8
XS Rating Curve= 0 ,0
Exp/Cntr=0.3,0.1

Type RM Length L Ch R = 1 ,2897    ,293,293,293
BEGIN DESCRIPTION:
Mapping XS af9a8599
END DESCRIPTION:
XS GIS Cut Line= 6
      3620900.97     10590315.37      3620657.94     10590058.45
      3620317.66     10589995.95      3620130.16     10589982.06
      3619845.44     10589919.56      3619464.08     10589919.56
#Sta/Elev= 30
  4219.4  373.57  4418.5  365.64    4495  363.68  4556.7  360.28  4563.6  357.52
  4573.1  357.99  4588.9  355.28    4612  353.73    4673  352.73  4764.5  348.66
  4915.5   344.2  4957.2  344.25  5117.8   341.9  5156.2  342.37    5210  342.08
  5225.9  339.15  5228.6  338.65  5231.9  339.15  5240.7  342.53  5250.9  343.19
  5291.9   342.8  5302.1     347  5312.4  348.01  5321.6  353.47  5359.6  357.51
  5474.4  365.23  5550.3   367.3  5684.4  371.24  5769.7  372.07  5779.9  372.19
#Mann= 9 ,-1 , 0
  4219.4     .05       0  4418.5      .1       0    4495     .05       0
  5156.2     .12       0  5225.9     .03       0  5231.9     .12       0
  5359.6     .08       0  5550.3     .05       0  5769.7     .08       0
Bank Sta=4957.2,5302.1
XS Rating Curve= 0 ,0
Exp/Cntr=0.3,0.1

Type RM Length L Ch R = 1 ,2604    ,364,364,364
BEGIN DESCRIPTION:
UNT 072 IN UKCR 4.0
END DESCRIPTION:
XS GIS Cut Line= 4
      3620924.79     10590063.13      3620104.49     10589705.06
      3620065.43     10589652.98      3619479.46     10589750.64
#Sta/Elev= 30
  4173.3  359.14  4217.6  359.91  4316.7  358.83  4462.6  353.73  4473.6  352.29
  4572.7  351.74  4666.3  345.67  4864.5  342.18  4900.8  341.92  4953.7  340.65
  4975.5  342.35  4986.4  341.79  4992.4   340.4  4997.9  336.28  5008.2  340.28
  5015.8  341.01  5132.1  339.61  5211.6  340.28  5220.5   339.7  5237.7  335.78
  5240.5  335.28  5243.7  335.78  5250.9  345.91  5267.3  350.98  5272.4  350.52
  5311.7  354.83  5362.4  357.64  5409.1  357.91    5555  359.32  5727.5  362.88
#Mann= 5 ,-1 , 0
  4173.3     .05       0  4900.8     .12       0  5237.7     .07       0
  5243.7     .12       0  5409.1     .05       0
Bank Sta=4864.5,5250.9
XS Rating Curve= 0 ,0
Exp/Cntr=0.3,0.1

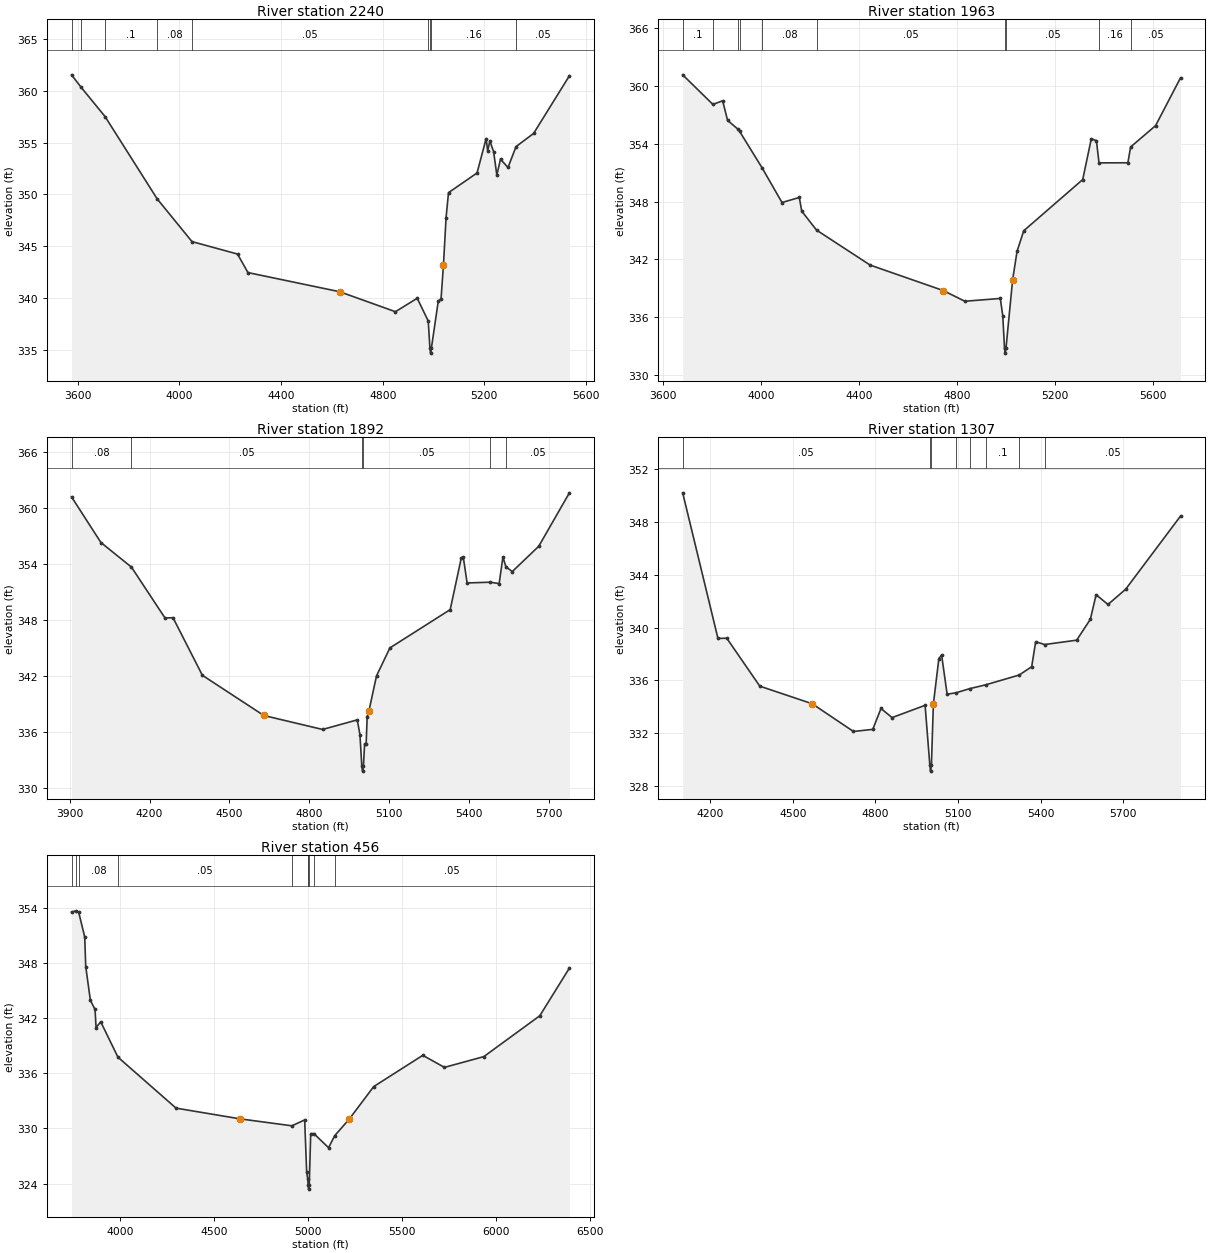
Type RM Length L Ch R = 1 ,2240    ,277,277,277
BEGIN DESCRIPTION:
Mapping XS 450bde68
END DESCRIPTION:
XS GIS Cut Line= 6
      3621315.44     10589442.47      3620293.29     10589668.17
      3620032.88      10589520.6      3619896.16     10589485.88
      3619805.01     10589505.41      3619496.84      10589724.6
#Sta/Elev= 30
  3575.7  361.54  3612.2  360.37  3707.5  357.51  3912.5  349.56  4049.6  345.43
  4228.7  344.23  4269.7  342.44  4630.7  340.59  4850.1  338.66  4935.8  339.96
  4979.2  337.76  4985.7  335.16  4988.4  334.66  4991.7  335.16  5018.4  339.65
  5029.6  339.92    5039  343.15  5049.3  347.74  5058.9  350.16  5171.2  352.06
  5206.9  355.38    5213   354.2  5221.7  355.15  5236.4  354.12    5249  351.86
  5263.5  353.39    5293  352.59  5324.7  354.61  5393.8  355.88  5534.6  361.45
#Mann= 9 ,-1 , 0
  3575.7      .1       0  3612.2     .05       0  3707.5      .1       0
  3912.5     .08       0  4049.6     .05       0  4979.2     .16       0
  4985.7     .07       0  4991.7     .16       0  5324.7     .05       0
Bank Sta=4630.7,5039
XS Rating Curve= 0 ,0
Exp/Cntr=0.3,0.1

Type RM Length L Ch R = 1 ,1963    ,71,71,71
BEGIN DESCRIPTION:
Mapping XS 2e0e4421
END DESCRIPTION:
XS GIS Cut Line= 6
      3621311.14     10589409.92      3620753.36     10589490.22
      3620091.47      10589288.4      3619978.62     10589275.37
      3619709.53     10589514.09      3619475.16     10589709.39
#Sta/Elev= 30
  3679.4  361.14  3802.9  358.07  3842.6  358.45  3862.8  356.42    3904  355.53
  3911.6  355.29  4003.9  351.49  4085.1   347.9  4155.8  348.42  4165.9     347
  4226.2  345.04  4445.3  341.41  4743.8  338.77  4832.1  337.66    4977  337.95
  4987.1  336.17  4994.2  332.78  4996.9  332.28  5000.2  332.78  5027.4  339.89
  5045.5  342.84  5072.8  344.97  5313.7  350.28  5348.8  354.51  5369.7  354.31
  5380.4  352.01  5498.2  352.02  5509.5  353.66  5611.4  355.87  5713.3  360.83
#Mann= 10 ,-1 , 0
  3679.4      .1       0  3802.9     .08       0    3904     .05       0
  3911.6      .1       0  4003.9     .08       0  4226.2     .05       0
  4994.2     .03       0  5000.2     .05       0  5380.4     .16       0
  5509.5     .05       0
Bank Sta=4743.8,5027.4
XS Rating Curve= 0 ,0
Exp/Cntr=0.3,0.1

Type RM Length L Ch R = 1 ,1892    ,585,585,585
BEGIN DESCRIPTION:
UNT 072 IN UKCR 3.0
END DESCRIPTION:
XS GIS Cut Line= 3
      3621099.58     10589310.19      3619999.61     10589210.19
      3619423.21     10589716.95
#Sta/Elev= 30
  3906.6  361.19    4017   356.3  4131.8  353.66    4258   348.2  4288.1  348.23
  4398.6  342.05  4629.5  337.74  4850.5  336.24    4981  337.27    4991  335.68
  4998.1  332.27  5000.8  331.77  5004.1  332.27  5008.6  334.72  5014.4  334.72
  5018.2  337.63  5024.9  338.24  5053.3  341.99  5103.6  344.99  5330.4   349.1
  5372.1  354.64  5379.7  354.71    5394  351.96  5480.6  352.04  5514.4  351.89
  5528.7  354.75  5539.9  353.69  5563.8  353.18  5663.4   355.9  5778.6  361.63
#Mann= 6 ,-1 , 0
  3906.6     .08       0  4131.8     .05       0  4998.1     .03       0
  5004.1     .05       0  5480.6     .16       0  5539.9     .05       0
Bank Sta=4629.5,5024.9
XS Rating Curve= 0 ,0
Exp/Cntr=0.3,0.1

Type RM Length L Ch R = 1 ,1307    ,851,851,851
BEGIN DESCRIPTION:
UNT 072 IN UKCR 2.0
END DESCRIPTION:
XS GIS Cut Line= 3
      3620949.63     10588860.19      3619956.55     10588822.34
      3619449.59     10589460.22
#Sta/Elev= 30
  4099.6   350.2  4227.8  339.18  4259.7   339.2  4379.8  335.57    4570  334.24
  4720.1  332.14  4790.1   332.3  4820.1  333.88  4860.2  333.19  4980.3  334.12
  4997.3  329.64    5000  329.14  5003.3  329.64  5010.3  334.21  5030.3  337.66
  5040.3  337.93  5060.3  334.96  5092.8  335.07  5143.9  335.39  5200.3  335.67
  5321.8  336.41  5367.5  337.04  5381.9  338.93  5414.7  338.72  5530.9  339.05
  5580.6  340.63  5601.6  342.49  5644.6  341.75  5708.7   342.9  5908.2  348.44
#Mann= 8 ,-1 , 0
  4099.6     .05       0  4997.3     .03       0  5003.3     .05       0
  5092.8      .1       0  5143.9     .15       0  5200.3      .1       0
  5321.8     .08       0  5414.7     .05       0
Bank Sta=4570,5010.3
XS Rating Curve= 0 ,0
Exp/Cntr=0.3,0.1

Type RM Length L Ch R = 1 ,456     ,0,0,0
BEGIN DESCRIPTION:
UNT 072 IN UKCR 1.0
END DESCRIPTION:
XS GIS Cut Line= 3
       3621049.6     10588860.18      3619775.99      10588377.9
      3619089.45     10589466.65
#Sta/Elev= 30
  3742.2   353.5  3763.9  353.64  3780.5  353.46  3812.2   350.8  3817.6  347.59
  3842.4  343.91  3867.2  342.92  3872.6  340.96  3897.4  341.58    3989  337.74
  4298.2   332.2  4640.4  331.03  4914.8  330.28  4982.6  330.92  4993.3  325.22
  4999.3  324.45    5001   323.9  5003.8   323.4    5007   323.9  5014.7  329.42
  5031.2  329.44  5109.7   327.9  5142.5  329.21  5219.1  330.99  5349.8  334.54
    5611  337.94  5726.4  336.63  5935.9   337.8  6233.7  342.24  6391.2  347.42
#Mann= 10 ,-1 , 0
  3742.2     .05       0  3763.9      .1       0  3780.5     .08       0
    3989     .05       0  4914.8     .16       0  4999.3     .12       0
    5001     .07       0    5007     .12       0  5031.2     .16       0
  5142.5     .05       0
Bank Sta=4640.4,5219.1
XS Rating Curve= 0 ,0
Exp/Cntr=0.3,0.1

Chan Stop Cuts=-1
Use User Specified Reach Order=0
Composite Channel Slope=5