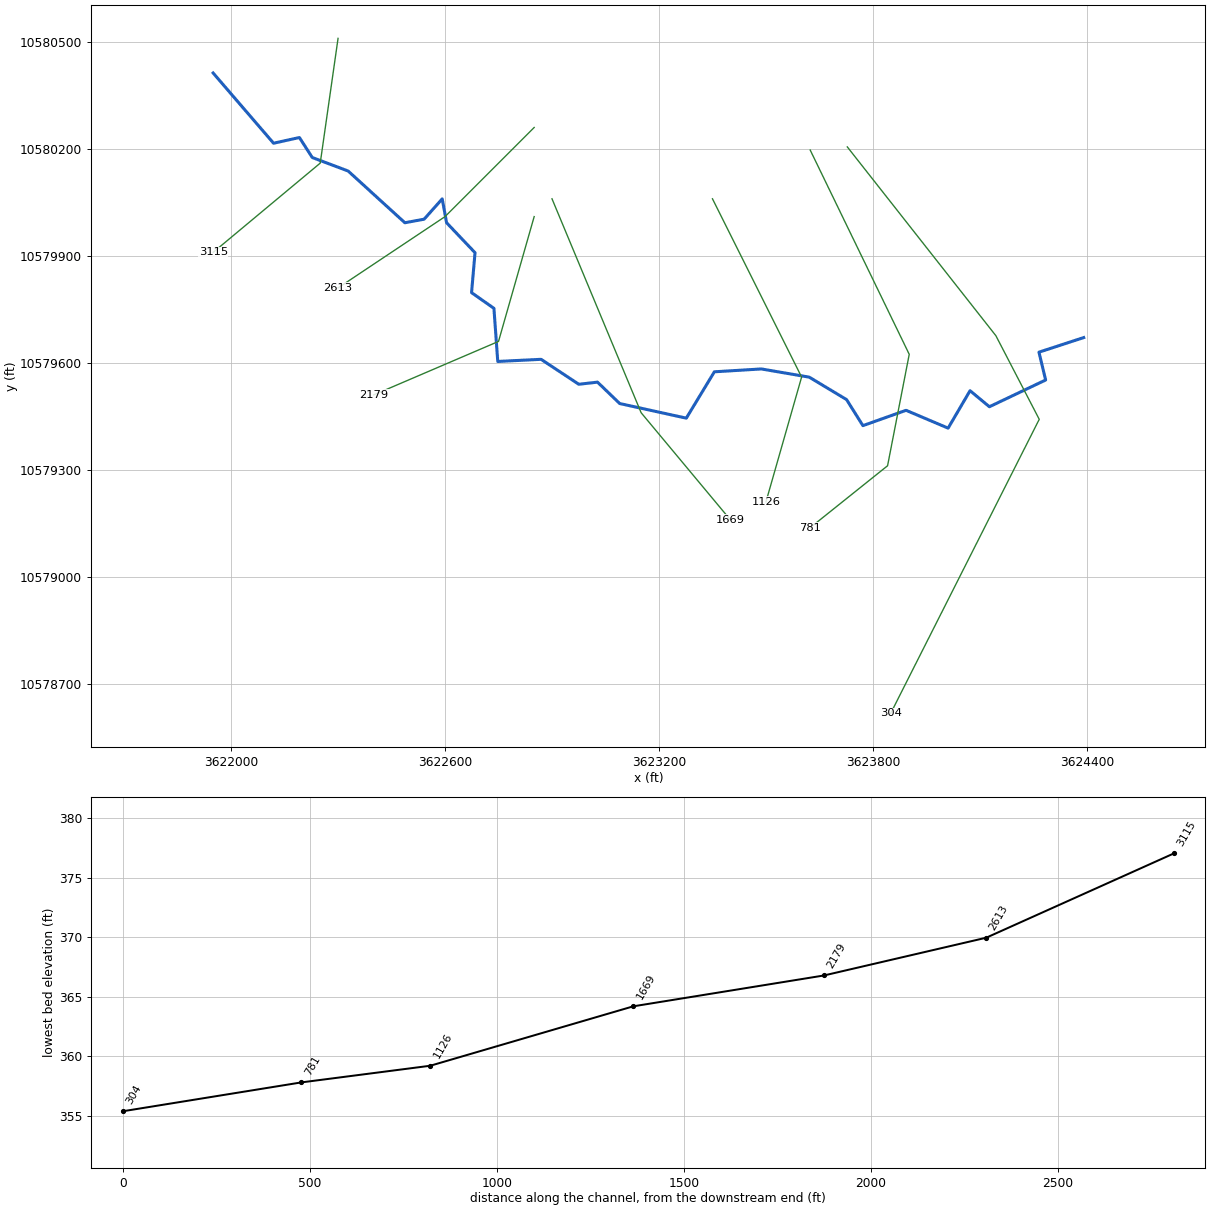
--- UNT 082 IN UKCR.prj (project) ---

Proj Title=UNT 082 IN UKCR Base Level Engineering
Current Plan=p01
Default Exp/Contr=0.3,0.1
English Units
Geom File=g01
Flow File=f01
Plan File=p01
BEGIN DESCRIPTION:
UNT 082 IN UKCR
END DESCRIPTION:

--- UNT 082 IN UKCR.p01 (plan) ---

Plan Title=Multiple Run
Short Identifier=Multiple
Geom File=g01
Flow File=f01
Subcritical Flow
K Sum by GR= 0
Std Step Tol= 0.01
Critical Tol= 0.01
Num of Std Step Trials= 20
Max Error Tol= 0.3
Flow Tol Ratio= 0.001
Split Flow NTrial= 30
Split Flow Tol= 0.02
Split Flow Ratio= 0.02
Log Output Level= 0
Friction Slope Method= 1
Unsteady Friction Slope Method= 2
Unsteady Bridges Friction Slope Method= 1
Parabolic Critical Depth
Global Vel Dist=  1 , 1 , 1
Global Log Level= 0
CheckData=True
Encroach Param= -1, 0, 0, 0
BEGIN DESCRIPTION:
Multiple Run
END DESCRIPTION:

--- UNT 082 IN UKCR.f01 (steady flow) ---

Flow Title=Multiple
Number of Profiles=7
Profile Names=10-year,25-year,50-year,1pct_min,100-year,1pct_plu,500-year
River Rch & RM= UNT 082 IN UKCR,Reach-1,3115
    1302    1840    2300    2101    2841    3842    4318
Boundary for River Rch & Prof#=UNT 082 IN UKCR,Reach-1,1
Up Type=0
Dn Type=3
Dn Slope=0.005
Boundary for River Rch & Prof#=UNT 082 IN UKCR,Reach-1,2
Up Type=0
Dn Type=3
Dn Slope=0.005
Boundary for River Rch & Prof#=UNT 082 IN UKCR,Reach-1,3
Up Type=0
Dn Type=3
Dn Slope=0.005
Boundary for River Rch & Prof#=UNT 082 IN UKCR,Reach-1,4
Up Type=0
Dn Type=3
Dn Slope=0.005
Boundary for River Rch & Prof#=UNT 082 IN UKCR,Reach-1,5
Up Type=0
Dn Type=3
Dn Slope=0.005
Boundary for River Rch & Prof#=UNT 082 IN UKCR,Reach-1,6
Up Type=0
Dn Type=3
Dn Slope=0.005
Boundary for River Rch & Prof#=UNT 082 IN UKCR,Reach-1,7
Up Type=0
Dn Type=3
Dn Slope=0.005

--- UNT 082 IN UKCR.g01 (geometry) ---

Geom Title=Existing Conditions

River Reach=UNT 082 IN UKCR,Reach-1
Reach XY= 30
      3621949.25     10580413.00      3622118.75     10580216.00
      3622191.25     10580232.00      3622227.25     10580176.00
      3622328.00     10580138.00      3622487.00     10579993.00
      3622541.00     10580003.00      3622591.75     10580060.00
      3622604.00     10579993.00      3622683.75     10579909.00
      3622674.00     10579797.00      3622736.75     10579753.00
      3622747.50     10579604.00      3622869.00     10579610.00
      3622974.75     10579540.00      3623027.25     10579546.00
      3623089.50     10579486.00      3623276.25     10579445.00
      3623355.00     10579575.00      3623486.75     10579583.00
      3623621.00     10579560.00      3623725.75     10579497.00
      3623771.50     10579424.00      3623892.50     10579467.00
      3624010.50     10579417.00      3624072.00     10579522.00
      3624126.25     10579477.00      3624284.00     10579552.00
      3624265.25     10579630.00      3624390.75     10579671.00

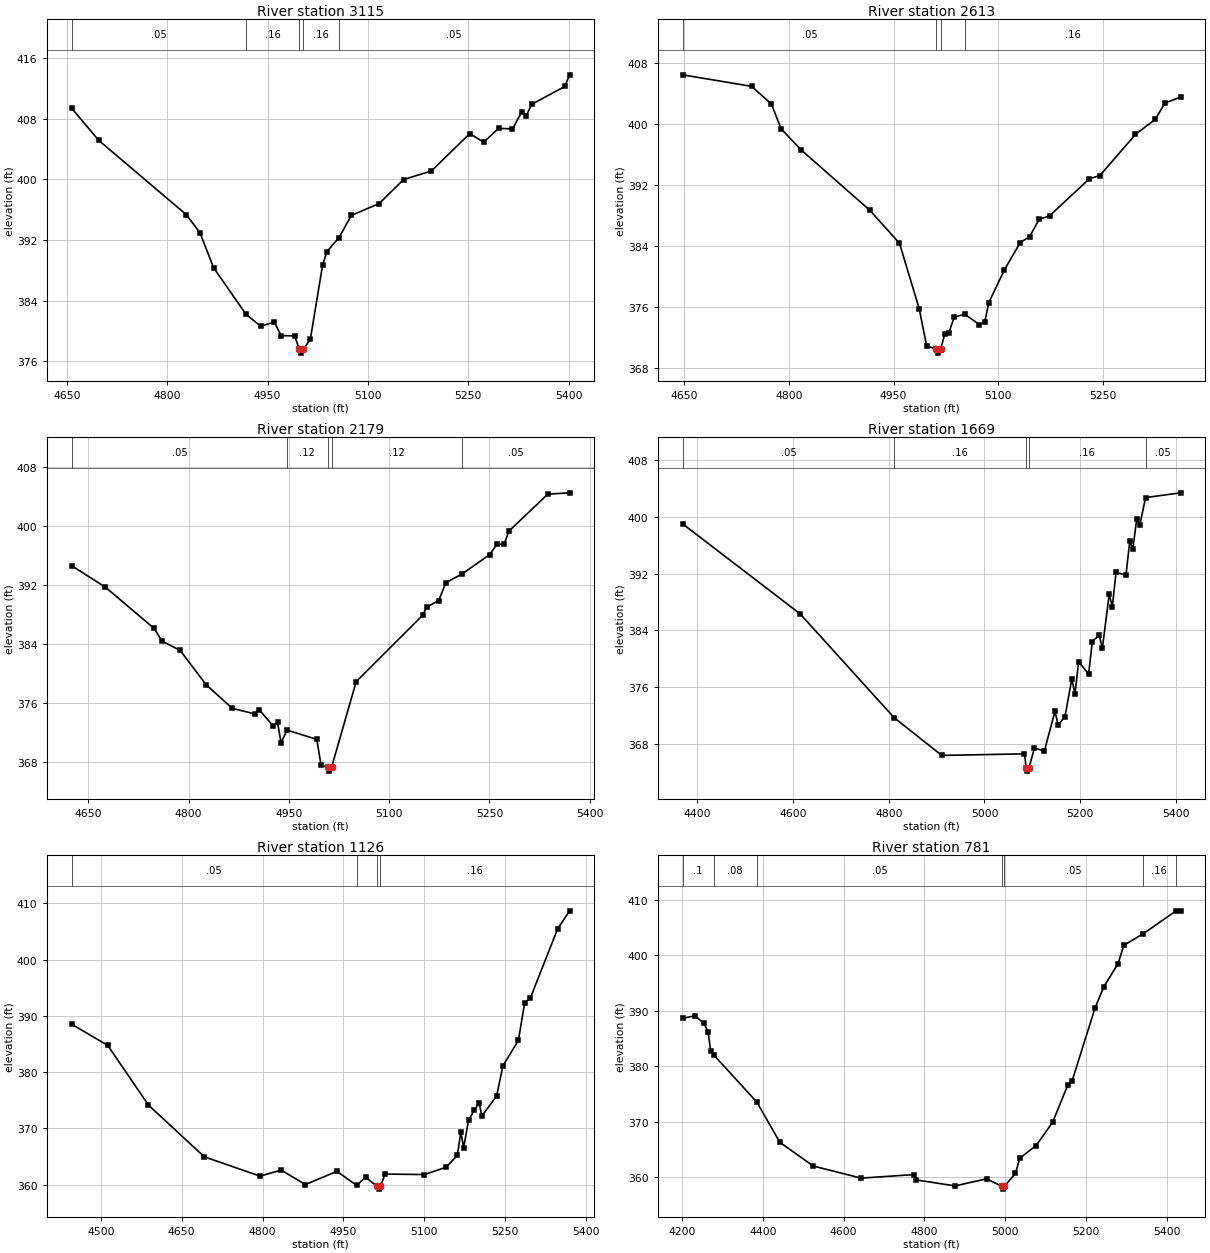
Type RM Length L Ch R = 1,3115,502,502,502
BEGIN DESCRIPTION:
UNT 082 IN UKCR 6.0
END DESCRIPTION:
XS GIS Cut Line= 3
      3622299.61     10580510.18      3622249.61     10580160.19
      3621949.58     10579910.16
#Sta/Elev= 30
  4657.1  409.42  4697.5  405.17  4828.8  395.32  4849.0  392.94  4869.2  388.35
  4917.8  382.17  4939.9  380.60  4960.1  381.16  4970.2  379.36  4990.4  379.33
  4997.5  377.55  5000.3  377.05  5003.5  377.55  5013.9  378.89  5032.1  388.63
  5038.6  390.46  5056.7  392.31  5075.1  395.24  5116.7  396.81  5153.2  399.98
  5194.8  401.11  5252.1  406.05  5272.9  404.91  5295.1  406.74  5315.9  406.67
  5330.2  408.96  5336.7  408.43  5344.5  409.91  5394.0  412.27  5401.2  413.81
#Mann=5,-1,0
  4657.1    0.05       0  4917.8    0.16       0  4997.5    0.07       0
  5003.5    0.16       0  5056.7    0.05       0
Bank Sta=4997.5,5003.5
Exp/Cntr=0.3,0.1

Type RM Length L Ch R = 1,2613,434,434,434
BEGIN DESCRIPTION:
UNT 082 IN UKCR 5.0
END DESCRIPTION:
XS GIS Cut Line= 3
      3622849.62     10580260.20      3622599.61     10580010.19
      3622299.63     10579810.20
#Sta/Elev= 30
  4647.3  406.48  4746.3  404.97  4774.6  402.67  4788.7  399.40  4817.0  396.66
  4916.0  388.70  4958.4  384.39  4986.7  375.80  4997.3  370.94  5011.4  370.47
  5014.1  369.97  5017.4  370.47  5023.4  372.50  5029.4  372.67  5036.9  374.72
  5052.2  375.06  5073.0  373.71  5080.5  373.99  5086.5  376.60  5109.0  380.92
  5131.6  384.48  5145.1  385.26  5158.6  387.51  5173.6  387.98  5230.7  392.85
  5245.7  393.26  5296.8  398.66  5325.4  400.66  5338.9  402.77  5361.4  403.56
#Mann=4,-1,0
  4647.3    0.05       0  5011.4    0.03       0  5017.4    0.05       0
  5052.2    0.16       0
Bank Sta=5011.4,5017.4
Exp/Cntr=0.3,0.1

Type RM Length L Ch R = 1,2179,510,510,510
BEGIN DESCRIPTION:
UNT 082 IN UKCR 4.0
END DESCRIPTION:
XS GIS Cut Line= 3
      3622849.62     10580010.23      3622749.61     10579660.19
      3622399.64     10579510.20
#Sta/Elev= 30
  4625.1  394.68  4675.8  391.75  4748.6  386.16  4760.3  384.45  4787.6  383.17
  4826.6  378.50  4865.6  375.31  4899.4  374.56  4905.9  375.11  4926.7  372.92
  4933.2  373.40  4938.4  370.67  4947.4  372.37  4991.9  371.10  4998.2  367.63
  5007.9  367.30  5010.7  366.80  5013.9  367.30  5050.8  378.95  5150.5  387.97
  5156.0  389.04  5174.1  389.94  5185.0  392.38  5209.6  393.58  5250.3  396.17
  5261.1  397.57  5272.0  397.57  5279.3  399.37  5337.3  404.38  5369.9  404.56
#Mann=5,-1,0
  4625.1    0.05       0  4947.4    0.12       0  5007.9    0.07       0
  5013.9    0.12       0  5209.6    0.05       0
Bank Sta=5007.9,5013.9
Exp/Cntr=0.3,0.1

Type RM Length L Ch R = 1,1669,543,543,543
BEGIN DESCRIPTION:
UNT 082 IN UKCR 3.0
END DESCRIPTION:
XS GIS Cut Line= 3
      3622899.60     10580060.20      3623149.61     10579460.19
      3623399.59     10579160.21
#Sta/Elev= 30
  4369.1  399.01  4614.5  386.36  4811.3  371.73  4910.8  366.42  5083.5  366.64
  5087.1  364.71  5089.8  364.21  5093.1  364.71  5104.4  367.47  5125.2  367.04
  5147.3  372.64  5153.8  370.68  5168.2  371.89  5182.5  377.20  5189.0  375.05
  5196.8  379.58  5217.6  377.88  5225.4  382.45  5239.8  383.36  5246.3  381.49
  5260.6  389.08  5267.1  387.37  5274.9  392.16  5295.7  391.81  5303.5  396.55
  5310.0  395.44  5317.9  399.63  5324.4  398.80  5336.6  402.70  5409.6  403.37
#Mann=5,-1,0
  4369.1    0.05       0  4811.3    0.16       0  5087.1    0.07       0
  5093.1    0.16       0  5336.6    0.05       0
Bank Sta=5087.1,5093.1
Exp/Cntr=0.3,0.1

Type RM Length L Ch R = 1,1126,345,345,345
BEGIN DESCRIPTION:
UNT 082 IN UKCR 2.0
END DESCRIPTION:
XS GIS Cut Line= 3
      3623349.59     10580060.22      3623599.61     10579560.19
      3623499.60     10579210.15
#Sta/Elev= 30
  4446.0  388.54  4513.1  384.76  4588.6  374.15  4692.0  364.97  4795.4  361.53
  4834.6  362.61  4879.3  360.03  4938.0  362.38  4974.3  359.90  4991.1  361.31
  5012.5  359.72  5015.2  359.22  5018.5  359.72  5027.2  361.90  5100.0  361.81
  5140.3  363.12  5161.1  365.22  5167.6  369.35  5172.8  366.61  5181.9  371.47
  5192.3  373.21  5201.4  374.55  5206.6  372.21  5233.9  375.78  5245.6  381.15
  5274.2  385.64  5285.9  392.36  5296.3  393.15  5347.0  405.47  5369.1  408.68
#Mann=4,-1,0
  4446.0    0.05       0  4974.3    0.16       0  5012.5    0.07       0
  5018.5    0.16       0
Bank Sta=5012.5,5018.5
Exp/Cntr=0.3,0.1

Type RM Length L Ch R = 1,781,477,477,477
BEGIN DESCRIPTION:
Mapping XS 53bc18af
END DESCRIPTION:
XS GIS Cut Line= 4
      3623623.68     10580196.95      3623901.46     10579624.03
      3623840.70     10579311.53      3623624.14     10579138.28
#Sta/Elev= 30
  4201.5  388.59  4231.7  389.06  4254.2  387.73  4264.6  386.19  4271.3  382.72
  4278.5  382.02  4385.5  373.50  4442.4  366.25  4525.1  361.98  4643.6  359.80
  4773.4  360.44  4779.0  359.49  4876.0  358.40  4954.2  359.68  4991.9  358.32
  4994.7  357.82  4997.9  358.32  5025.5  360.65  5036.0  363.39  5076.4  365.66
  5117.2  369.85  5154.7  376.53  5165.5  377.30  5222.0  390.38  5244.0  394.30
  5279.2  398.43  5293.6  401.75  5341.1  403.82  5421.7  407.90  5433.9  407.97
#Mann=7,-1,0
  4201.5     0.1       0  4278.5    0.08       0  4385.5    0.05       0
  4991.9    0.03       0  4997.9    0.05       0  5341.1    0.16       0
  5421.7     0.1       0
Bank Sta=4991.9,4997.9
Exp/Cntr=0.3,0.1

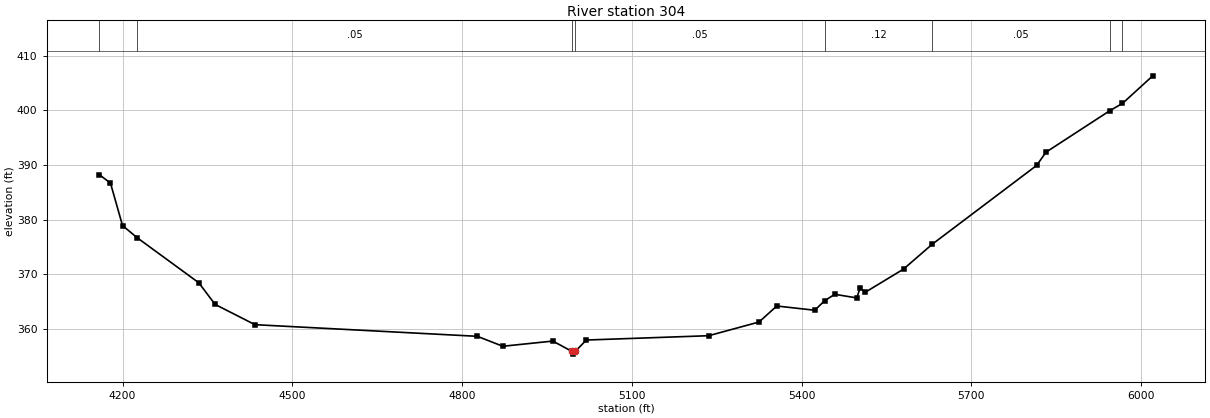
Type RM Length L Ch R = 1,304,0,0,0
BEGIN DESCRIPTION:
UNT 082 IN UKCR 1.0
END DESCRIPTION:
XS GIS Cut Line= 4
      3623727.82     10580205.66      3624144.52     10579676.11
      3624266.05     10579441.73      3623849.38     10578617.07
#Sta/Elev= 30
  4158.9  388.25  4178.6  386.70  4199.9  378.93  4226.1  376.68  4334.6  368.47
  4363.5  364.50  4434.0  360.79  4827.0  358.66  4872.0  356.84  4960.5  357.79
  4994.1  355.90  4996.9  355.40  5000.1  355.90  5019.6  357.98  5235.8  358.77
  5324.9  361.28  5356.2  364.21  5423.4  363.43  5440.7  365.17  5458.7  366.35
  5497.6  365.69  5503.3  367.47  5513.0  366.75  5580.2  370.96  5630.9  375.51
  5815.5  389.94  5832.0  392.36  5944.7  399.95  5967.2  401.29  6020.7  406.34
#Mann=8,-1,0
  4158.9     0.1       0  4226.1    0.05       0  4994.1    0.03       0
  5000.1    0.05       0  5440.7    0.12       0  5630.9    0.05       0
  5944.7    0.16       0  5967.2    0.05       0
Bank Sta=4994.1,5000.1
Exp/Cntr=0.3,0.1

Chan Stop Cuts=-1