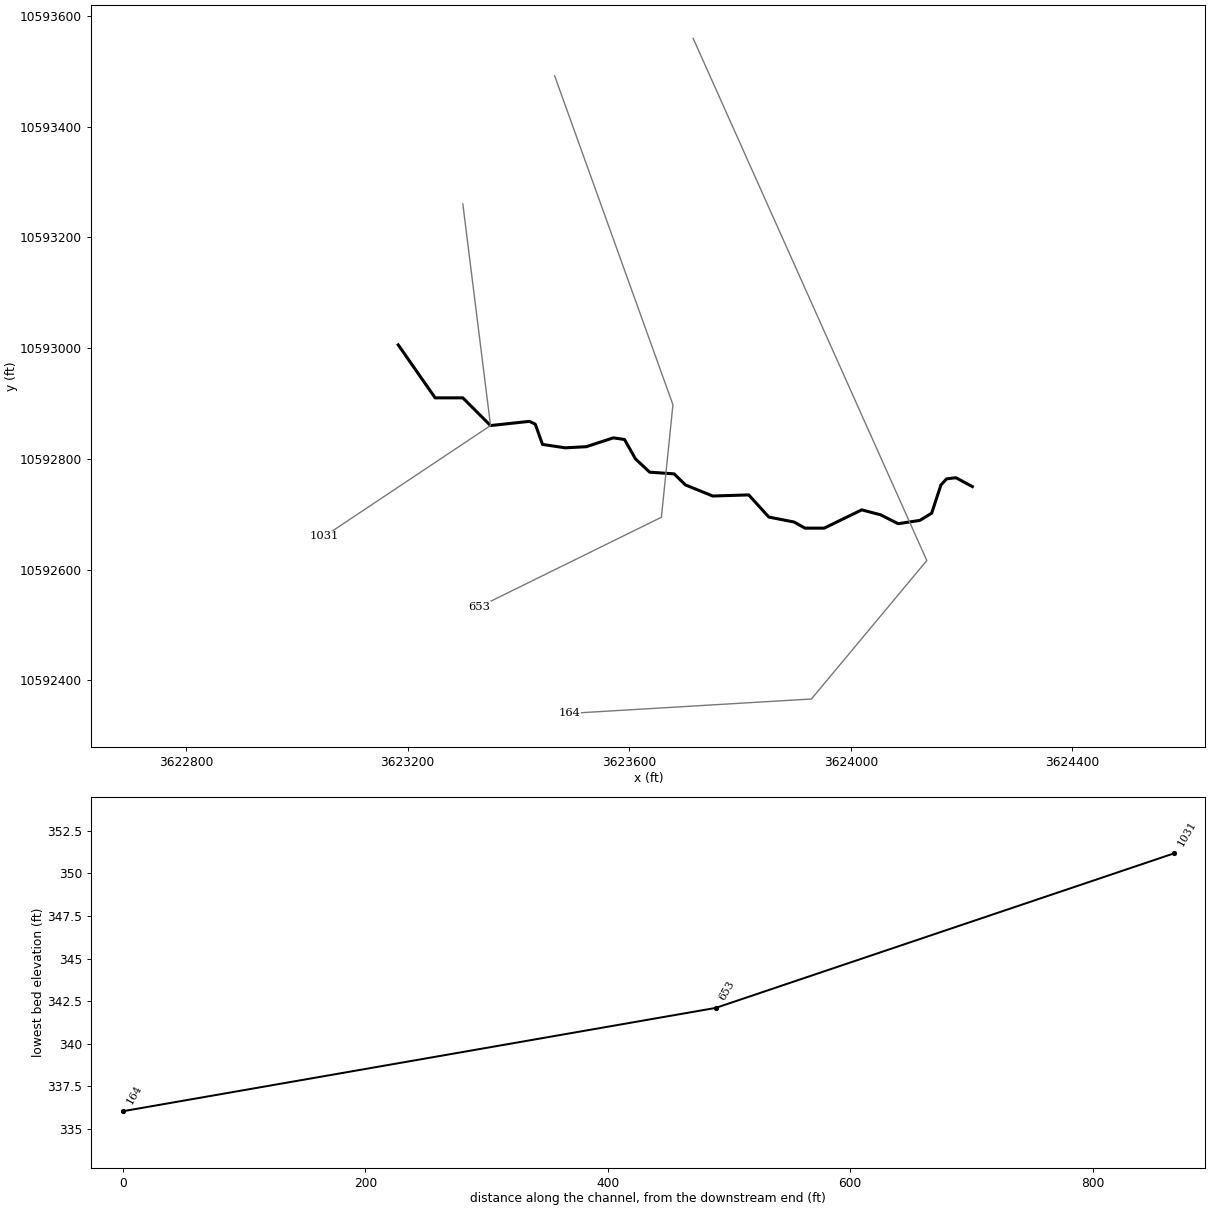
--- UNT 085 IN UKCR.prj (project) ---

Proj Title=UNT 085 IN UKCR Base Level Engineering
Current Plan=p01
Default Exp/Contr=0.3,0.1
English Units
Geom File=g01
Flow File=f01
Plan File=p01
Y Axis Title=Elevation
X Axis Title(PF)=Main Channel Distance
X Axis Title(XS)=Station
BEGIN DESCRIPTION:
UNT 085 IN UKCR
END DESCRIPTION:
DSS Export Rating Curves= 0
DSS Export Rating Curve Sorted= 0
DSS Export Volume Flow Curves= 0
DXF OffsetX= 0
DXF OffsetY= 0
DXF ScaleX= 1
DXF ScaleY= 10

--- UNT 085 IN UKCR.p01 (plan) ---

Plan Title=Multiple Run
Program Version=4.10
Short Identifier=Multiple
Geom File=g01
Flow File=f01
Subcritical Flow
K Sum by GR= 0
Std Step Tol= 0.01
Critical Tol= 0.01
Num of Std Step Trials= 20
Max Error Tol= 0.3
Flow Tol Ratio= 0.001
Split Flow NTrial= 30
Split Flow Tol= 0.02
Split Flow Ratio= 0.02
Log Output Level= 0
Friction Slope Method= 1
Unsteady Friction Slope Method= 2
Unsteady Bridges Friction Slope Method= 1
Parabolic Critical Depth
Global Vel Dist= 1 , 1 , 1
Global Log Level= 0
CheckData=True
Encroach Param=-1 ,0,0, 0
BEGIN DESCRIPTION:
Multiple Run
END DESCRIPTION:
Computation Interval=1HOUR
Output Interval=1HOUR
Run HTab= 0
Run UNet= 0
Run PostProcess= 0
Run WQNet= 0
UNET Theta= 1
UNET Theta Warmup= 1
UNET ZTol= 0.02
UNET ZSATol= 0.05
UNET MxIter= 20
UNET MaxInSteps= 0
UNET DtIC= 0
UNET DtMin= 0
UNET MaxCRTS= 20
UNET WFStab= 2
UNET SFStab= 1
UNET WFX= 1
UNET SFX= 1
UNET DSS MLevel= 4
UNET DZMax Abort= 100
UNET Convert EG Bridges= 0
UNET Use Existing IB Tables=-1
UNET Froude Reduction=False
UNET Froude Limit= 1
UNET Froude Power= 10
UNET Time Slicing=0,0, 5
UNET Junction Losses=0
Instantaneous Interval=1HOUR
Write IC File= 0
Write IC File at Sim End=0
Echo Input=False
Echo Parameters=False
Echo Output=False
Write Detailed= 0
WQ AD Non Conservative
WQ ULTIMATE=-1
WQ Max Comp Step=1HOUR
WQ Output Interval=15MIN
WQ Output Selected Increments= 0
WQ Output face flow=0
WQ Output face velocity=0
WQ Output face area=0
WQ Output face dispersion=0
WQ Output cell volume=0
WQ Output cell surface area=0
WQ Output cell continuity=0
WQ Output cumulative cell continuity=0
WQ Output face conc=0
WQ Output face dconc_dx=0
WQ Output face courant=0
WQ Output face peclet=0
WQ Output face adv mass=0
WQ Output face disp mass=0
WQ Output cell mass=0
WQ Output cell source sink temp=0
WQ Output cell source sink nsm=0
WQ Output MaxMinRange=-1
WQ Daily Max Min Mean=-1
WQ Daily Range=0
WQ Daily Time=0
WQ Create Restart=0
WQ Fixed Restart=0
WQ System Summary=0
WQ Use Fixed Temperature=0
Sorting and Armoring Iterations= 10
XS Update Threshold= 0.02
Hydraulics Update Threshold= 0.02
Energy Slope Method= 1
Volume Change Method= 0
XS Weighting Method= 0
Number of US Weighted Cross Sections= 1
Number of DS Weighted Cross Sections= 1
Upstream XS Weight=0.25
Main XS Weight=0.5
Downstream XS Weight=0.25
Number of DS XS's Weighted with US Boundary= 1
Upstream Boundary Weight= 1
Weight of XSs Associated with US Boundary= 0
Number of US XS's Weighted with DS Boundary= 1
Downstream Boundary Weight= 0.5
Weight of XSs Associated with DS Boundary= 0.5
Sediment Output Level= 4
Mass or Volume Output= 0
Output Increment Type= 1
Profile and TS Output Increment= 10
XS Output Flag= 0
XS Output Increment= 10
Disregard all LS=0
Disregard all Conn=0
Disregard all Breaches=0
Disregard all Pumps=0

--- UNT 085 IN UKCR.f01 (steady flow) ---

Flow Title=Multiple
Program Version=4.10
Number of Profiles= 7
Profile Names=10-year,25-year,50-year,1pct_min,100-year,1pct_plu,500-year
River Rch & RM=UNT 085 IN UKCR,Reach-1         ,1031
     274     347     403     344     466     630     615
Boundary for River Rch & Prof#=UNT 085 IN UKCR,Reach-1         , 1
Up Type= 0
Dn Type= 3
Dn Slope=0.005
Boundary for River Rch & Prof#=UNT 085 IN UKCR,Reach-1         , 2
Up Type= 0
Dn Type= 3
Dn Slope=0.005
Boundary for River Rch & Prof#=UNT 085 IN UKCR,Reach-1         , 3
Up Type= 0
Dn Type= 3
Dn Slope=0.005
Boundary for River Rch & Prof#=UNT 085 IN UKCR,Reach-1         , 4
Up Type= 0
Dn Type= 3
Dn Slope=0.005
Boundary for River Rch & Prof#=UNT 085 IN UKCR,Reach-1         , 5
Up Type= 0
Dn Type= 3
Dn Slope=0.005
Boundary for River Rch & Prof#=UNT 085 IN UKCR,Reach-1         , 6
Up Type= 0
Dn Type= 3
Dn Slope=0.005
Boundary for River Rch & Prof#=UNT 085 IN UKCR,Reach-1         , 7
Up Type= 0
Dn Type= 3
Dn Slope=0.005
DSS Import GetInterval= 0
DSS Import GetPeak= 0
DSS Import FillOption= 0

--- UNT 085 IN UKCR.g01 (geometry) ---

Geom Title=Existing Conditions
Program Version=4.10

River Reach=UNT 085 IN UKCR ,Reach-1
Reach XY= 30
      3623183.04     10593005.81      3623249.61     10592910.19
      3623299.61     10592910.19      3623349.61     10592860.19
      3623420.02     10592867.79      3623430.44     10592862.58
      3623443.46     10592826.12       3623484.5       10592820.
       3623522.5       10592822.      3623571.25       10592838.
       3623591.5       10592835.      3623611.25       10592800.
        3623637.       10592776.        3623681.       10592773.
       3623701.5       10592753.      3623750.75       10592733.
      3623815.75       10592735.        3623852.       10592695.
      3623897.75       10592686.      3623917.25       10592675.
        3623952.       10592675.      3624019.75       10592708.
        3624054.       10592699.       3624085.5       10592683.
      3624124.75       10592689.        3624146.       10592702.
      3624162.75       10592753.        3624173.       10592764.
      3624189.75       10592766.       3624219.5       10592750.

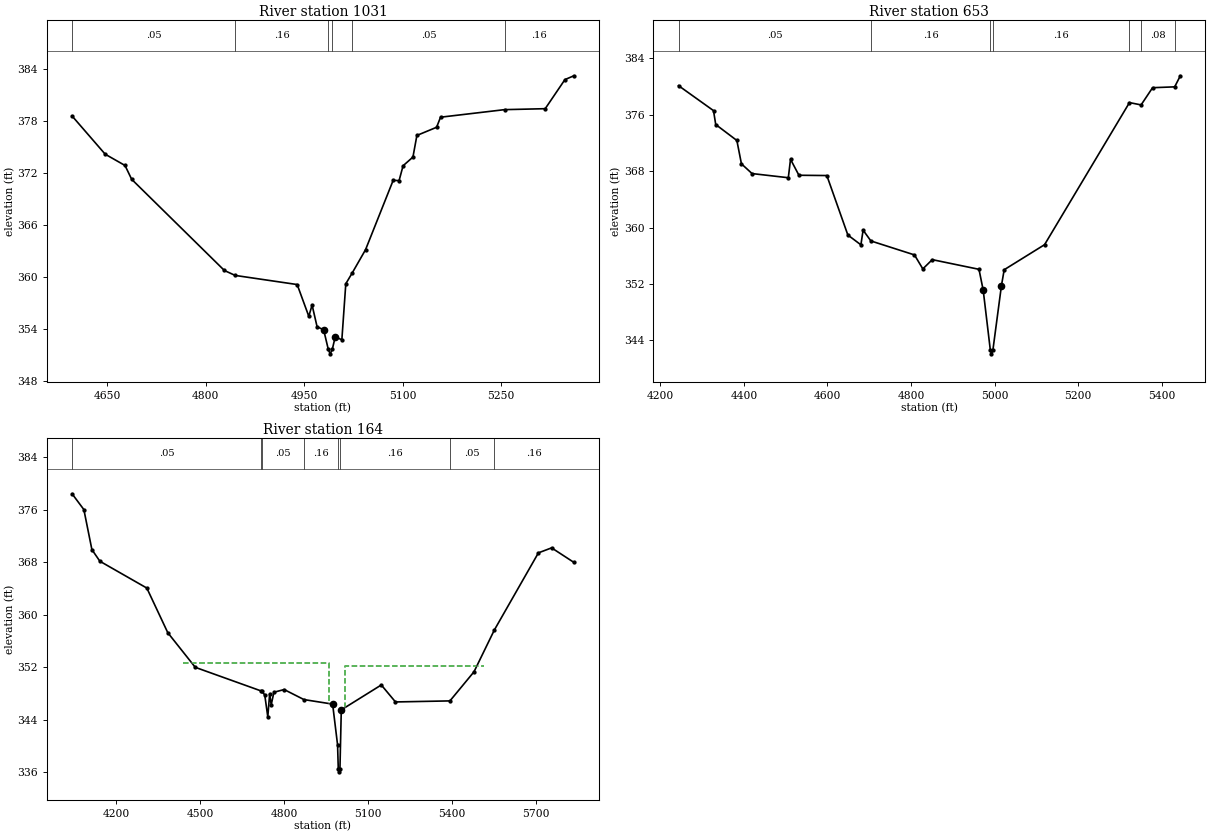
Type RM Length L Ch R = 1 ,1031    ,378,378,378
BEGIN DESCRIPTION:
UNT 085 IN UKCR 2.0
END DESCRIPTION:
XS GIS Cut Line= 3
      3623299.61     10593260.18      3623349.61     10592860.19
      3623049.57     10592660.16
#Sta/Elev= 30
  4596.9  378.57  4647.3  374.17  4677.5  372.87  4687.6  371.28  4828.7  360.78
  4845.1  360.21  4939.5  359.16  4957.2   355.5  4962.2   356.8  4969.8   354.3
  4979.8  353.95  4986.9  351.68  4989.7  351.18  4992.9  351.68  4997.5  353.16
  5007.5  352.79  5013.5  359.25  5023.4  360.51  5043.6  363.18  5085.6  371.16
  5094.6  371.13  5100.7  372.84  5115.7  373.84  5121.7  376.33  5151.7  377.27
  5157.7  378.43  5255.1   379.3    5317  379.41    5347  382.76  5360.6   383.2
#Mann= 6 ,-1 , 0
  4596.9     .05       0  4845.1     .16       0  4986.9     .07       0
  4992.9     .16       0  5023.4     .05       0  5255.1     .16       0
Bank Sta=4979.8,4997.5
XS Rating Curve= 0 ,0
Exp/Cntr=0.3,0.1

Type RM Length L Ch R = 1 ,653     ,489,489,489
BEGIN DESCRIPTION:
Mapping XS f8fb40bf
END DESCRIPTION:
XS GIS Cut Line= 4
      3623465.38     10593491.51      3623678.92     10592897.79
      3623658.08     10592694.66        3623330.     10592533.23
#Sta/Elev= 30
  4243.6  380.11  4327.3  376.57  4332.6   374.6  4383.2  372.34  4394.1  369.03
  4419.5  367.65  4506.3  367.06  4511.6  369.67  4531.7  367.41  4598.5  367.37
  4648.8  358.94    4680  357.55  4685.3  359.63  4703.9   358.1  4808.2  356.12
  4828.2  354.14  4850.8  355.45  4962.6  354.08  4972.7  351.11  4989.8   342.6
  4992.5   342.1  4995.8   342.6  5016.3  351.76  5022.9  354.02  5119.5  357.57
  5322.7  377.71  5350.5  377.38    5378  379.82  5430.9  379.94  5444.4  381.51
#Mann= 7 ,-1 , 0
  4243.6     .05       0  4703.9     .16       0  4989.8     .07       0
  4995.8     .16       0  5322.7     .05       0  5350.5     .08       0
  5430.9      .1       0
Bank Sta=4972.7,5016.3
XS Rating Curve= 0 ,0
Exp/Cntr=0.3,0.1

Type RM Length L Ch R = 1 ,164     ,0,0,0
BEGIN DESCRIPTION:
UNT 085 IN UKCR 1.0
END DESCRIPTION:
XS GIS Cut Line= 4
      3623715.38     10593559.23      3624137.25     10592616.54
      3623928.92     10592366.54        3623493.     10592340.59
#Sta/Elev= 30
    4042  378.44  4084.2  376.03  4112.9  369.93  4141.5  368.15  4309.4  364.06
  4384.4  357.25  4482.7  351.97  4719.4  348.35  4720.4  348.35  4731.2  347.76
  4742.1  344.42  4748.8  347.95  4754.3  346.25    4764  348.17  4800.7  348.58
  4871.5  347.05    4974  346.36  4991.7  340.14  4994.2  336.53    4997  336.03
  5000.2  336.53    5005  345.48  5148.1  349.28  5198.8  346.69  5393.6  346.85
  5479.7  351.29  5552.7  357.68  5710.1  369.43  5757.3  370.19  5836.9  367.98
#Mann= 8 ,-1 , 0
    4042     .05       0  4719.4     .16       0  4720.4     .05       0
  4871.5     .16       0  4994.2     .07       0  5000.2     .16       0
  5393.6     .05       0  5552.7     .16       0
#XS Ineff= 2 ,-1
  4437.5 4960.23  352.59 5018.18 5514.77  352.15
Permanent Ineff=
       F       F
Bank Sta=4974,5005
XS Rating Curve= 0 ,0
Exp/Cntr=0.3,0.1

Chan Stop Cuts=-1
Use User Specified Reach Order=0
Composite Channel Slope=5