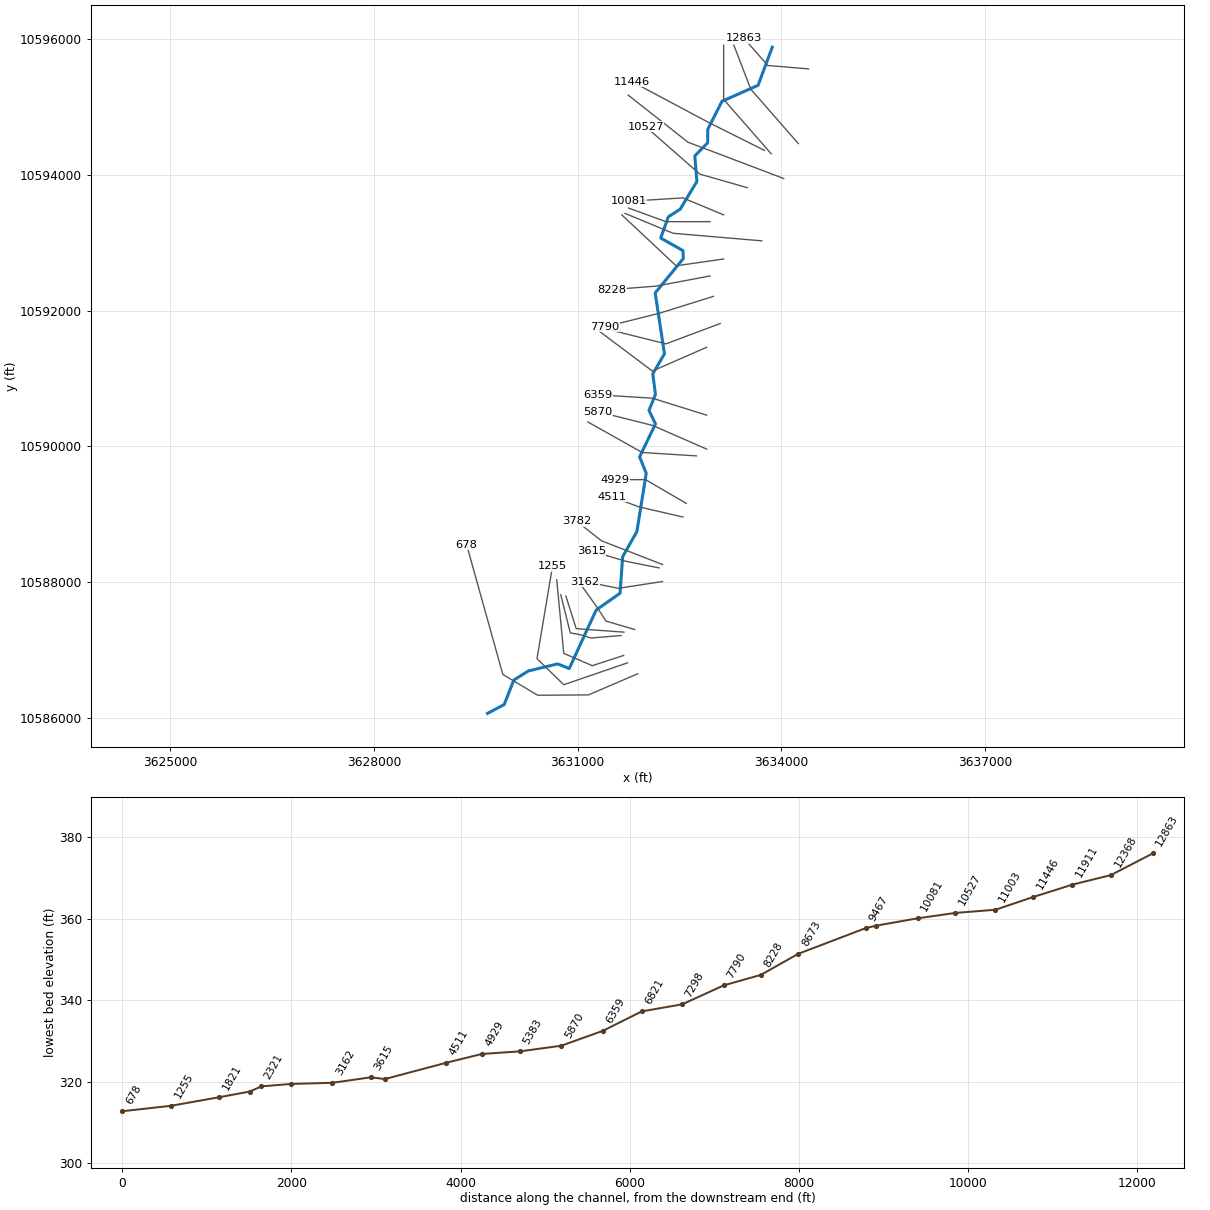
--- UNT 087 IN UKCR.prj (project) ---

Proj Title=UNT 087 IN UKCR Base Level Engineering
Current Plan=p01
Default Exp/Contr=0.3,0.1
English Units
Geom File=g01
Flow File=f01
Plan File=p01
BEGIN DESCRIPTION:
UNT 087 IN UKCR
END DESCRIPTION:

--- UNT 087 IN UKCR.p01 (plan) ---

Plan Title=Multiple Run
Short Identifier=Multiple
Geom File=g01
Flow File=f01
Subcritical Flow
K Sum by GR= 0
Std Step Tol= 0.01
Critical Tol= 0.01
Num of Std Step Trials= 20
Max Error Tol= 0.3
Flow Tol Ratio= 0.001
Split Flow NTrial= 30
Split Flow Tol= 0.02
Split Flow Ratio= 0.02
Log Output Level= 0
Friction Slope Method= 1
Unsteady Friction Slope Method= 2
Unsteady Bridges Friction Slope Method= 1
Parabolic Critical Depth
Global Vel Dist=  1 , 1 , 1
Global Log Level= 0
CheckData=True
Encroach Param= -1, 0, 0, 0
BEGIN DESCRIPTION:
Multiple Run
END DESCRIPTION:

--- UNT 087 IN UKCR.f01 (steady flow) ---

Flow Title=Multiple
Number of Profiles=7
Profile Names=10-year,25-year,50-year,1pct_min,100-year,1pct_plu,500-year
River Rch & RM= UNT 087 IN UKCR,Reach-1,12863
    1433    2034    2549    2334    3156    4268    4820
River Rch & RM= UNT 087 IN UKCR,Reach-1,12368
    2207    3197    4059    3759    5083    6875    7948
River Rch & RM= UNT 087 IN UKCR,Reach-1,7790
    2588    3759    4781    4429    5989    8100    9374
River Rch & RM= UNT 087 IN UKCR,Reach-1,678
    3209    4709    6029    5618    7598   10275   12037
Boundary for River Rch & Prof#=UNT 087 IN UKCR,Reach-1,1
Up Type=0
Dn Type=3
Dn Slope=0.005
Boundary for River Rch & Prof#=UNT 087 IN UKCR,Reach-1,2
Up Type=0
Dn Type=3
Dn Slope=0.005
Boundary for River Rch & Prof#=UNT 087 IN UKCR,Reach-1,3
Up Type=0
Dn Type=3
Dn Slope=0.005
Boundary for River Rch & Prof#=UNT 087 IN UKCR,Reach-1,4
Up Type=0
Dn Type=3
Dn Slope=0.005
Boundary for River Rch & Prof#=UNT 087 IN UKCR,Reach-1,5
Up Type=0
Dn Type=3
Dn Slope=0.005
Boundary for River Rch & Prof#=UNT 087 IN UKCR,Reach-1,6
Up Type=0
Dn Type=3
Dn Slope=0.005
Boundary for River Rch & Prof#=UNT 087 IN UKCR,Reach-1,7
Up Type=0
Dn Type=3
Dn Slope=0.005

--- UNT 087 IN UKCR.g01 (geometry) ---

Geom Title=Existing Conditions

River Reach=UNT 087 IN UKCR,Reach-1
Reach XY= 30
      3633865.50     10595879.00      3633656.25     10595318.00
      3633124.75     10595083.00      3632915.00     10594669.00
      3632914.00     10594472.00      3632724.75     10594278.00
      3632755.75     10593902.00      3632509.75     10593495.00
      3632335.50     10593382.00      3632222.00     10593069.00
      3632550.25     10592884.00      3632555.50     10592767.00
      3632141.25     10592260.00      3632277.75     10591364.00
      3632106.00     10591069.00      3632145.00     10590765.00
      3632050.00     10590530.00      3632145.25     10590331.00
      3631911.50     10589845.00      3632009.00     10589605.00
      3631872.00     10588747.00      3631662.25     10588375.00
      3631623.50     10587837.00      3631271.75     10587590.00
      3630875.25     10586728.00      3630705.00     10586797.00
      3630273.25     10586693.00      3630059.00     10586559.00
      3629917.50     10586198.00      3629672.25     10586068.00

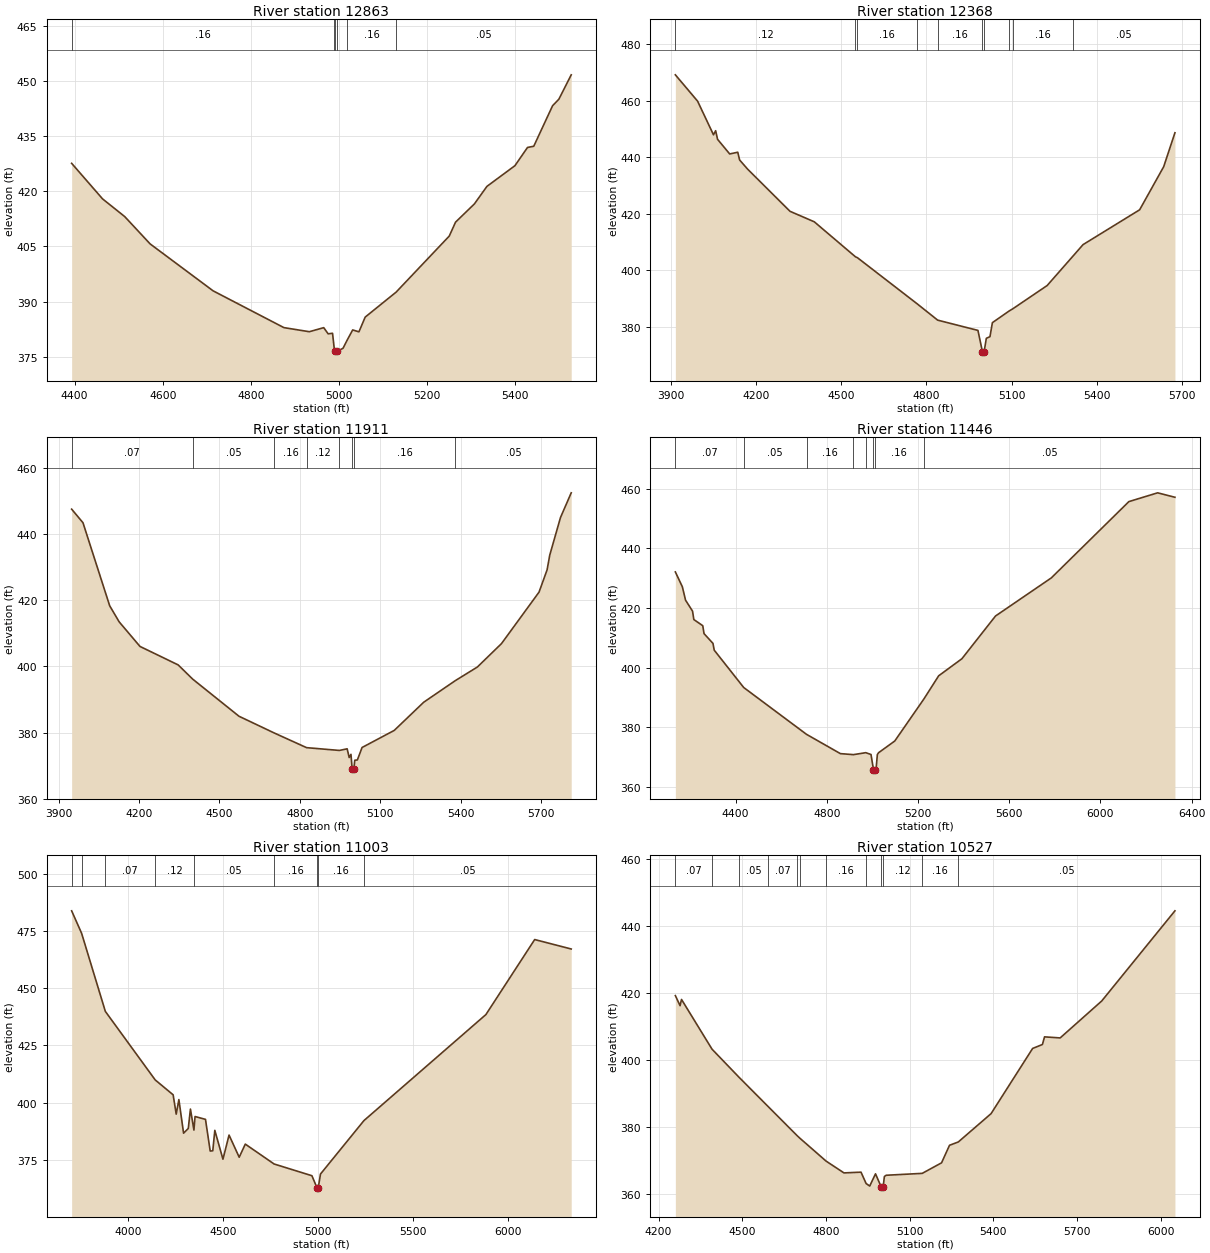
Type RM Length L Ch R = 1,12863,495,495,495
BEGIN DESCRIPTION:
UNT 087 IN UKCR 26.0
END DESCRIPTION:
XS GIS Cut Line= 3
      3634399.60     10595560.19      3633799.61     10595610.19
      3633449.59     10596010.21
#Sta/Elev= 30
  4393.1  427.58  4463.3  417.91  4513.5  413.11  4571.2  405.68  4714.2  392.92
  4874.8  382.93  4932.4  381.82  4965.1  382.92  4975.1  381.25  4985.1  381.39
  4989.0  377.24  4989.7  376.50  4992.4  376.00  4995.7  376.50  5008.9  377.32
  5018.5  379.58  5030.8  382.30  5045.0  381.79  5059.2  385.79  5129.4  392.58
  5250.0  407.82  5264.2  411.59  5307.0  416.55  5335.4  421.31  5399.0  426.94
  5427.5  431.89  5441.7  432.22  5484.4  443.23  5498.7  445.01  5526.7  451.63
#Mann=6,-1,0
  4393.1    0.16       0  4989.0    0.12       0  4989.7    0.07       0
  4995.7    0.12       0  5018.5    0.16       0  5129.4    0.05       0
Bank Sta=4989.7,4995.7
Exp/Cntr=0.3,0.1

Type RM Length L Ch R = 1,12368,457,457,457
BEGIN DESCRIPTION:
UNT 087 IN UKCR 25.0
END DESCRIPTION:
XS GIS Cut Line= 3
      3634249.62     10594460.17      3633549.61     10595260.19
      3633299.59     10595910.23
#Sta/Elev= 30
  3916.1  469.14  3994.4  459.83  4050.4  447.92  4058.0  449.37  4064.7  446.33
  4107.4  441.15  4135.8  441.75  4142.5  439.00  4171.0  435.73  4320.0  420.85
  4405.4  417.14  4550.3  404.77  4557.5  404.43  4767.3  388.16  4839.9  382.35
  4981.8  378.72  4997.6  371.18  5000.3  370.68  5003.6  371.18  5011.3  375.93
  5024.1  376.49  5032.7  381.46  5091.1  385.55  5104.5  386.36  5225.6  394.60
  5314.9  404.82  5352.0  409.07  5551.3  421.39  5635.9  436.62  5675.6  448.64
#Mann=10,-1,0
  3916.1    0.12       0  4550.3    0.07       0  4557.5    0.16       0
  4767.3    0.05       0  4839.9    0.16       0  4997.6    0.07       0
  5003.6    0.16       0  5091.1    0.12       0  5104.5    0.16       0
  5314.9    0.05       0
Bank Sta=4997.6,5003.6
Exp/Cntr=0.3,0.1

Type RM Length L Ch R = 1,11911,465,465,465
BEGIN DESCRIPTION:
UNT 087 IN UKCR 24.0
END DESCRIPTION:
XS GIS Cut Line= 3
      3633849.64     10594310.15      3633149.61     10595110.19
      3633149.61     10595910.22
#Sta/Elev= 30
  3948.6  447.48  3990.9  443.37  4090.5  418.28  4125.7  413.44  4203.5  406.00
  4345.9  400.42  4399.7  396.15  4572.7  384.91  4704.5  379.84  4824.8  375.42
  4947.1  374.58  4976.1  375.07  4983.7  372.44  4990.3  373.40  4994.9  368.83
  4997.7  368.33  5000.9  368.83  5004.5  371.61  5014.2  371.71  5031.7  375.47
  5151.7  380.63  5261.7  389.15  5379.8  395.69  5461.7  399.78  5551.7  406.86
  5691.7  422.41  5721.7  429.14  5731.7  433.61  5771.7  444.95  5811.7  452.41
#Mann=8,-1,0
  3948.6    0.07       0  4399.7    0.05       0  4704.5    0.16       0
  4824.8    0.12       0  4947.1    0.16       0  4994.9    0.07       0
  5000.9    0.16       0  5379.8    0.05       0
Bank Sta=4994.9,5000.9
Exp/Cntr=0.3,0.1

Type RM Length L Ch R = 1,11446,443,443,443
BEGIN DESCRIPTION:
UNT 087 IN UKCR 23.0
END DESCRIPTION:
XS GIS Cut Line= 3
      3633749.58     10594360.20      3632949.61     10594760.19
      3631804.82     10595369.41
#Sta/Elev= 30
  4135.5  432.11  4166.2  427.12  4180.2  422.63  4210.9  418.95  4216.5  416.14
  4255.7  414.07  4261.3  411.41  4300.4  408.14  4306.0  405.86  4435.2  393.34
  4710.8  377.62  4859.4  371.15  4916.5  370.81  4970.5  371.47  4993.6  370.86
  5004.5  365.78  5007.3  365.28  5010.5  365.78  5015.9  366.01  5021.5  370.85
  5027.1  371.47  5097.9  375.39  5225.3  389.45  5290.4  397.26  5392.4  402.99
  5539.7  417.32  5784.4  430.10  6124.6  455.70  6250.8  458.65  6326.7  457.16
#Mann=8,-1,0
  4135.5    0.07       0  4435.2    0.05       0  4710.8    0.16       0
  4916.5    0.12       0  4970.5    0.16       0  5004.5    0.07       0
  5010.5    0.16       0  5225.3    0.05       0
Bank Sta=5004.5,5010.5
Exp/Cntr=0.3,0.1

Type RM Length L Ch R = 1,11003,476,476,476
BEGIN DESCRIPTION:
UNT 087 IN UKCR 22.0
END DESCRIPTION:
XS GIS Cut Line= 3
      3634034.03     10593945.77      3632624.31     10594480.50
      3631743.51     10595174.04
#Sta/Elev= 30
  3705.1  483.79  3757.5  473.99  3882.4  439.85  4144.8  409.90  4239.2  403.39
  4255.3  394.94  4269.4  401.31  4294.1  386.63  4318.9  388.68  4330.2  397.17
  4348.5  387.98  4354.4  393.91  4409.4  392.66  4434.2  378.82  4447.8  378.93
  4458.5  387.86  4501.3  375.25  4533.4  385.80  4586.8  376.12  4618.9  381.85
  4770.5  373.16  4969.4  368.04  4996.5  362.68  4999.3  362.18  5002.5  362.68
  5014.6  368.78  5243.1  392.12  5885.1  438.47  6141.7  471.24  6333.9  467.11
#Mann=9,-1,0
  3705.1    0.05       0  3757.5    0.12       0  3882.4    0.07       0
  4144.8    0.12       0  4348.5    0.05       0  4770.5    0.16       0
  4996.5    0.07       0  5002.5    0.16       0  5243.1    0.05       0
Bank Sta=4996.5,5002.5
Exp/Cntr=0.3,0.1

Type RM Length L Ch R = 1,10527,446,446,446
BEGIN DESCRIPTION:
UNT 087 IN UKCR 21.0
END DESCRIPTION:
XS GIS Cut Line= 3
      3633499.64     10593810.18      3632799.61     10594010.19
      3631999.58     10594710.22
#Sta/Elev= 30
  4260.3  419.13  4277.2  416.12  4282.4  417.98  4391.8  403.14  4488.6  394.76
  4592.7  386.05  4696.7  377.36  4705.9  376.64  4800.7  369.75  4864.8  366.23
  4925.9  366.45  4944.2  363.06  4957.1  362.31  4977.9  365.95  4999.1  361.89
  5001.9  361.39  5005.1  361.89  5009.7  365.16  5016.3  365.53  5145.3  366.09
  5214.7  369.24  5243.2  374.47  5274.7  375.46  5392.2  383.91  5541.2  403.36
  5576.3  404.54  5583.9  406.82  5639.9  406.50  5788.9  417.52  6051.4  444.42
#Mann=12,-1,0
  4260.3    0.07       0  4391.8    0.12       0  4488.6    0.05       0
  4592.7    0.07       0  4696.7     0.1       0  4705.9    0.05       0
  4800.7    0.16       0  4944.2    0.12       0  4999.1    0.07       0
  5005.1    0.12       0  5145.3    0.16       0  5274.7    0.05       0
Bank Sta=4999.1,5005.1
Exp/Cntr=0.3,0.1

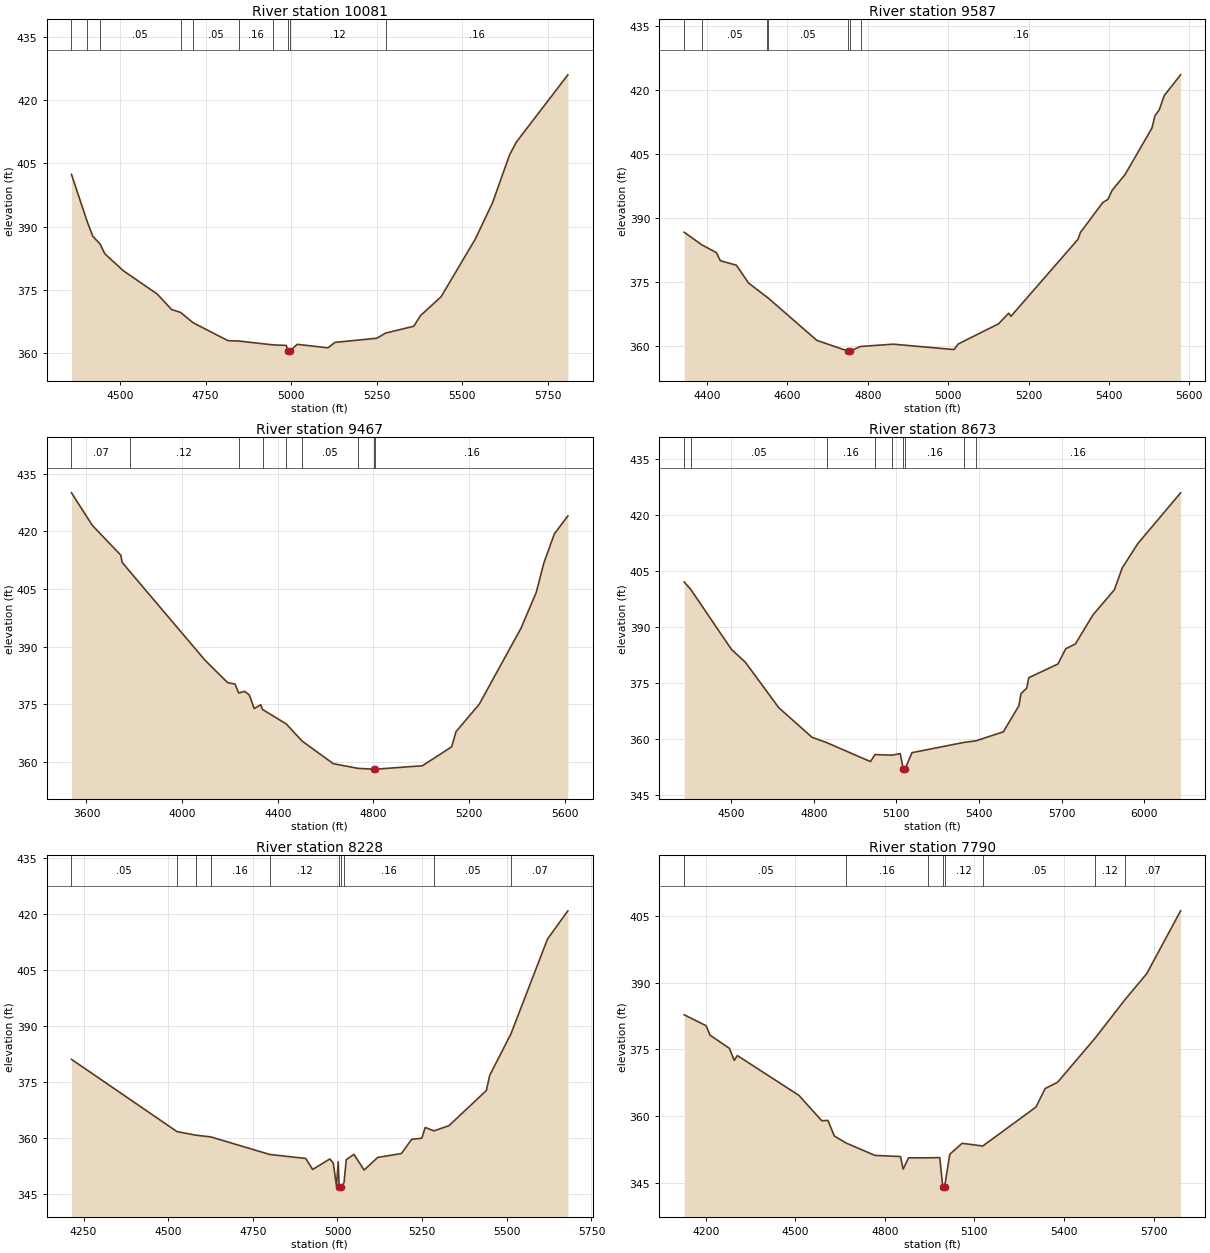
Type RM Length L Ch R = 1,10081,494,494,494
BEGIN DESCRIPTION:
UNT 087 IN UKCR 20.0
END DESCRIPTION:
XS GIS Cut Line= 3
      3633149.59     10593410.20      3632549.61     10593660.19
      3631749.65     10593610.19
#Sta/Elev= 30
  4357.7  402.37  4404.3  391.07  4420.0  387.73  4441.0  385.94  4455.2  383.59
  4509.3  379.58  4608.5  374.05  4650.2  370.40  4676.5  369.72  4713.2  367.27
  4815.4  363.02  4847.6  362.93  4947.2  362.02  4986.0  361.89  4990.1  360.57
  4992.8  360.07  4996.1  360.57  5017.7  362.15  5107.9  361.33  5127.9  362.61
  5250.7  363.60  5276.0  364.81  5358.4  366.43  5378.4  368.96  5438.5  373.42
  5538.7  387.10  5588.8  395.65  5638.9  407.04  5658.9  410.07  5809.2  425.95
#Mann=10,-1,0
  4357.7    0.12       0  4404.3    0.07       0  4441.0    0.05       0
  4676.5    0.16       0  4713.2    0.05       0  4847.6    0.16       0
  4947.2    0.12       0  4990.1    0.07       0  4996.1    0.12       0
  5276.0    0.16       0
Bank Sta=4990.1,4996.1
Exp/Cntr=0.3,0.1

Type RM Length L Ch R = 1,9587,120,120,120
BEGIN DESCRIPTION:
UNT 087 IN UKCR 19.0
END DESCRIPTION:
XS GIS Cut Line= 3
      3632949.64     10593310.19      3632299.61     10593310.19
      3631749.58     10593510.20
#Sta/Elev= 30
  4343.1  386.60  4386.3  383.69  4423.1  381.83  4433.1  379.92  4473.1  378.87
  4503.1  374.71  4549.9  371.32  4550.4  371.32  4673.1  361.25  4750.1  358.75
  4752.9  358.25  4756.1  358.75  4782.0  359.81  4863.1  360.35  5014.4  359.09
  5025.1  360.40  5125.5  365.13  5150.7  367.62  5156.1  366.88  5323.0  384.94
  5329.0  386.54  5384.8  393.58  5397.5  394.31  5408.1  396.45  5440.0  400.11
  5507.2  411.06  5514.5  413.92  5525.2  415.31  5537.8  418.68  5578.4  423.53
#Mann=7,-1,0
  4343.1    0.12       0  4386.3    0.05       0  4549.9    0.16       0
  4550.4    0.05       0  4750.1    0.07       0  4756.1    0.05       0
  4782.0    0.16       0
Bank Sta=4750.1,4756.1
Exp/Cntr=0.3,0.1

Type RM Length L Ch R = 1,9467,794,794,794
BEGIN DESCRIPTION:
UNT 087 IN UKCR 18.0
END DESCRIPTION:
XS GIS Cut Line= 3
      3633710.97     10593027.75      3632405.58     10593138.97
      3631697.29     10593431.65
#Sta/Elev= 30
  3537.3  430.00  3624.5  421.55  3743.6  413.79  3749.4  411.91  3781.6  409.53
  4095.9  386.49  4191.0  380.64  4221.1  380.32  4236.8  377.96  4261.3  378.40
  4281.3  377.45  4301.4  373.93  4329.1  374.91  4336.4  373.69  4436.0  369.91
  4502.7  365.44  4632.6  359.59  4734.8  358.39  4802.6  358.16  4805.3  357.66
  4808.6  358.16  5005.4  359.06  5127.7  363.99  5146.0  367.93  5243.4  375.09
  5417.8  394.82  5481.5  404.13  5513.4  411.78  5557.2  419.32  5613.8  424.00
#Mann=9,-1,0
  3537.3    0.07       0  3781.6    0.12       0  4236.8    0.07       0
  4336.4    0.12       0  4436.0    0.16       0  4502.7    0.05       0
  4734.8    0.16       0  4802.6    0.07       0  4808.6    0.16       0
Bank Sta=4802.6,4808.6
Exp/Cntr=0.3,0.1

Type RM Length L Ch R = 1,8673,445,445,445
BEGIN DESCRIPTION:
UNT 087 IN UKCR 17.0
END DESCRIPTION:
XS GIS Cut Line= 3
      3633149.61     10592760.19      3632449.61     10592660.19
      3631649.61     10593410.19
#Sta/Elev= 30
  4328.9  402.03  4352.9  400.02  4500.6  383.98  4551.1  380.54  4672.4  368.38
  4793.6  360.43  4847.0  359.01  5005.7  353.93  5022.2  355.81  5084.2  355.66
  5113.9  356.07  5125.1  351.88  5127.8  351.38  5131.1  351.88  5156.4  356.32
  5346.7  359.09  5388.8  359.49  5488.6  361.91  5545.2  368.92  5552.5  372.11
  5573.6  373.63  5580.9  376.40  5686.9  380.07  5715.2  384.15  5750.4  385.44
  5814.4  393.24  5892.0  399.95  5920.4  405.79  5977.0  412.29  6132.6  425.91
#Mann=9,-1,0
  4328.9    0.07       0  4352.9    0.05       0  4847.0    0.16       0
  5022.2    0.12       0  5084.2    0.16       0  5125.1    0.07       0
  5131.1    0.16       0  5346.7    0.12       0  5388.8    0.16       0
Bank Sta=5125.1,5131.1
Exp/Cntr=0.3,0.1

Type RM Length L Ch R = 1,8228,438,438,438
BEGIN DESCRIPTION:
UNT 087 IN UKCR 16.0
END DESCRIPTION:
XS GIS Cut Line= 3
      3632949.61     10592510.19      3632149.61     10592360.19
      3631499.57     10592310.19
#Sta/Elev= 30
  4214.5  380.96  4526.3  361.59  4581.4  360.65  4626.2  360.17  4800.1  355.47
  4906.3  354.41  4926.7  351.46  4977.6  354.28  4987.7  353.12  4997.1  347.00
  5002.2  353.51  5005.1  346.69  5007.8  346.19  5011.1  346.69  5019.4  347.95
  5025.9  354.07  5048.5  355.51  5078.6  351.31  5118.7  354.68  5188.9  355.73
  5219.0  359.53  5249.1  359.83  5259.1  362.71  5284.9  361.80  5329.3  363.19
  5439.6  372.60  5449.7  376.70  5512.5  387.82  5620.2  413.18  5680.4  420.74
#Mann=10,-1,0
  4214.5    0.05       0  4526.3    0.12       0  4581.4    0.05       0
  4626.2    0.16       0  4800.1    0.12       0  5005.1    0.07       0
  5011.1    0.12       0  5019.4    0.16       0  5284.9    0.05       0
  5512.5    0.07       0
Bank Sta=5005.1,5011.1
Exp/Cntr=0.3,0.1

Type RM Length L Ch R = 1,7790,492,492,492
BEGIN DESCRIPTION:
UNT 087 IN UKCR 15.0
END DESCRIPTION:
XS GIS Cut Line= 3
      3632999.61     10592210.19      3632199.61     10591960.19
      3631399.58     10591760.18
#Sta/Elev= 30
  4127.9  382.77  4201.2  380.32  4214.3  378.20  4279.3  375.24  4295.5  372.54
  4306.0  373.62  4511.9  364.69  4588.9  358.97  4609.3  359.05  4630.8  355.55
  4671.3  353.94  4767.0  351.19  4852.4  350.94  4861.3  348.12  4879.6  350.65
  4943.3  350.65  4984.1  350.70  4994.0  344.12  4996.7  343.62  5000.0  344.12
  5017.6  351.45  5058.8  353.91  5128.0  353.30  5306.2  362.05  5337.1  366.22
  5378.4  367.60  5503.3  377.44  5604.3  386.16  5677.3  392.01  5790.7  406.12
#Mann=8,-1,0
  4127.9    0.05       0  4671.3    0.16       0  4943.3    0.12       0
  4994.0    0.07       0  5000.0    0.12       0  5128.0    0.05       0
  5503.3    0.12       0  5604.3    0.07       0
Bank Sta=4994,5000
Exp/Cntr=0.3,0.1

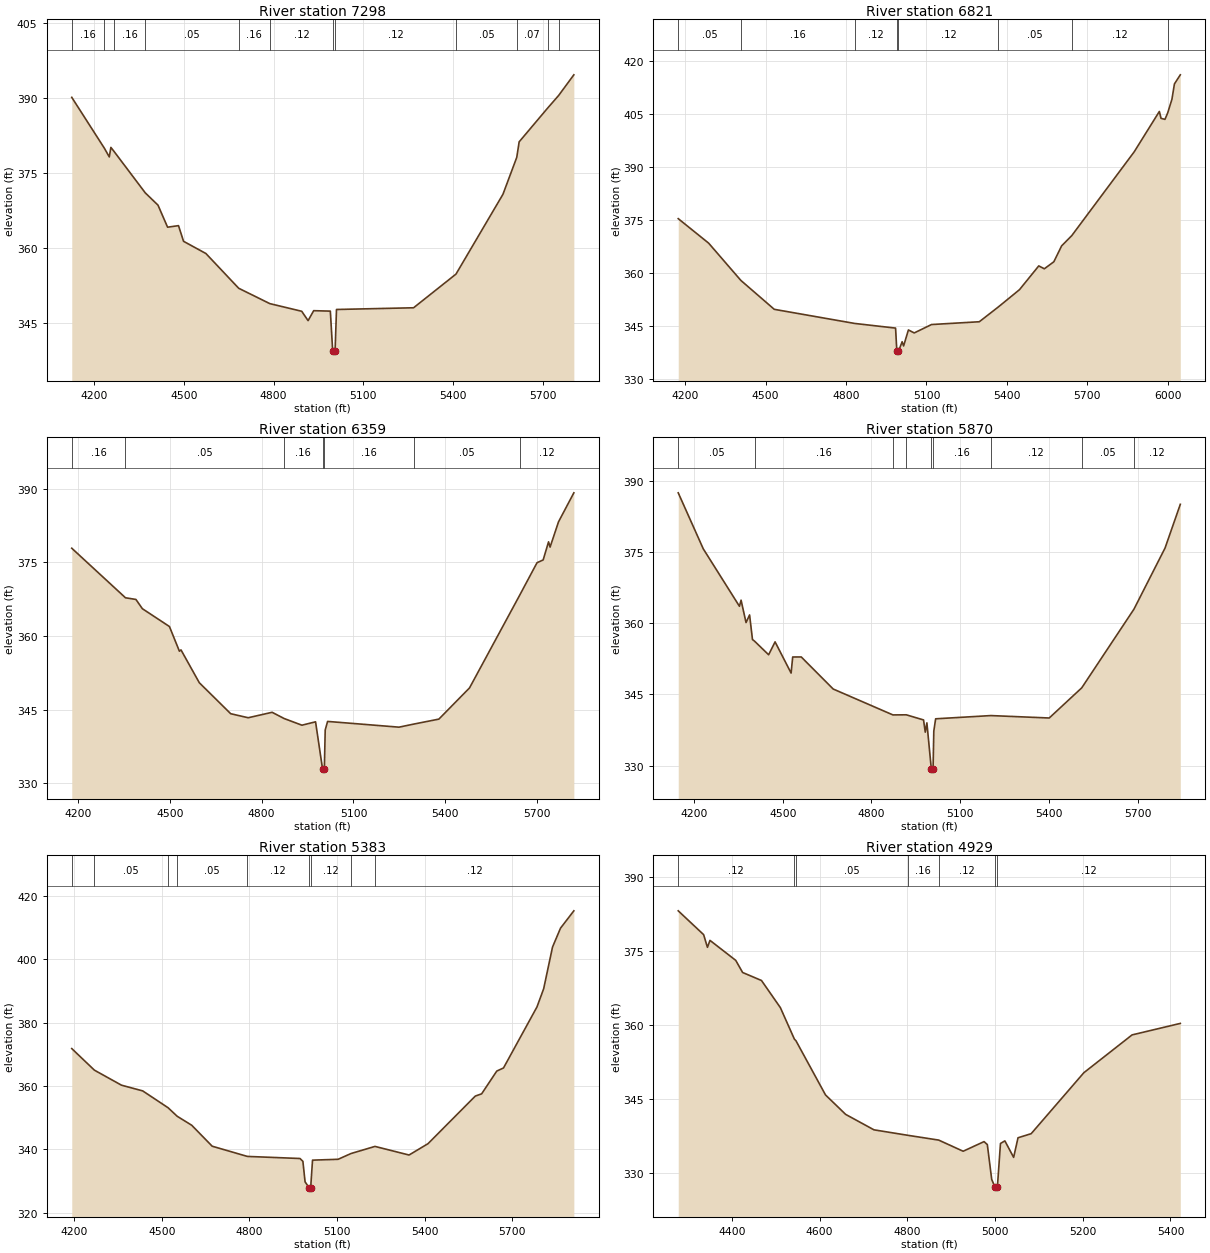
Type RM Length L Ch R = 1,7298,477,477,477
BEGIN DESCRIPTION:
UNT 087 IN UKCR 14.0
END DESCRIPTION:
XS GIS Cut Line= 3
      3633099.61     10591810.19      3632299.61     10591510.19
      3631499.64     10591710.18
#Sta/Elev= 30
  4125.1  390.07  4234.0  379.92  4250.6  378.17  4255.9  380.07  4266.8  379.24
  4370.9  370.99  4413.5  368.53  4445.5  364.13  4482.0  364.44  4498.9  361.31
  4573.7  358.87  4683.3  351.93  4787.4  348.86  4894.1  347.33  4915.4  345.46
  4934.1  347.45  4989.8  347.36  4997.5  339.55  4999.7  339.47  5002.4  338.97
  5005.7  339.47  5010.4  347.69  5268.1  348.03  5410.0  354.76  5567.0  370.70
  5613.2  378.08  5621.2  381.18  5716.1  387.90  5753.2  390.44  5804.1  394.57
#Mann=12,-1,0
  4125.1    0.16       0  4234.0    0.12       0  4266.8    0.16       0
  4370.9    0.05       0  4683.3    0.16       0  4787.4    0.12       0
  4999.7    0.07       0  5005.7    0.12       0  5410.0    0.05       0
  5613.2    0.07       0  5716.1    0.12       0  5753.2    0.07       0
Bank Sta=4999.7,5005.7
Exp/Cntr=0.3,0.1

Type RM Length L Ch R = 1,6821,462,462,462
BEGIN DESCRIPTION:
UNT 087 IN UKCR 13.0
END DESCRIPTION:
XS GIS Cut Line= 3
      3632899.65     10591460.21      3632099.61     10591110.19
      3631299.57     10591710.22
#Sta/Elev= 30
  4173.9  375.34  4287.4  368.40  4407.6  357.84  4532.2  349.65  4832.2  345.65
  4984.8  344.33  4989.6  337.74  4992.3  337.24  4995.6  337.74  5009.3  340.47
  5014.8  339.27  5032.7  343.81  5054.4  342.96  5119.0  345.34  5297.2  346.13
  5368.2  350.32  5447.2  355.22  5519.0  361.95  5539.9  361.14  5575.3  363.12
  5604.4  367.63  5642.4  370.55  5875.3  394.29  5969.0  405.71  5975.3  403.76
  5989.9  403.47  5999.9  405.25  6015.9  409.15  6025.3  413.52  6047.2  416.09
#Mann=8,-1,0
  4173.9    0.05       0  4407.6    0.16       0  4832.2    0.12       0
  4989.6    0.07       0  4995.6    0.12       0  5368.2    0.05       0
  5642.4    0.12       0  5999.9    0.07       0
Bank Sta=4989.6,4995.6
Exp/Cntr=0.3,0.1

Type RM Length L Ch R = 1,6359,489,489,489
BEGIN DESCRIPTION:
UNT 087 IN UKCR 12.0
END DESCRIPTION:
XS GIS Cut Line= 3
      3632899.61     10590460.19      3632099.61     10590710.19
      3631299.62     10590760.19
#Sta/Elev= 30
  4180.1  377.89  4355.5  367.79  4389.6  367.45  4410.6  365.57  4499.1  361.93
  4531.6  356.90  4536.8  357.17  4596.6  350.48  4699.2  344.16  4756.3  343.34
  4834.4  344.45  4873.7  343.18  4931.8  341.82  4976.3  342.51  4999.0  332.96
  5001.8  332.46  5005.0  332.96  5007.8  340.84  5015.6  342.59  5248.7  341.42
  5298.1  342.06  5379.0  343.06  5479.1  349.42  5643.6  368.39  5699.6  374.94
  5719.6  375.50  5737.2  379.19  5742.2  378.12  5769.7  383.26  5819.8  389.18
#Mann=7,-1,0
  4180.1    0.16       0  4355.5    0.05       0  4873.7    0.16       0
  4999.0    0.07       0  5005.0    0.16       0  5298.1    0.05       0
  5643.6    0.12       0
Bank Sta=4999,5005
Exp/Cntr=0.3,0.1

Type RM Length L Ch R = 1,5870,487,487,487
BEGIN DESCRIPTION:
UNT 087 IN UKCR 11.0
END DESCRIPTION:
XS GIS Cut Line= 3
      3632899.65     10589960.17      3632099.61     10590310.19
      3631299.59     10590510.19
#Sta/Elev= 30
  4146.5  387.49  4231.1  375.69  4353.5  363.57  4359.0  364.86  4375.8  360.14
  4387.8  361.75  4397.6  356.56  4404.6  356.22  4452.2  353.35  4474.0  356.07
  4528.2  349.49  4533.6  352.88  4562.5  352.89  4670.5  346.13  4872.5  340.67
  4917.8  340.69  4976.1  339.61  4981.9  337.03  4987.4  339.00  5002.3  329.32
  5005.1  328.82  5008.3  329.32  5010.8  337.28  5017.0  339.85  5203.9  340.53
  5401.1  340.02  5511.1  346.38  5687.6  362.96  5792.8  375.85  5844.4  385.07
#Mann=9,-1,0
  4146.5    0.05       0  4404.6    0.16       0  4872.5    0.12       0
  4917.8    0.16       0  5002.3    0.07       0  5008.3    0.16       0
  5203.9    0.12       0  5511.1    0.05       0  5687.6    0.12       0
Bank Sta=5002.3,5008.3
Exp/Cntr=0.3,0.1

Type RM Length L Ch R = 1,5383,454,454,454
BEGIN DESCRIPTION:
UNT 087 IN UKCR 10.0
END DESCRIPTION:
XS GIS Cut Line= 3
      3632749.57     10589860.19      3631949.61     10589910.19
      3631149.60     10590360.19
#Sta/Elev= 30
  4191.9  371.82  4269.4  365.01  4362.2  360.26  4434.8  358.46  4521.6  353.15
  4552.9  350.45  4602.7  347.61  4672.8  340.99  4793.2  337.77  4973.4  337.11
  4983.4  336.22  4990.9  329.74  5004.1  327.94  5006.9  327.44  5010.1  327.94
  5016.4  336.59  5104.0  336.86  5148.2  338.68  5230.3  340.93  5346.9  338.21
  5411.9  341.79  5573.8  356.82  5595.5  357.53  5647.4  364.72  5670.4  365.70
  5785.1  384.98  5808.0  390.73  5838.3  403.88  5865.7  409.85  5911.3  415.32
#Mann=9,-1,0
  4191.9    0.08       0  4269.4    0.05       0  4521.6    0.08       0
  4552.9    0.05       0  4793.2    0.12       0  5004.1    0.07       0
  5010.1    0.12       0  5148.2    0.16       0  5230.3    0.12       0
Bank Sta=5004.1,5010.1
Exp/Cntr=0.3,0.1

Type RM Length L Ch R = 1,4929,418,418,418
BEGIN DESCRIPTION:
UNT 087 IN UKCR 9.0
END DESCRIPTION:
XS GIS Cut Line= 3
      3632599.64     10589160.17      3631999.61     10589510.19
      3631549.56     10589510.19
#Sta/Elev= 30
  4277.8  383.20  4335.7  378.37  4344.4  375.80  4350.2  377.21  4408.9  373.16
  4424.6  370.70  4467.6  369.08  4510.6  363.59  4542.7  357.18  4546.1  356.88
  4613.6  345.88  4659.5  341.94  4724.0  338.81  4801.2  337.70  4871.6  336.73
  4927.4  334.47  4975.0  336.42  4982.5  335.82  4992.5  328.76  4999.5  327.29
  5002.2  326.79  5005.5  327.29  5012.5  336.04  5022.5  336.57  5042.5  333.23
  5052.5  337.20  5082.5  338.03  5202.5  350.38  5312.5  358.05  5422.5  360.38
#Mann=7,-1,0
  4277.8    0.12       0  4542.7    0.16       0  4546.1    0.05       0
  4801.2    0.16       0  4871.6    0.12       0  4999.5    0.07       0
  5005.5    0.12       0
Bank Sta=4999.5,5005.5
Exp/Cntr=0.3,0.1

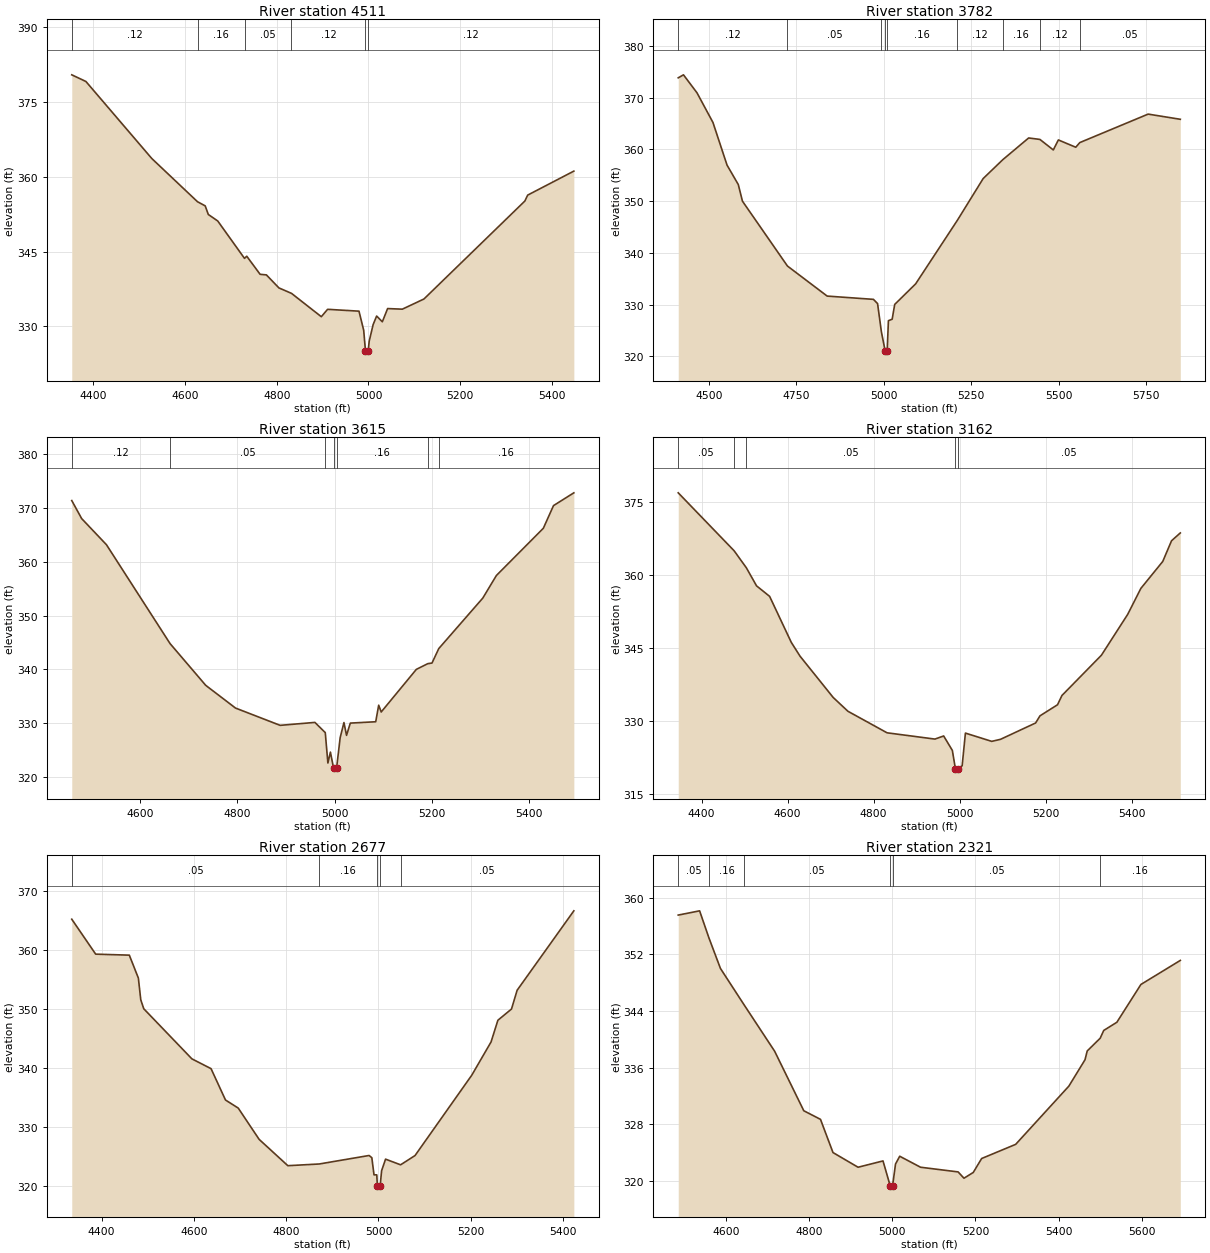
Type RM Length L Ch R = 1,4511,729,729,729
BEGIN DESCRIPTION:
UNT 087 IN UKCR 8.0
END DESCRIPTION:
XS GIS Cut Line= 3
      3632549.59     10588960.19      3631899.61     10589110.19
      3631499.58     10589260.20
#Sta/Elev= 30
  4353.3  380.43  4384.1  379.10  4527.8  363.65  4627.4  354.99  4644.1  354.17
  4650.9  352.44  4671.4  351.14  4729.8  343.64  4734.7  344.07  4763.8  340.45
  4777.5  340.33  4804.8  337.72  4832.2  336.63  4897.2  331.95  4910.9  333.43
  4979.3  333.06  4989.6  329.22  4993.4  325.15  4996.2  324.65  4999.4  325.15
  5001.6  327.05  5010.1  330.36  5017.8  332.08  5030.2  330.93  5041.7  333.58
  5073.8  333.46  5120.9  335.50  5340.8  355.13  5347.0  356.32  5447.6  361.13
#Mann=6,-1,0
  4353.3    0.12       0  4627.4    0.16       0  4729.8    0.05       0
  4832.2    0.12       0  4993.4    0.07       0  4999.4    0.12       0
Bank Sta=4993.4,4999.4
Exp/Cntr=0.3,0.1

Type RM Length L Ch R = 1,3782,167,167,167
BEGIN DESCRIPTION:
UNT 087 IN UKCR 7.0
END DESCRIPTION:
XS GIS Cut Line= 3
      3632249.64     10588260.18      3631349.61     10588610.19
      3630980.44     10588900.59
#Sta/Elev= 30
  4412.8  373.82  4427.8  374.40  4466.5  370.92  4512.1  365.19  4552.3  356.96
  4584.5  353.20  4596.4  349.99  4725.0  337.46  4838.6  331.65  4970.8  331.02
  4982.7  330.20  4993.6  324.75  5004.2  321.13  5006.9  320.63  5010.2  321.13
  5013.7  326.90  5024.4  327.18  5031.7  330.04  5091.5  334.01  5210.8  346.29
  5284.6  354.36  5340.6  358.00  5414.6  362.20  5446.8  361.92  5485.1  359.89
  5499.6  361.82  5549.3  360.41  5560.9  361.31  5756.2  366.81  5848.2  365.81
#Mann=9,-1,0
  4412.8    0.12       0  4725.0    0.05       0  4993.6    0.16       0
  5004.2    0.07       0  5010.2    0.16       0  5210.8    0.12       0
  5340.6    0.16       0  5446.8    0.12       0  5560.9    0.05       0
Bank Sta=5004.2,5010.2
Exp/Cntr=0.3,0.1

Type RM Length L Ch R = 1,3615,453,453,453
BEGIN DESCRIPTION:
UNT 087 IN UKCR 6.0
END DESCRIPTION:
XS GIS Cut Line= 3
      3632199.56     10588210.20      3631699.61     10588310.19
      3631199.58     10588460.20
#Sta/Elev= 30
  4459.4  371.42  4479.7  368.07  4530.7  363.20  4661.4  344.80  4734.7  337.03
  4795.9  332.80  4887.7  329.58  4959.1  330.13  4980.4  328.23  4985.8  322.57
  4991.0  324.60  4997.6  321.56  5000.3  321.06  5003.6  321.56  5011.0  327.28
  5018.8  330.10  5024.1  327.72  5031.9  330.00  5084.1  330.25  5090.2  333.33
  5095.4  332.07  5167.6  340.00  5191.1  341.06  5199.8  341.18  5213.7  343.87
  5304.2  353.27  5332.1  357.47  5428.6  366.26  5449.5  370.48  5491.3  372.86
#Mann=7,-1,0
  4459.4    0.12       0  4661.4    0.05       0  4980.4    0.16       0
  4997.6    0.07       0  5003.6    0.16       0  5191.1    0.12       0
  5213.7    0.16       0
Bank Sta=4997.6,5003.6
Exp/Cntr=0.3,0.1

Type RM Length L Ch R = 1,3162,485,485,485
BEGIN DESCRIPTION:
UNT 087 IN UKCR 5.0
END DESCRIPTION:
XS GIS Cut Line= 3
      3632249.60     10588010.19      3631599.61     10587910.19
      3631099.64     10588010.18
#Sta/Elev= 30
  4345.9  376.95  4475.9  365.03  4504.4  361.52  4528.0  357.82  4558.4  355.66
  4608.9  346.18  4629.2  343.35  4706.3  334.86  4740.5  332.03  4831.5  327.60
  4942.8  326.31  4963.1  326.95  4983.3  323.98  4990.4  320.22  4993.2  319.72
  4996.4  320.22  5006.1  320.82  5013.7  327.54  5074.9  325.84  5095.3  326.26
  5176.9  329.62  5187.1  331.09  5227.9  333.37  5238.1  335.27  5329.9  343.55
  5391.1  351.96  5421.7  357.30  5472.6  362.84  5493.0  367.09  5513.4  368.70
#Mann=5,-1,0
  4345.9    0.05       0  4475.9    0.12       0  4504.4    0.05       0
  4990.4    0.03       0  4996.4    0.05       0
Bank Sta=4990.4,4996.4
Exp/Cntr=0.3,0.1

Type RM Length L Ch R = 1,2677,356,356,356
BEGIN DESCRIPTION:
UNT 087 IN UKCR 4.0
END DESCRIPTION:
XS GIS Cut Line= 4
      3631839.32     10587303.61      3631416.03     10587427.23
      3631299.61     10587610.19      3631049.63     10587960.16
#Sta/Elev= 30
  4335.4  365.17  4387.2  359.25  4460.1  359.08  4479.7  355.20  4484.9  351.52
  4491.4  350.00  4595.7  341.51  4637.2  339.85  4668.5  334.54  4696.1  333.17
  4741.4  327.87  4803.6  323.41  4871.7  323.70  4979.7  325.14  4985.6  324.76
  4990.3  321.86  4996.3  321.86  4997.6  319.94  5000.3  319.44  5003.6  319.94
  5006.7  322.54  5015.3  324.52  5047.9  323.56  5079.2  325.13  5202.1  338.74
  5243.9  344.37  5258.7  348.05  5288.2  349.95  5300.4  353.13  5423.3  366.59
#Mann=5,-1,0
  4335.4    0.05       0  4871.7    0.16       0  4997.6    0.07       0
  5003.6    0.16       0  5047.9    0.05       0
Bank Sta=4997.6,5003.6
Exp/Cntr=0.3,0.1

Type RM Length L Ch R = 1,2321,135,135,135
BEGIN DESCRIPTION:
UNT 087 IN UKCR 3.0
END DESCRIPTION:
XS GIS Cut Line= 4
      3631680.86     10587264.55      3631257.73     10587294.93
      3630977.78     10587316.63      3630826.05     10587795.66
#Sta/Elev= 30
  4485.2  357.52  4536.6  358.12  4558.9  354.32  4586.7  349.99  4643.4  344.87
  4717.0  338.31  4787.2  329.90  4827.3  328.69  4857.4  324.00  4917.7  321.93
  4977.7  322.82  4994.8  319.34  4997.6  318.84  5000.8  319.34  5007.8  322.39
  5017.9  323.48  5068.0  321.93  5158.3  321.27  5172.4  320.38  5194.7  321.19
  5214.9  323.16  5296.8  325.16  5424.7  333.38  5463.5  337.10  5468.8  338.34
  5500.0  340.14  5508.6  341.24  5540.1  342.39  5598.0  347.73  5692.7  351.12
#Mann=6,-1,0
  4485.2    0.05       0  4558.9    0.16       0  4643.4    0.05       0
  4994.8    0.03       0  5000.8    0.05       0  5500.0    0.16       0
Bank Sta=4994.8,5000.8
Exp/Cntr=0.3,0.1

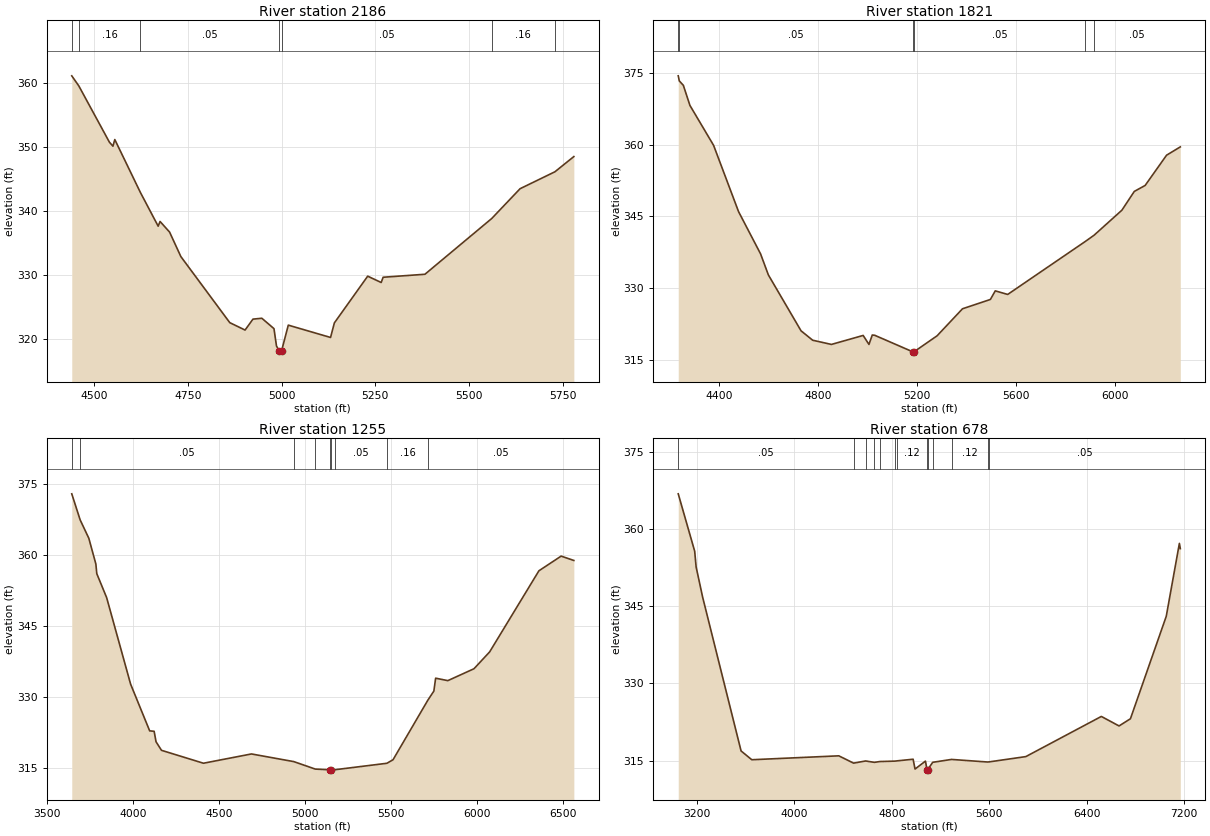
Type RM Length L Ch R = 1,2186,365,365,365
BEGIN DESCRIPTION:
Mapping XS 705764c9
END DESCRIPTION:
XS GIS Cut Line= 5
      3631639.64     10587214.63      3631194.79     10587177.74
      3631042.88     10587225.48      3630890.97     10587253.70
      3630749.99     10587815.46
#Sta/Elev= 30
  4440.3  361.16  4459.1  359.58  4540.7  350.77  4550.1  350.14  4555.1  351.18
  4623.3  342.90  4670.8  337.61  4675.8  338.35  4701.2  336.69  4731.3  332.85
  4861.8  322.50  4902.6  321.34  4923.6  323.05  4947.3  323.19  4979.7  321.56
  4986.4  318.84  4993.9  318.07  4996.7  317.57  4999.9  318.07  5017.9  322.11
  5130.6  320.18  5140.8  322.46  5229.7  329.78  5265.7  328.79  5270.9  329.61
  5382.4  330.08  5560.7  338.82  5636.2  343.48  5729.1  346.13  5779.6  348.51
#Mann=7,-1,0
  4440.3    0.05       0  4459.1    0.16       0  4623.3    0.05       0
  4993.9    0.03       0  4999.9    0.05       0  5560.7    0.16       0
  5729.1    0.05       0
Bank Sta=4993.9,4999.9
Exp/Cntr=0.3,0.1

Type RM Length L Ch R = 1,1821,566,566,566
BEGIN DESCRIPTION:
UNT 087 IN UKCR 2.0
END DESCRIPTION:
XS GIS Cut Line= 4
      3631676.38     10586920.89      3631214.74     10586770.47
      3630794.63     10586952.00      3630690.94     10588035.56
#Sta/Elev= 30
  4234.0  374.41  4238.3  373.35  4254.7  372.42  4281.3  368.22  4377.1  359.86
  4478.1  345.99  4567.2  337.15  4598.7  332.75  4731.0  321.05  4778.0  319.08
  4853.9  318.20  4982.3  320.08  5005.8  318.20  5019.2  320.17  5029.3  320.11
  5182.4  316.67  5185.2  316.17  5188.4  316.67  5281.6  320.01  5384.3  325.66
  5497.1  327.61  5516.9  329.41  5567.2  328.66  5881.0  339.74  5916.9  341.06
  6029.3  346.29  6079.5  350.22  6123.4  351.47  6210.1  357.80  6265.7  359.54
#Mann=6,-1,0
  4234.0    0.16       0  4238.3    0.05       0  5182.4    0.03       0
  5188.4    0.05       0  5881.0    0.16       0  5916.9    0.05       0
Bank Sta=5182.4,5188.4
Exp/Cntr=0.3,0.1

Type RM Length L Ch R = 1,1255,577,577,577
BEGIN DESCRIPTION:
Mapping XS 1b5e50f6
END DESCRIPTION:
XS GIS Cut Line= 4
      3631733.36     10586811.95      3630794.63     10586490.39
      3630400.45     10586874.20      3630628.65     10588233.02
#Sta/Elev= 30
  3645.2  372.88  3694.0  367.37  3744.3  363.50  3785.4  358.05  3790.7  356.02
  3848.0  350.96  3987.4  332.68  4098.3  322.80  4124.3  322.71  4135.4  320.49
  4167.1  318.69  4411.1  315.96  4690.3  317.92  4936.8  316.30  5061.9  314.72
  5147.0  314.58  5149.7  314.08  5153.0  314.58  5174.4  314.58  5478.2  315.95
  5513.9  316.70  5716.8  329.31  5751.3  331.20  5761.6  333.93  5832.5  333.41
  5984.6  335.92  6075.9  339.49  6362.4  356.62  6491.6  359.72  6565.5  358.80
#Mann=9,-1,0
  3645.2    0.16       0  3694.0    0.05       0  4936.8    0.16       0
  5061.9    0.12       0  5147.0    0.07       0  5153.0    0.12       0
  5174.4    0.05       0  5478.2    0.16       0  5716.8    0.05       0
Bank Sta=5147,5153
Exp/Cntr=0.3,0.1

Type RM Length L Ch R = 1,678,0,0,0
BEGIN DESCRIPTION:
UNT 087 IN UKCR 1.0
END DESCRIPTION:
XS GIS Cut Line= 5
      3631883.83     10586651.19      3631157.68     10586339.99
      3630410.82     10586334.80      3629897.36     10586640.80
      3629363.15     10588554.61
#Sta/Elev= 30
  3046.1  366.86  3181.2  355.70  3192.9  352.65  3246.5  346.76  3562.0  316.86
  3649.9  315.15  4364.2  315.91  4485.6  314.49  4584.8  314.91  4655.9  314.64
  4702.7  314.80  4824.3  314.88  4842.4  314.93  4974.4  315.25  4990.0  313.34
  5075.6  314.88  5088.2  313.24  5091.0  312.74  5094.2  313.24  5135.1  314.65
  5289.6  315.21  5584.9  314.71  5597.9  314.73  5899.7  315.76  6519.4  323.57
  6664.8  321.72  6758.3  323.12  7052.4  343.05  7160.1  357.22  7167.7  356.20
#Mann=13,-1,0
  3046.1    0.05       0  4485.6    0.16       0  4584.8    0.12       0
  4655.9    0.16       0  4702.7    0.12       0  4824.3    0.16       0
  4842.4    0.12       0  5088.2    0.07       0  5094.2    0.12       0
  5135.1    0.16       0  5289.6    0.12       0  5584.9    0.07       0
  5597.9    0.05       0
Bank Sta=5088.2,5094.2
Exp/Cntr=0.3,0.1

Chan Stop Cuts=-1