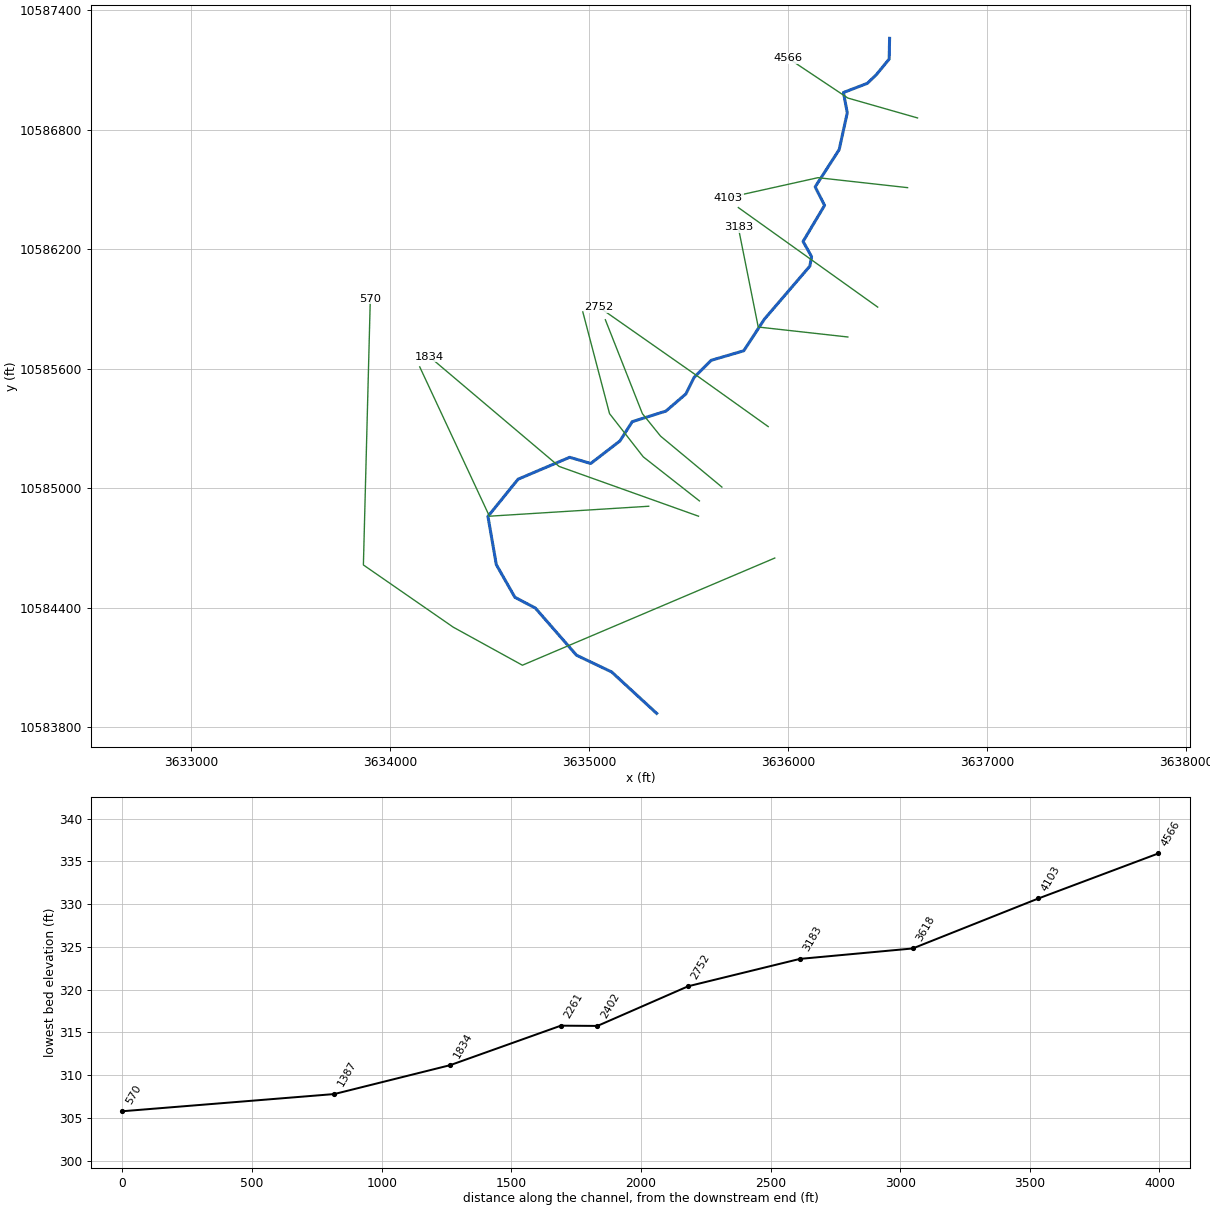
--- UNT 090 IN UKCR.prj (project) ---

Proj Title=UNT 090 IN UKCR Base Level Engineering
Current Plan=p01
Default Exp/Contr=0.3,0.1
English Units
Geom File=g01
Flow File=f01
Plan File=p01
BEGIN DESCRIPTION:
UNT 090 IN UKCR
END DESCRIPTION:

--- UNT 090 IN UKCR.p01 (plan) ---

Plan Title=Multiple Run
Short Identifier=Multiple
Geom File=g01
Flow File=f01
Subcritical Flow
K Sum by GR= 0
Std Step Tol= 0.01
Critical Tol= 0.01
Num of Std Step Trials= 20
Max Error Tol= 0.3
Flow Tol Ratio= 0.001
Split Flow NTrial= 30
Split Flow Tol= 0.02
Split Flow Ratio= 0.02
Log Output Level= 0
Friction Slope Method= 1
Unsteady Friction Slope Method= 2
Unsteady Bridges Friction Slope Method= 1
Parabolic Critical Depth
Global Vel Dist=  1 , 1 , 1
Global Log Level= 0
CheckData=True
Encroach Param= -1, 0, 0, 0
BEGIN DESCRIPTION:
Multiple Run
END DESCRIPTION:

--- UNT 090 IN UKCR.f01 (steady flow) ---

Flow Title=Multiple
Number of Profiles=7
Profile Names=10-year,25-year,50-year,1pct_min,100-year,1pct_plu,500-year
River Rch & RM= UNT 090 IN UKCR,Reach-1,4566
    1703    2427    3048    2793    3777    5108    5780
Boundary for River Rch & Prof#=UNT 090 IN UKCR,Reach-1,1
Up Type=0
Dn Type=3
Dn Slope=0.005
Boundary for River Rch & Prof#=UNT 090 IN UKCR,Reach-1,2
Up Type=0
Dn Type=3
Dn Slope=0.005
Boundary for River Rch & Prof#=UNT 090 IN UKCR,Reach-1,3
Up Type=0
Dn Type=3
Dn Slope=0.005
Boundary for River Rch & Prof#=UNT 090 IN UKCR,Reach-1,4
Up Type=0
Dn Type=3
Dn Slope=0.005
Boundary for River Rch & Prof#=UNT 090 IN UKCR,Reach-1,5
Up Type=0
Dn Type=3
Dn Slope=0.005
Boundary for River Rch & Prof#=UNT 090 IN UKCR,Reach-1,6
Up Type=0
Dn Type=3
Dn Slope=0.005
Boundary for River Rch & Prof#=UNT 090 IN UKCR,Reach-1,7
Up Type=0
Dn Type=3
Dn Slope=0.005

--- UNT 090 IN UKCR.g01 (geometry) ---

Geom Title=Existing Conditions

River Reach=UNT 090 IN UKCR,Reach-1
Reach XY= 30
      3636509.25     10587260.00      3636507.25     10587156.00
      3636444.00     10587079.00      3636397.50     10587034.00
      3636277.50     10586988.00      3636296.75     10586886.00
      3636256.00     10586701.00      3636135.50     10586514.00
      3636182.75     10586421.00      3636074.75     10586240.00
      3636117.50     10586164.00      3636108.75     10586116.00
      3635880.75     10585850.00      3635777.00     10585691.00
      3635613.25     10585643.00      3635527.25     10585557.00
      3635486.00     10585474.00      3635386.00     10585388.00
      3635217.00     10585335.00      3635155.00     10585238.00
      3635008.50     10585125.00      3634902.75     10585156.00
      3634643.50     10585046.00      3634492.25     10584859.00
      3634534.25     10584617.00      3634627.50     10584453.00
      3634730.25     10584399.00      3634937.00     10584162.00
      3635113.50     10584078.00      3635339.50     10583870.00

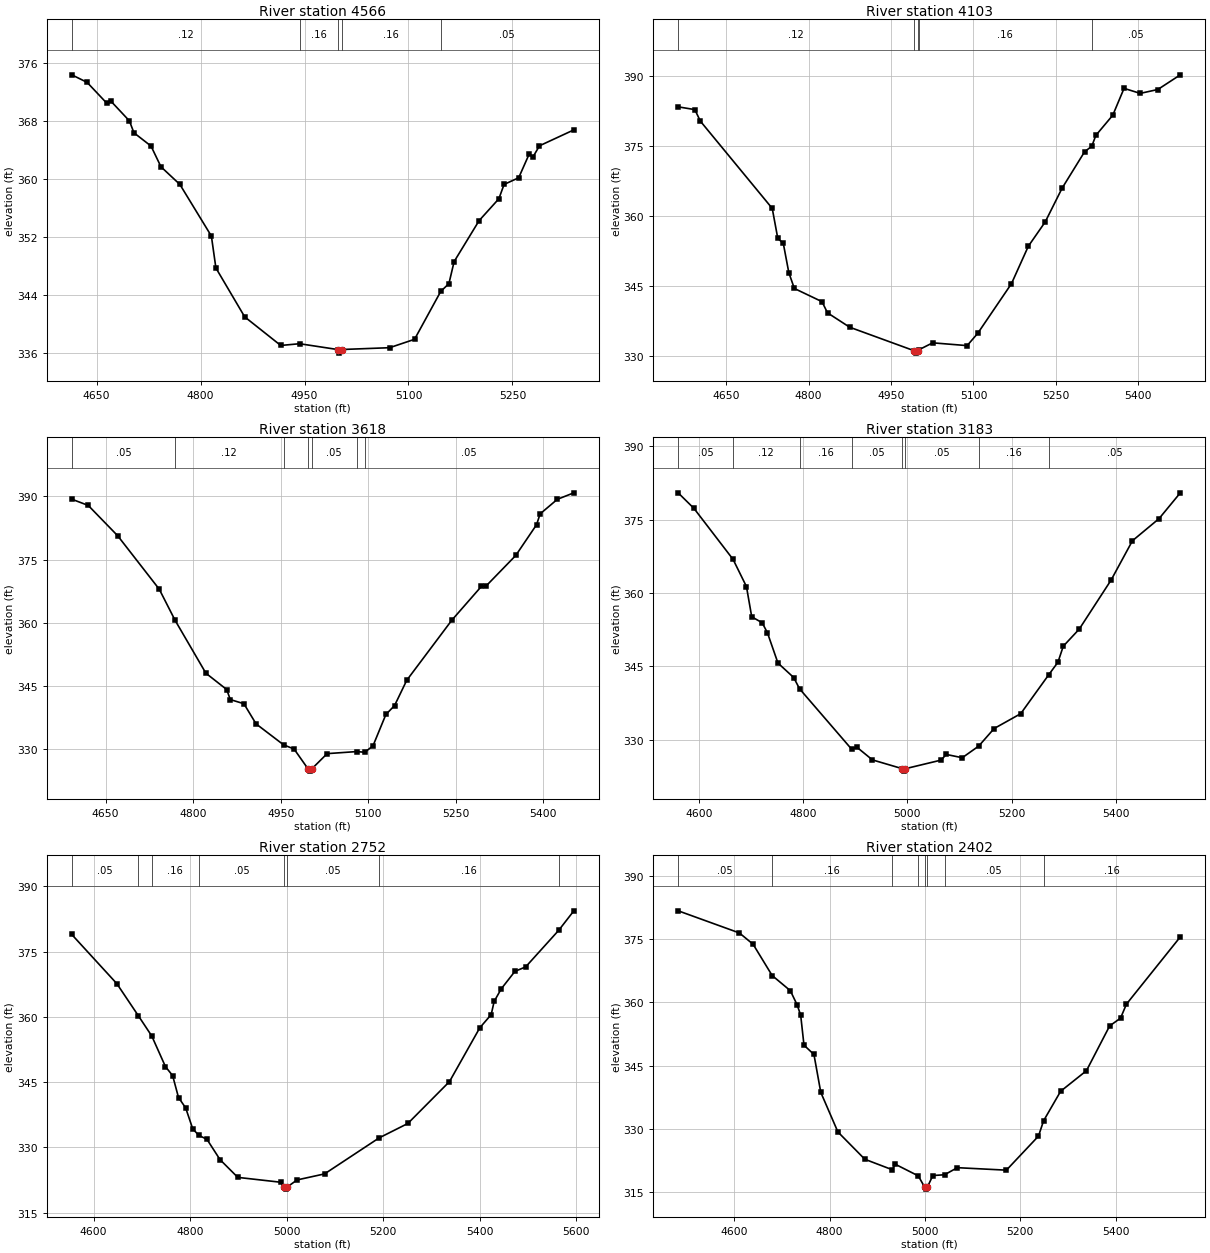
Type RM Length L Ch R = 1,4566,463,463,463
BEGIN DESCRIPTION:
UNT 090 IN UKCR 9.0
END DESCRIPTION:
XS GIS Cut Line= 3
      3636649.64     10586860.18      3636299.61     10586960.19
      3635999.61     10587160.19
#Sta/Elev= 30
  4614.1  374.40  4636.2  373.36  4664.8  370.46  4670.0  370.82  4697.3  368.03
  4703.8  366.39  4728.5  364.55  4742.8  361.69  4770.1  359.25  4815.6  352.11
  4822.1  347.70  4863.7  340.94  4915.7  336.99  4942.9  337.23  4997.7  336.43
  5000.4  335.93  5003.7  336.43  5072.8  336.68  5108.8  337.84  5146.6  344.46
  5158.4  345.54  5165.9  348.58  5202.0  354.25  5230.5  357.27  5238.0  359.25
  5259.1  360.17  5274.1  363.42  5280.1  363.11  5289.1  364.59  5338.7  366.79
#Mann=5,-1,0
  4614.1    0.12       0  4942.9    0.16       0  4997.7    0.07       0
  5003.7    0.16       0  5146.6    0.05       0
Bank Sta=4997.7,5003.7
Exp/Cntr=0.3,0.1

Type RM Length L Ch R = 1,4103,485,485,485
BEGIN DESCRIPTION:
UNT 090 IN UKCR 8.0
END DESCRIPTION:
XS GIS Cut Line= 3
      3636599.66     10586510.18      3636149.61     10586560.19
      3635699.61     10586460.19
#Sta/Elev= 30
  4562.7  383.48  4592.9  382.89  4603.0  380.41  4733.8  361.70  4743.9  355.26
  4753.9  354.21  4764.0  347.91  4774.0  344.53  4824.3  341.70  4834.4  339.30
  4874.7  336.22  4992.4  331.16  4995.1  330.66  4998.4  331.16  5000.2  331.35
  5025.8  332.87  5088.5  332.27  5107.7  334.89  5169.2  345.56  5199.9  353.59
  5230.6  358.80  5261.4  366.05  5302.3  373.85  5315.4  375.04  5322.8  377.37
  5353.6  381.69  5374.1  387.45  5403.5  386.37  5435.5  387.20  5476.5  390.35
#Mann=5,-1,0
  4562.7    0.12       0  4992.4    0.07       0  4998.4    0.12       0
  5000.2    0.16       0  5315.4    0.05       0
Bank Sta=4992.4,4998.4
Exp/Cntr=0.3,0.1

Type RM Length L Ch R = 1,3618,435,435,435
BEGIN DESCRIPTION:
UNT 090 IN UKCR 7.0
END DESCRIPTION:
XS GIS Cut Line= 3
      3636449.58     10585910.21      3636099.61     10586160.19
      3635749.61     10586410.19
#Sta/Elev= 30
  4591.9  389.35  4620.1  387.87  4670.5  380.68  4741.8  367.98  4769.0  360.58
  4821.7  348.05  4857.3  344.18  4863.5  341.79  4886.8  340.81  4907.7  336.02
  4954.8  331.05  4972.8  330.05  4996.9  325.31  4999.6  324.81  5002.9  325.31
  5029.4  328.96  5079.9  329.45  5093.9  329.29  5108.0  330.82  5130.1  338.26
  5144.9  340.36  5165.8  346.37  5243.2  360.66  5293.6  368.64  5302.2  368.81
  5352.6  376.00  5388.2  383.29  5394.3  385.86  5423.8  389.32  5452.1  390.86
#Mann=7,-1,0
  4591.9    0.05       0  4769.0    0.12       0  4954.8    0.05       0
  4996.9   0.033       0  5002.9    0.05       0  5079.9    0.16       0
  5093.9    0.05       0
Bank Sta=4996.9,5002.9
Exp/Cntr=0.3,0.1

Type RM Length L Ch R = 1,3183,431,431,431
BEGIN DESCRIPTION:
UNT 090 IN UKCR 6.0
END DESCRIPTION:
XS GIS Cut Line= 3
      3636299.61     10585760.19      3635849.61     10585810.19
      3635749.60     10586310.21
#Sta/Elev= 30
  4560.6  380.48  4590.8  377.31  4665.8  366.88  4691.4  361.33  4701.5  355.16
  4721.6  353.92  4731.6  351.89  4751.8  345.69  4782.0  342.73  4793.2  340.43
  4893.1  328.07  4902.7  328.52  4932.9  325.89  4990.2  324.09  4993.0  323.59
  4996.2  324.09  5064.4  325.84  5074.6  327.00  5105.2  326.33  5136.6  328.70
  5166.3  332.30  5217.3  335.34  5270.7  343.25  5288.7  345.87  5298.9  349.14
  5329.5  352.63  5390.7  362.68  5431.5  370.70  5482.5  375.22  5523.3  380.50
#Mann=8,-1,0
  4560.6    0.05       0  4665.8    0.12       0  4793.2    0.16       0
  4893.1    0.05       0  4990.2   0.033       0  4996.2    0.05       0
  5136.6    0.16       0  5270.7    0.05       0
Bank Sta=4990.2,4996.2
Exp/Cntr=0.3,0.1

Type RM Length L Ch R = 1,2752,350,350,350
BEGIN DESCRIPTION:
UNT 090 IN UKCR 5.0
END DESCRIPTION:
XS GIS Cut Line= 3
      3635899.64     10585310.17      3635549.61     10585560.19
      3635049.59     10585910.20
#Sta/Elev= 30
  4554.8  378.91  4648.2  367.61  4693.0  360.20  4720.6  355.58  4749.0  348.53
  4763.8  346.49  4776.0  341.44  4790.8  339.07  4805.5  334.24  4818.1  332.75
  4835.0  331.83  4862.1  327.16  4898.9  323.09  4988.0  321.97  4995.5  320.89
  4998.2  320.39  5001.5  320.89  5021.6  322.50  5078.7  323.89  5191.7  332.16
  5251.3  335.48  5337.6  345.11  5400.4  357.47  5424.0  360.50  5430.1  363.52
  5444.9  366.43  5473.2  370.44  5495.4  371.46  5564.0  379.88  5595.3  384.35
#Mann=8,-1,0
  4554.8    0.05       0  4693.0    0.12       0  4720.6    0.16       0
  4818.1    0.05       0  4995.5   0.033       0  5001.5    0.05       0
  5191.7    0.16       0  5564.0    0.05       0
Bank Sta=4995.5,5001.5
Exp/Cntr=0.3,0.1

Type RM Length L Ch R = 1,2402,141,141,141
BEGIN DESCRIPTION:
Mapping XS 1c7421b3
END DESCRIPTION:
XS GIS Cut Line= 4
      3635667.06     10585006.43      3635358.93     10585262.48
      3635267.78     10585375.33      3635081.80     10585846.77
#Sta/Elev= 30
  4482.8  381.65  4611.0  376.41  4639.7  373.74  4679.7  366.33  4717.8  362.74
  4732.1  359.37  4739.5  356.92  4746.4  349.84  4767.3  347.63  4781.6  338.67
  4817.5  329.29  4874.0  322.82  4931.1  320.36  4938.2  321.62  4986.0  318.89
  4999.2  316.25  5001.9  315.75  5005.2  316.25  5016.5  318.97  5041.0  319.15
  5067.9  320.83  5170.7  320.24  5238.0  328.31  5248.7  331.94  5284.4  338.92
  5338.5  343.79  5387.2  354.40  5410.0  356.24  5422.4  359.56  5535.3  375.48
#Mann=8,-1,0
  4482.8    0.05       0  4679.7    0.16       0  4931.1    0.05       0
  4986.0    0.16       0  4999.2    0.07       0  5005.2    0.16       0
  5041.0    0.05       0  5248.7    0.16       0
Bank Sta=4999.2,5005.2
Exp/Cntr=0.3,0.1

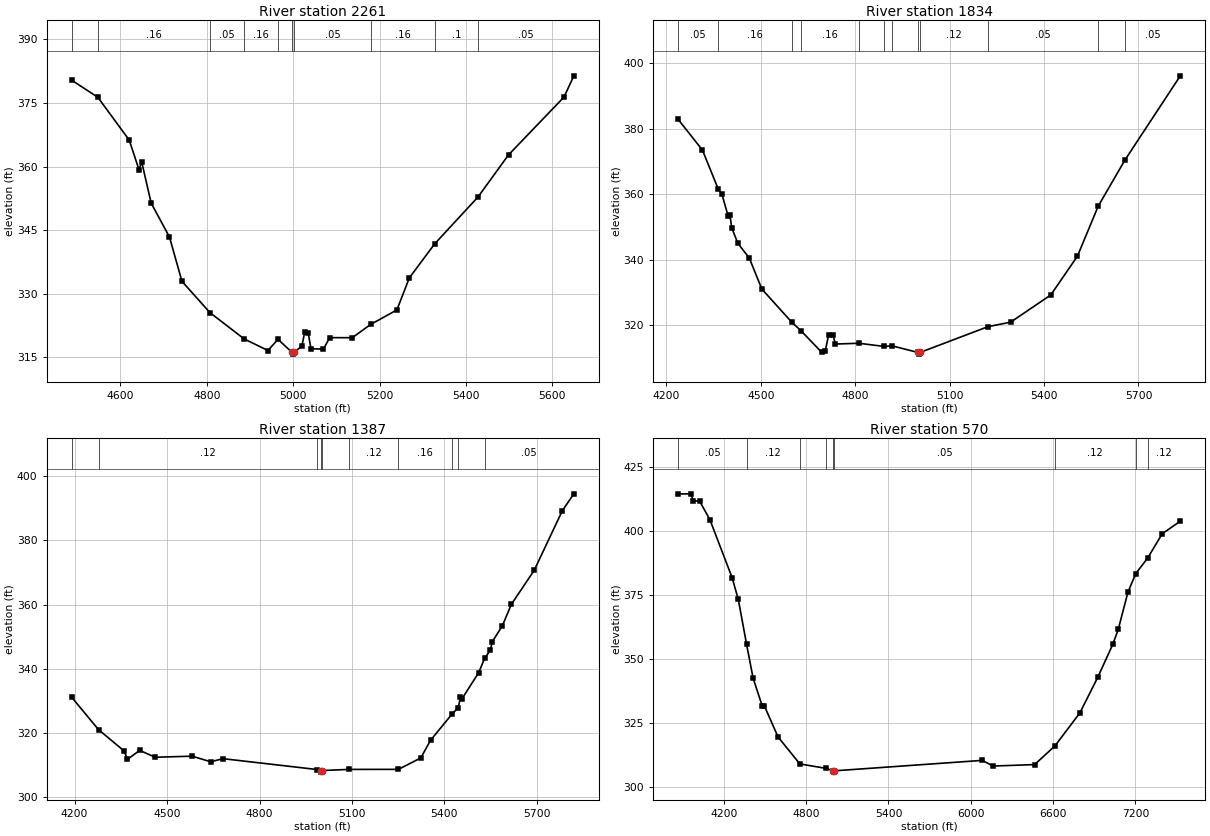
Type RM Length L Ch R = 1,2261,427,427,427
BEGIN DESCRIPTION:
UNT 090 IN UKCR 4.0
END DESCRIPTION:
XS GIS Cut Line= 4
      3635554.21     10584936.99      3635272.12     10585158.31
      3635102.85     10585375.33      3634968.61     10585886.32
#Sta/Elev= 30
  4487.5  380.38  4547.9  376.35  4620.5  366.26  4643.0  359.31  4649.4  361.10
  4671.3  351.38  4713.6  343.42  4742.5  332.95  4807.3  325.57  4886.4  319.37
  4941.6  316.63  4964.8  319.26  4996.4  316.28  4999.2  315.78  5002.4  316.28
  5020.2  317.66  5026.6  320.99  5034.7  320.81  5041.1  317.05  5070.0  316.96
  5084.5  319.67  5136.6  319.65  5179.6  322.80  5240.0  326.20  5268.8  333.76
  5327.5  341.79  5427.9  352.86  5498.5  362.79  5626.9  376.42  5649.6  381.42
#Mann=10,-1,0
  4487.5    0.05       0  4547.9    0.16       0  4807.3    0.05       0
  4886.4    0.16       0  4964.8    0.05       0  4996.4    0.03       0
  5002.4    0.05       0  5179.6    0.16       0  5327.5     0.1       0
  5427.9    0.05       0
Bank Sta=4996.4,5002.4
Exp/Cntr=0.3,0.1

Type RM Length L Ch R = 1,1834,447,447,447
BEGIN DESCRIPTION:
UNT 090 IN UKCR 3.0
END DESCRIPTION:
XS GIS Cut Line= 3
      3635549.60     10584860.19      3634849.61     10585110.19
      3634199.58     10585660.21
#Sta/Elev= 30
  4238.1  382.86  4315.1  373.48  4365.5  361.50  4376.7  360.09  4396.8  353.26
  4402.2  353.74  4408.0  349.77  4427.6  344.98  4463.7  340.54  4503.6  331.05
  4599.1  320.87  4628.4  318.27  4694.2  311.69  4705.3  312.24  4715.9  317.08
  4730.3  316.88  4737.2  314.24  4812.1  314.48  4891.3  313.52  4918.6  313.66
  4999.8  311.66  5002.6  311.16  5005.8  311.66  5221.9  319.55  5294.0  320.93
  5421.4  329.23  5506.0  341.07  5572.3  356.40  5657.4  370.52  5832.9  396.19
#Mann=12,-1,0
  4238.1    0.05       0  4365.5    0.16       0  4599.1    0.12       0
  4628.4    0.16       0  4812.1    0.12       0  4891.3    0.05       0
  4918.6    0.12       0  4999.8    0.07       0  5005.8    0.12       0
  5221.9    0.05       0  5572.3    0.12       0  5657.4    0.05       0
Bank Sta=4999.8,5005.8
Exp/Cntr=0.3,0.1

Type RM Length L Ch R = 1,1387,817,817,817
BEGIN DESCRIPTION:
UNT 090 IN UKCR 2.0
END DESCRIPTION:
XS GIS Cut Line= 3
      3635299.58     10584910.19      3634499.61     10584860.19
      3634149.60     10585610.21
#Sta/Elev= 30
  4190.8  331.08  4277.9  320.99  4361.1  314.35  4371.1  311.73  4411.2  314.56
  4461.3  312.42  4581.5  312.75  4641.6  311.01  4681.7  311.97  4986.8  308.59
  4998.0  308.28  5000.8  307.78  5004.0  308.28  5091.2  308.63  5250.7  308.64
  5323.4  312.20  5354.9  317.69  5424.6  325.86  5444.9  327.87  5451.9  331.09
  5457.4  330.70  5511.0  338.75  5530.9  343.33  5548.8  345.69  5555.1  348.37
  5588.2  353.43  5617.4  360.09  5691.5  370.70  5782.9  389.30  5820.0  394.51
#Mann=10,-1,0
  4190.8    0.16       0  4277.9    0.12       0  4986.8    0.16       0
  4998.0    0.07       0  5004.0    0.16       0  5091.2    0.12       0
  5250.7    0.16       0  5424.6    0.12       0  5444.9    0.16       0
  5530.9    0.05       0
Bank Sta=4998,5004
Exp/Cntr=0.3,0.1

Type RM Length L Ch R = 1,570,0,0,0
BEGIN DESCRIPTION:
UNT 090 IN UKCR 1.0
END DESCRIPTION:
XS GIS Cut Line= 5
      3635932.67     10584650.05      3634665.35     10584111.87
      3634318.13     10584302.84      3633866.74     10584615.34
      3633901.46     10585952.16
#Sta/Elev= 30
  3867.8  414.47  3960.2  414.53  3978.5  411.71  4023.2  411.75  4099.3  404.33
  4260.4  381.78  4305.7  373.25  4365.9  355.74  4413.2  342.55  4479.5  331.70
  4495.0  331.74  4595.1  319.52  4754.5  308.97  4943.8  307.25  4997.7  306.27
  5000.5  305.77  5003.7  306.27  6083.7  310.36  6162.1  308.15  6464.9  308.71
  6613.4  316.01  6795.0  328.91  6925.0  342.77  7035.1  355.71  7075.1  361.59
  7145.1  376.05  7202.7  383.38  7289.1  389.43  7395.2  398.92  7527.2  403.84
#Mann=9,-1,0
  3867.8    0.05       0  4365.9    0.12       0  4754.5    0.07       0
  4943.8    0.05       0  4997.7   0.035       0  5003.7    0.05       0
  6613.4    0.12       0  7202.7    0.05       0  7289.1    0.12       0
Bank Sta=4997.7,5003.7
Exp/Cntr=0.3,0.1

Chan Stop Cuts=-1