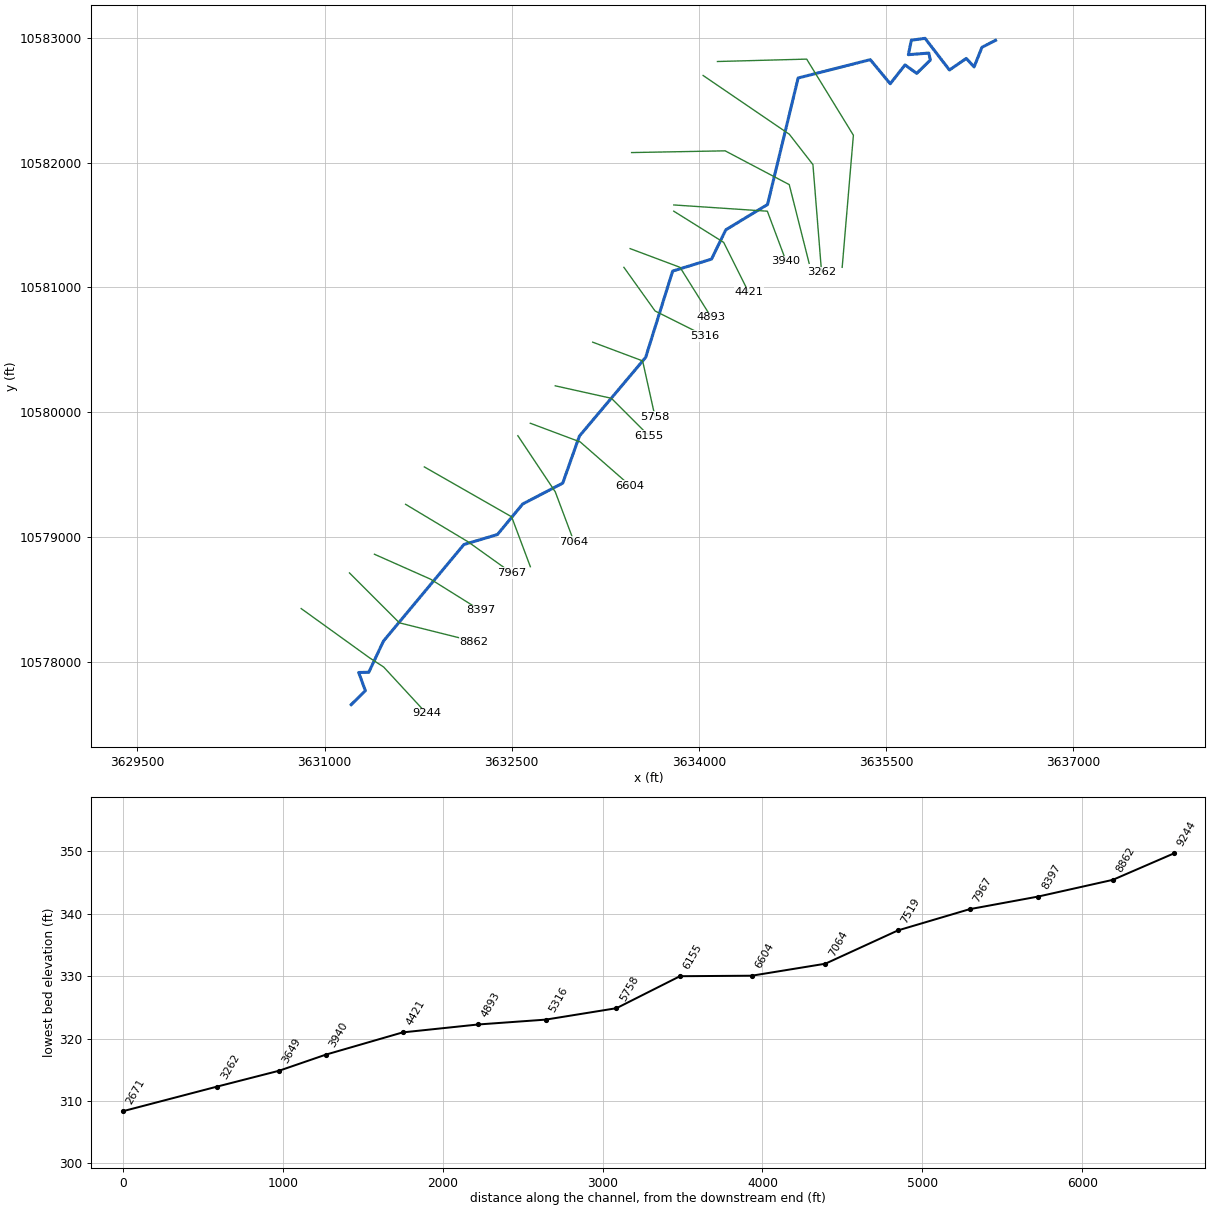
--- UNT 091 IN UKCR.prj (project) ---

Proj Title=UNT 091 IN UKCR Base Level Engineering
Current Plan=p01
Default Exp/Contr=0.3,0.1
English Units
Geom File=g01
Flow File=f01
Plan File=p01
BEGIN DESCRIPTION:
UNT 091 IN UKCR
END DESCRIPTION:

--- UNT 091 IN UKCR.p01 (plan) ---

Plan Title=Multiple Run
Short Identifier=Multiple
Geom File=g01
Flow File=f01
Subcritical Flow
K Sum by GR= 0
Std Step Tol= 0.01
Critical Tol= 0.01
Num of Std Step Trials= 20
Max Error Tol= 0.3
Flow Tol Ratio= 0.001
Split Flow NTrial= 30
Split Flow Tol= 0.02
Split Flow Ratio= 0.02
Log Output Level= 0
Friction Slope Method= 1
Unsteady Friction Slope Method= 2
Unsteady Bridges Friction Slope Method= 1
Parabolic Critical Depth
Global Vel Dist=  1 , 1 , 1
Global Log Level= 0
CheckData=True
Encroach Param= -1, 0, 0, 0
BEGIN DESCRIPTION:
Multiple Run
END DESCRIPTION:

--- UNT 091 IN UKCR.f01 (steady flow) ---

Flow Title=Multiple
Number of Profiles=7
Profile Names=10-year,25-year,50-year,1pct_min,100-year,1pct_plu,500-year
River Rch & RM= UNT 091 IN UKCR,Reach-1,9244
    1639    2313    2884    2622    3547    4796    5345
Boundary for River Rch & Prof#=UNT 091 IN UKCR,Reach-1,1
Up Type=0
Dn Type=3
Dn Slope=0.005
Boundary for River Rch & Prof#=UNT 091 IN UKCR,Reach-1,2
Up Type=0
Dn Type=3
Dn Slope=0.005
Boundary for River Rch & Prof#=UNT 091 IN UKCR,Reach-1,3
Up Type=0
Dn Type=3
Dn Slope=0.005
Boundary for River Rch & Prof#=UNT 091 IN UKCR,Reach-1,4
Up Type=0
Dn Type=3
Dn Slope=0.005
Boundary for River Rch & Prof#=UNT 091 IN UKCR,Reach-1,5
Up Type=0
Dn Type=3
Dn Slope=0.005
Boundary for River Rch & Prof#=UNT 091 IN UKCR,Reach-1,6
Up Type=0
Dn Type=3
Dn Slope=0.005
Boundary for River Rch & Prof#=UNT 091 IN UKCR,Reach-1,7
Up Type=0
Dn Type=3
Dn Slope=0.005

--- UNT 091 IN UKCR.g01 (geometry) ---

Geom Title=Existing Conditions

River Reach=UNT 091 IN UKCR,Reach-1
Reach XY= 30
      3631213.00     10577654.00      3631327.00     10577766.00
      3631273.50     10577912.00      3631354.50     10577914.00
      3631472.25     10578164.00      3632117.00     10578938.00
      3632385.75     10579018.00      3632588.50     10579263.00
      3632909.25     10579430.00      3633042.75     10579807.00
      3633574.00     10580438.00      3633790.50     10581130.00
      3634102.00     10581226.00      3634216.75     10581461.00
      3634551.25     10581664.00      3634796.50     10582678.00
      3635374.75     10582825.00      3635534.75     10582632.00
      3635653.50     10582783.00      3635747.25     10582715.00
      3635856.50     10582822.00      3635844.00     10582878.00
      3635680.25     10582865.00      3635704.25     10582981.00
      3635814.00     10582996.00      3636009.50     10582742.00
      3636144.25     10582835.00      3636207.25     10582767.00
      3636270.00     10582924.00      3636379.00     10582980.00

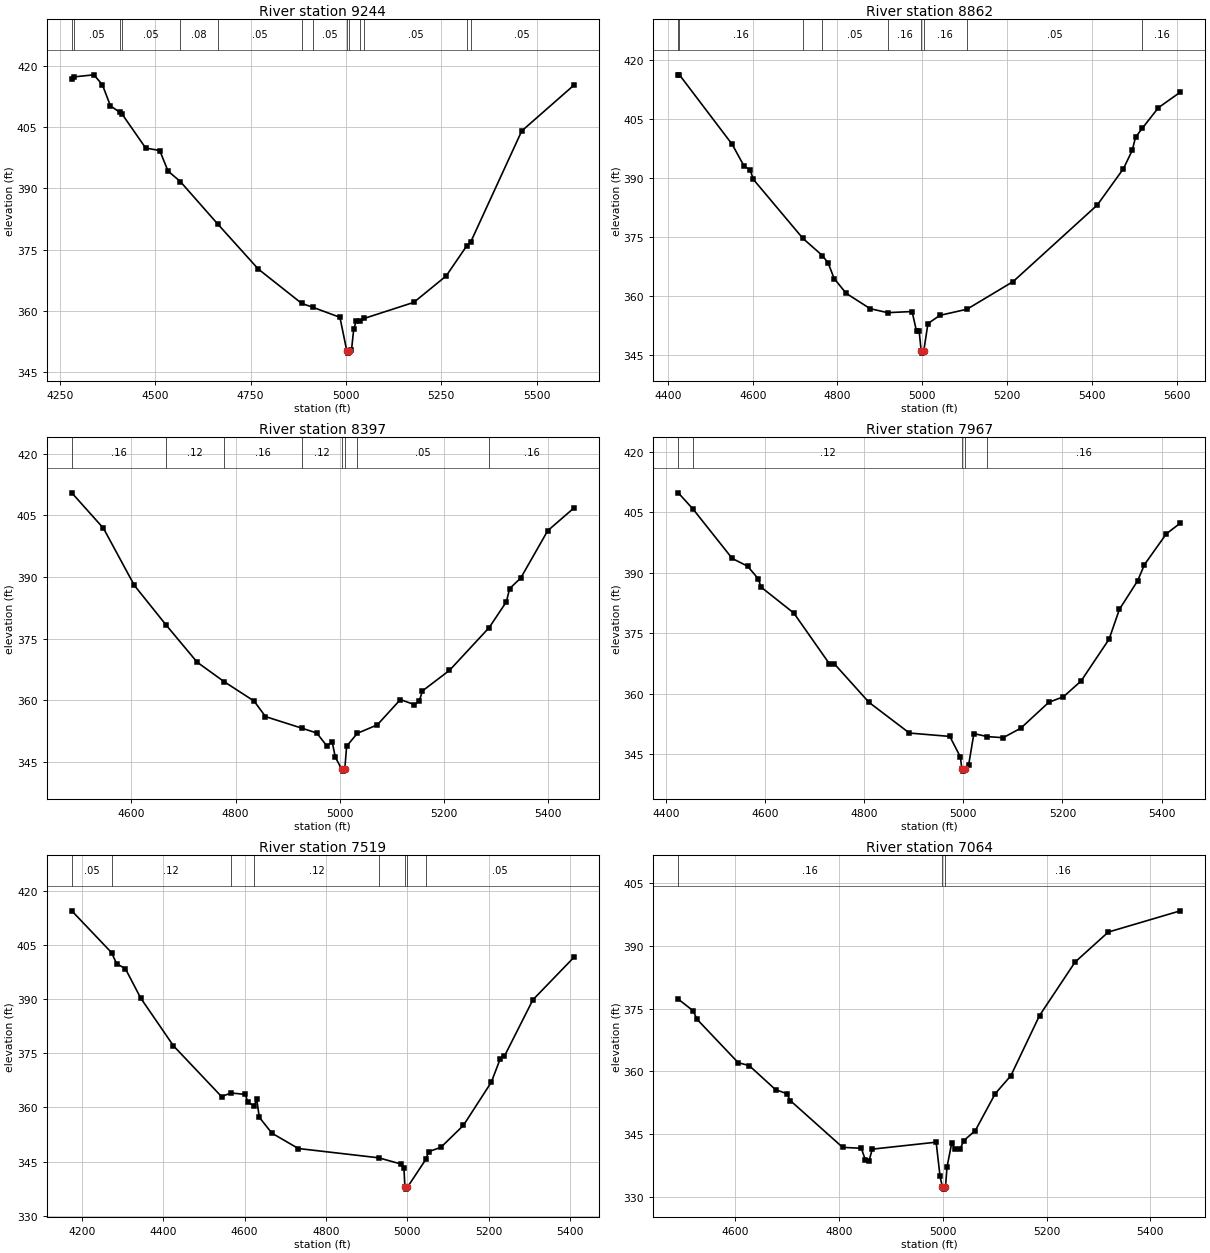
Type RM Length L Ch R = 1,9244,382,382,382
BEGIN DESCRIPTION:
UNT 091 IN UKCR 14.0
END DESCRIPTION:
XS GIS Cut Line= 4
      3630812.41     10578424.49      3631361.90     10578028.65
      3631473.88     10577955.73      3631816.78     10577584.25
#Sta/Elev= 30
  4281.3  416.81  4287.2  417.32  4339.5  417.82  4361.8  415.34  4382.7  410.22
  4406.6  408.69  4412.7  408.28  4475.0  399.90  4512.0  399.28  4533.6  394.27
  4565.8  391.70  4663.5  381.34  4770.5  370.25  4884.1  361.86  4914.3  360.87
  4984.4  358.45  5002.5  350.18  5005.3  349.68  5008.5  350.18  5014.7  350.41
  5020.6  355.60  5027.4  357.58  5037.0  357.45  5048.8  358.20  5178.1  362.11
  5263.0  368.58  5316.9  375.95  5327.3  376.89  5461.1  404.08  5597.7  415.27
#Mann=14,-1,0
  4281.3    0.16       0  4287.2    0.05       0  4406.6     0.1       0
  4412.7    0.05       0  4565.8    0.08       0  4663.5    0.05       0
  4884.1    0.08       0  4914.3    0.05       0  5002.5    0.04       0
  5008.5    0.05       0  5037.0    0.16       0  5048.8    0.05       0
  5316.9    0.16       0  5327.3    0.05       0
Bank Sta=5002.5,5008.5
Exp/Cntr=0.3,0.1

Type RM Length L Ch R = 1,8862,465,465,465
BEGIN DESCRIPTION:
UNT 091 IN UKCR 13.0
END DESCRIPTION:
XS GIS Cut Line= 3
      3631199.61     10578710.18      3631599.61     10578310.19
      3632199.57     10578160.20
#Sta/Elev= 30
  4424.4  416.28  4427.2  416.28  4551.7  398.57  4580.0  392.98  4594.1  392.10
  4601.2  389.71  4718.3  374.66  4764.2  370.29  4777.9  368.40  4792.1  364.43
  4820.4  360.67  4876.9  356.76  4918.2  355.74  4975.9  356.03  4986.5  350.95
  4992.7  350.95  4997.4  345.94  5000.1  345.44  5003.4  345.94  5013.3  352.97
  5041.6  355.06  5105.3  356.61  5214.3  363.66  5412.7  383.14  5474.5  392.41
  5495.2  397.08  5502.9  400.39  5519.2  402.73  5557.0  407.93  5608.5  411.87
#Mann=9,-1,0
  4424.4    0.08       0  4427.2    0.16       0  4718.3    0.12       0
  4764.2    0.05       0  4918.2    0.16       0  4997.4    0.07       0
  5003.4    0.16       0  5105.3    0.05       0  5519.2    0.16       0
Bank Sta=4997.4,5003.4
Exp/Cntr=0.3,0.1

Type RM Length L Ch R = 1,8397,430,430,430
BEGIN DESCRIPTION:
UNT 091 IN UKCR 12.0
END DESCRIPTION:
XS GIS Cut Line= 3
      3631399.65     10578860.17      3631849.61     10578660.19
      3632249.61     10578410.19
#Sta/Elev= 30
  4485.6  410.50  4546.4  401.88  4605.9  387.95  4666.8  378.32  4726.3  369.29
  4778.4  364.52  4835.7  359.82  4857.6  356.04  4928.5  353.18  4956.1  352.04
  4975.3  348.91  4985.7  349.88  4991.6  346.17  5003.9  343.27  5006.6  342.77
  5009.9  343.27  5013.4  348.83  5033.9  351.97  5072.3  354.03  5116.6  360.18
  5143.7  358.95  5153.1  359.91  5159.0  362.30  5210.9  367.29  5287.2  377.72
  5320.0  383.95  5326.5  387.21  5347.7  389.76  5399.6  401.29  5449.7  406.79
#Mann=8,-1,0
  4485.6    0.16       0  4666.8    0.12       0  4778.4    0.16       0
  4928.5    0.12       0  5003.9    0.07       0  5009.9    0.12       0
  5033.9    0.05       0  5287.2    0.16       0
Bank Sta=5003.9,5009.9
Exp/Cntr=0.3,0.1

Type RM Length L Ch R = 1,7967,448,448,448
BEGIN DESCRIPTION:
UNT 091 IN UKCR 11.0
END DESCRIPTION:
XS GIS Cut Line= 3
      3631649.59     10579260.20      3632149.61     10578960.19
      3632499.58     10578710.21
#Sta/Elev= 30
  4424.7  409.80  4454.6  405.76  4533.6  393.52  4564.7  391.59  4586.1  388.48
  4591.9  386.40  4658.0  379.96  4729.9  367.35  4739.6  367.38  4809.6  357.81
  4891.2  350.19  4972.8  349.35  4994.2  344.22  4997.0  341.24  4999.8  340.74
  5003.0  341.24  5010.9  342.36  5021.3  350.05  5048.5  349.31  5080.3  349.03
  5116.0  351.40  5172.5  357.82  5202.0  359.19  5237.6  363.10  5294.2  373.49
  5315.0  380.89  5351.9  387.99  5365.4  391.96  5409.7  399.63  5437.9  402.28
#Mann=5,-1,0
  4424.7    0.16       0  4454.6    0.12       0  4997.0    0.07       0
  5003.0    0.12       0  5048.5    0.16       0
Bank Sta=4997,5003
Exp/Cntr=0.3,0.1

Type RM Length L Ch R = 1,7519,455,455,455
BEGIN DESCRIPTION:
UNT 091 IN UKCR 10.0
END DESCRIPTION:
XS GIS Cut Line= 3
      3631799.60     10579560.20      3632499.61     10579160.19
      3632649.59     10578760.23
#Sta/Elev= 30
  4175.5  414.55  4273.3  402.94  4285.7  399.88  4307.2  398.51  4344.7  390.37
  4425.3  377.10  4543.4  363.02  4566.4  364.01  4601.7  363.63  4608.1  361.40
  4624.0  360.48  4629.7  362.33  4636.2  357.26  4667.2  352.86  4732.0  348.61
  4929.4  346.03  4984.4  344.30  4991.5  343.17  4993.9  337.84  4996.6  337.34
  4999.9  337.84  5045.3  345.59  5052.1  347.73  5082.3  348.94  5137.5  355.01
  5206.0  366.98  5228.3  373.56  5238.1  374.16  5308.4  389.88  5408.9  401.63
#Mann=8,-1,0
  4175.5    0.05       0  4273.3    0.12       0  4566.4    0.16       0
  4624.0    0.12       0  4929.4    0.16       0  4993.9    0.07       0
  4999.9    0.16       0  5045.3    0.05       0
Bank Sta=4993.9,4999.9
Exp/Cntr=0.3,0.1

Type RM Length L Ch R = 1,7064,460,460,460
BEGIN DESCRIPTION:
UNT 091 IN UKCR 9.0
END DESCRIPTION:
XS GIS Cut Line= 3
      3632549.58     10579810.23      3632849.61     10579360.19
      3632999.62     10578960.17
#Sta/Elev= 30
  4489.7  377.23  4518.3  374.47  4525.8  372.45  4605.4  362.09  4626.5  361.41
  4677.5  355.66  4698.6  354.76  4706.1  353.04  4806.7  341.94  4842.8  341.71
  4850.3  339.00  4857.8  338.79  4863.8  341.51  4987.0  343.17  4994.5  335.07
  4999.0  332.49  5001.8  331.99  5005.0  332.49  5008.0  337.28  5017.1  343.01
  5023.1  341.51  5033.2  341.54  5040.4  343.55  5062.6  345.95  5100.9  354.72
  5131.1  359.01  5186.3  373.31  5254.9  386.06  5318.9  393.20  5457.8  398.26
#Mann=3,-1,0
  4489.7    0.16       0  4999.0    0.07       0  5005.0    0.16       0
Bank Sta=4999,5005
Exp/Cntr=0.3,0.1

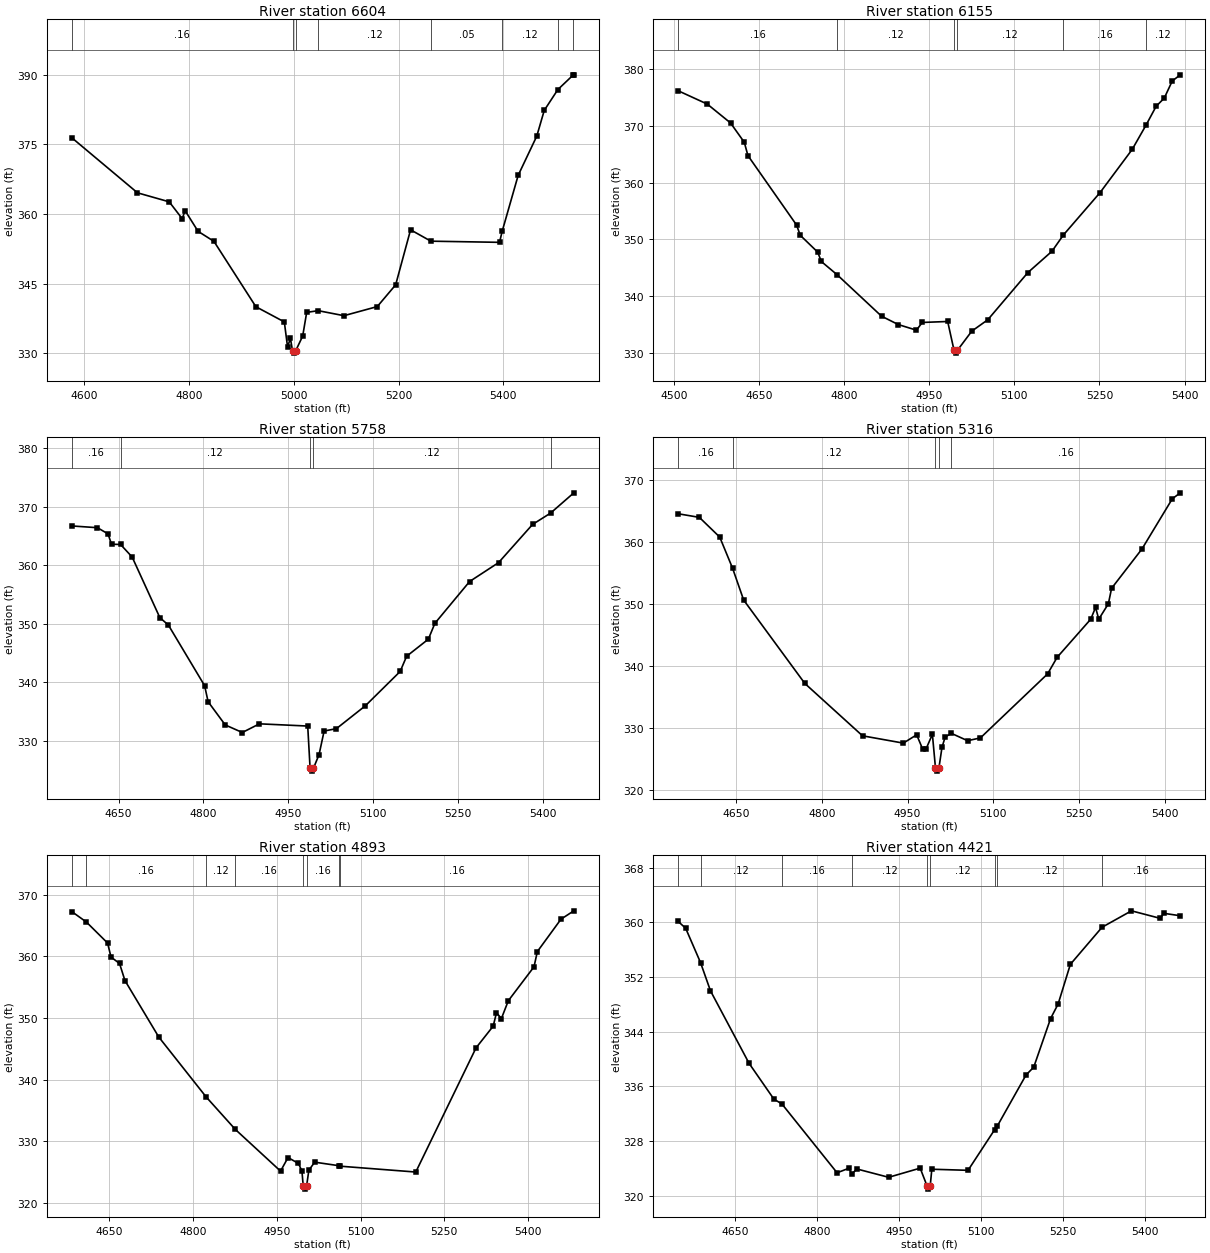
Type RM Length L Ch R = 1,6604,449,449,449
BEGIN DESCRIPTION:
UNT 091 IN UKCR 8.0
END DESCRIPTION:
XS GIS Cut Line= 3
      3632649.56     10579910.21      3633049.61     10579760.19
      3633449.64     10579410.16
#Sta/Elev= 30
  4575.9  376.44  4701.4  364.58  4762.0  362.64  4786.9  358.99  4792.2  360.76
  4817.1  356.29  4847.4  354.13  4927.5  340.06  4981.8  336.79  4988.0  331.40
  4993.4  333.25  4997.5  330.57  5000.2  330.07  5003.5  330.57  5016.9  333.75
  5024.5  338.84  5046.4  339.21  5095.7  338.13  5159.3  340.09  5194.4  344.77
  5222.9  356.62  5261.7  354.17  5392.8  353.92  5397.8  356.28  5428.4  368.35
  5463.9  376.78  5478.2  382.33  5504.2  386.81  5533.8  389.98  5534.7  389.98
#Mann=8,-1,0
  4575.9    0.16       0  4997.5    0.07       0  5003.5    0.16       0
  5046.4    0.12       0  5261.7    0.05       0  5397.8    0.12       0
  5504.2    0.16       0  5533.8    0.05       0
Bank Sta=4997.5,5003.5
Exp/Cntr=0.3,0.1

Type RM Length L Ch R = 1,6155,397,397,397
BEGIN DESCRIPTION:
UNT 091 IN UKCR 7.0
END DESCRIPTION:
XS GIS Cut Line= 3
      3632849.60     10580210.19      3633299.61     10580110.19
      3633599.64     10579810.15
#Sta/Elev= 30
  4507.3  376.17  4558.5  373.83  4599.5  370.51  4623.8  367.10  4630.2  364.76
  4716.0  352.53  4722.4  350.74  4753.2  347.77  4759.6  346.12  4787.8  343.76
  4865.8  336.49  4895.3  335.02  4927.3  334.03  4937.6  335.39  4982.4  335.56
  4993.6  330.49  4996.3  329.99  4999.6  330.49  5024.9  333.86  5053.1  335.86
  5123.9  344.18  5166.3  347.92  5186.3  350.77  5251.1  358.25  5307.7  365.84
  5332.3  370.15  5350.1  373.46  5364.3  374.88  5378.4  377.90  5392.6  378.98
#Mann=6,-1,0
  4507.3    0.16       0  4787.8    0.12       0  4993.6    0.07       0
  4999.6    0.12       0  5186.3    0.16       0  5332.3    0.12       0
Bank Sta=4993.6,4999.6
Exp/Cntr=0.3,0.1

Type RM Length L Ch R = 1,5758,442,442,442
BEGIN DESCRIPTION:
UNT 091 IN UKCR 6.0
END DESCRIPTION:
XS GIS Cut Line= 3
      3633149.58     10580560.20      3633549.61     10580410.19
      3633649.61     10579960.20
#Sta/Elev= 30
  4567.1  366.69  4612.5  366.39  4631.2  365.34  4637.4  363.57  4653.4  363.53
  4673.9  361.39  4722.9  351.05  4738.0  349.78  4802.1  339.44  4808.3  336.70
  4838.6  332.74  4868.8  331.45  4899.1  332.93  4984.5  332.55  4988.7  325.36
  4991.4  324.86  4994.7  325.36  5004.6  327.69  5013.5  331.70  5035.3  332.11
  5086.5  336.01  5148.0  341.86  5159.5  344.46  5197.9  347.37  5209.5  350.08
  5270.9  357.21  5322.1  360.43  5382.3  366.95  5414.1  368.88  5455.3  372.34
#Mann=5,-1,0
  4567.1    0.16       0  4653.4    0.12       0  4988.7    0.07       0
  4994.7    0.12       0  5414.1    0.16       0
Bank Sta=4988.7,4994.7
Exp/Cntr=0.3,0.1

Type RM Length L Ch R = 1,5316,423,423,423
BEGIN DESCRIPTION:
UNT 091 IN UKCR 5.0
END DESCRIPTION:
XS GIS Cut Line= 3
      3633399.60     10581160.20      3633649.61     10580810.19
      3634049.57     10580610.21
#Sta/Elev= 30
  4549.3  364.56  4586.2  363.98  4621.8  360.80  4644.3  355.76  4663.6  350.64
  4770.5  337.18  4871.3  328.73  4942.6  327.55  4965.9  328.89  4976.4  326.59
  4982.2  326.59  4993.4  328.97  4998.8  323.53  5001.5  323.03  5004.8  323.53
  5010.2  326.89  5015.8  328.55  5026.7  329.12  5054.9  327.94  5077.3  328.39
  5194.7  338.72  5211.4  341.40  5270.1  347.55  5278.5  349.45  5284.1  347.55
  5300.9  350.04  5306.5  352.53  5359.6  358.88  5412.7  366.99  5426.6  367.94
#Mann=5,-1,0
  4549.3    0.16       0  4644.3    0.12       0  4998.8    0.07       0
  5004.8    0.12       0  5026.7    0.16       0
Bank Sta=4998.8,5004.8
Exp/Cntr=0.3,0.1

Type RM Length L Ch R = 1,4893,472,472,472
BEGIN DESCRIPTION:
UNT 091 IN UKCR 4.0
END DESCRIPTION:
XS GIS Cut Line= 3
      3633449.59     10581310.20      3633849.61     10581160.19
      3634099.60     10580760.20
#Sta/Elev= 30
  4583.0  367.24  4609.2  365.54  4647.1  362.14  4653.3  359.86  4668.5  358.83
  4678.2  356.06  4738.8  346.90  4823.6  337.19  4875.9  331.92  4956.8  325.17
  4970.2  327.37  4988.9  326.41  4995.1  325.15  4997.4  322.75  5000.2  322.25
  5003.4  322.75  5007.5  325.32  5017.9  326.62  5061.8  326.04  5063.2  325.97
  5198.9  325.02  5306.8  345.15  5337.5  348.67  5343.4  350.84  5352.2  349.90
  5364.6  352.79  5410.6  358.29  5416.5  360.75  5458.9  366.01  5481.9  367.36
#Mann=8,-1,0
  4583.0     0.1       0  4609.2    0.16       0  4823.6    0.12       0
  4875.9    0.16       0  4997.4    0.07       0  5003.4    0.16       0
  5061.8    0.12       0  5063.2    0.16       0
Bank Sta=4997.4,5003.4
Exp/Cntr=0.3,0.1

Type RM Length L Ch R = 1,4421,481,481,481
BEGIN DESCRIPTION:
UNT 091 IN UKCR 3.0
END DESCRIPTION:
XS GIS Cut Line= 3
      3633799.59     10581610.20      3634199.61     10581360.19
      3634399.59     10580960.22
#Sta/Elev= 30
  4546.4  360.12  4560.0  359.13  4587.2  354.11  4605.4  349.98  4676.1  339.37
  4721.5  334.14  4736.1  333.44  4837.1  323.37  4858.3  324.02  4864.2  323.24
  4873.7  323.92  4931.5  322.71  4989.2  324.05  5001.6  321.48  5004.3  320.98
  5007.6  321.48  5010.5  323.89  5076.8  323.73  5125.7  329.70  5129.9  330.14
  5183.0  337.68  5197.0  338.81  5227.8  345.91  5241.7  348.06  5264.1  353.86
  5322.1  359.28  5375.9  361.68  5429.0  360.57  5434.6  361.32  5465.3  360.96
#Mann=9,-1,0
  4546.4    0.16       0  4587.2    0.12       0  4736.1    0.16       0
  4864.2    0.12       0  5001.6    0.07       0  5007.6    0.12       0
  5125.7    0.16       0  5129.9    0.12       0  5322.1    0.16       0
Bank Sta=5001.6,5007.6
Exp/Cntr=0.3,0.1

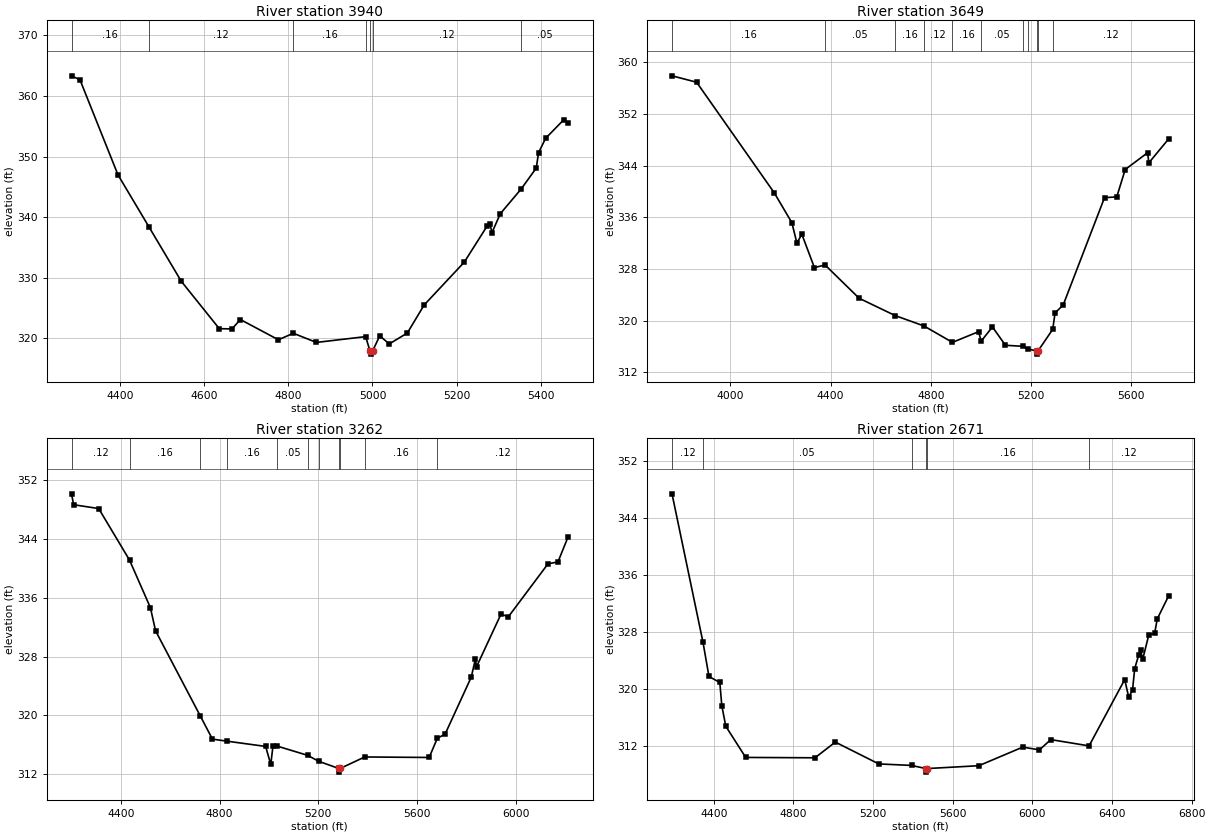
Type RM Length L Ch R = 1,3940,291,291,291
BEGIN DESCRIPTION:
UNT 091 IN UKCR 2.0
END DESCRIPTION:
XS GIS Cut Line= 3
      3633799.59     10581660.19      3634549.61     10581610.19
      3634699.61     10581210.17
#Sta/Elev= 30
  4285.6  363.34  4305.7  362.69  4395.9  347.00  4469.1  338.45  4546.2  329.43
  4636.4  321.61  4666.5  321.57  4686.5  323.12  4776.7  319.78  4812.2  320.85
  4866.9  319.34  4983.8  320.30  4994.2  317.91  4996.9  317.41  5000.2  317.91
  5017.2  320.42  5040.0  319.10  5082.7  320.89  5122.7  325.52  5218.0  332.60
  5272.2  338.55  5278.5  338.94  5283.8  337.48  5303.4  340.58  5352.9  344.66
  5388.8  348.12  5394.2  350.65  5411.1  353.04  5454.7  356.13  5464.5  355.56
#Mann=7,-1,0
  4285.6    0.16       0  4469.1    0.12       0  4812.2    0.16       0
  4983.8    0.12       0  4994.2    0.07       0  5000.2    0.12       0
  5352.9    0.05       0
Bank Sta=4994.2,5000.2
Exp/Cntr=0.3,0.1

Type RM Length L Ch R = 1,3649,387,387,387
BEGIN DESCRIPTION:
Mapping XS 820cc4ef
END DESCRIPTION:
XS GIS Cut Line= 4
      3633461.40     10582080.19      3634211.36     10582094.08
      3634725.25     10581823.24      3634884.80     10581191.98
#Sta/Elev= 30
  3767.2  357.91  3865.4  356.92  4175.5  339.79  4245.5  335.18  4265.5  332.04
  4285.5  333.38  4335.5  328.23  4378.0  328.64  4513.9  323.49  4658.0  320.80
  4772.2  319.21  4886.3  316.66  4991.2  318.32  5000.5  316.82  5046.0  319.05
  5097.8  316.21  5166.9  316.05  5186.4  315.64  5222.1  315.34  5224.9  314.84
  5228.1  315.34  5286.6  318.68  5295.9  321.22  5328.3  322.44  5493.3  339.06
  5542.1  339.17  5575.8  343.41  5665.2  346.01  5670.3  344.45  5749.3  348.15
#Mann=11,-1,0
  3767.2    0.16       0  4378.0    0.05       0  4658.0    0.16       0
  4772.2    0.12       0  4886.3    0.16       0  5000.5    0.05       0
  5166.9    0.16       0  5186.4    0.05       0  5222.1    0.07       0
  5228.1    0.05       0  5286.6    0.12       0
Bank Sta=5222.1,5228.1
Exp/Cntr=0.3,0.1

Type RM Length L Ch R = 1,3262,591,591,591
BEGIN DESCRIPTION:
Mapping XS 7f74b72a
END DESCRIPTION:
XS GIS Cut Line= 4
      3634034.71     10582698.10      3634725.90     10582227.01
      3634915.11     10581983.74      3634984.61     10581118.88
#Sta/Elev= 30
  4200.1  350.09  4208.7  348.61  4310.3  348.09  4435.1  341.10  4519.7  334.64
  4540.7  331.49  4722.4  319.90  4771.1  316.78  4831.0  316.50  4986.6  315.79
  5007.5  313.34  5016.4  315.85  5033.9  315.83  5156.8  314.58  5202.4  313.76
  5282.9  312.80  5285.7  312.30  5288.9  312.80  5388.1  314.36  5649.3  314.29
  5682.3  316.90  5713.7  317.45  5819.8  325.20  5836.4  327.64  5841.4  326.63
  5940.2  333.75  5970.3  333.40  6130.8  340.59  6171.0  340.84  6212.4  344.27
#Mann=11,-1,0
  4200.1    0.12       0  4435.1    0.16       0  4722.4    0.05       0
  4831.0    0.16       0  5033.9    0.05       0  5156.8     0.1       0
  5202.4    0.05       0  5282.9    0.07       0  5288.9    0.05       0
  5388.1    0.16       0  5682.3    0.12       0
Bank Sta=5282.9,5288.9
Exp/Cntr=0.3,0.1

Type RM Length L Ch R = 1,2671,0,0,0
BEGIN DESCRIPTION:
UNT 091 IN UKCR 1.0
END DESCRIPTION:
XS GIS Cut Line= 4
      3634149.61     10582810.19      3634864.91     10582829.40
      3635239.48     10582219.29      3635149.61     10581160.18
#Sta/Elev= 30
  4190.1  347.36  4345.7  326.55  4375.7  321.75  4430.2  320.91  4440.2  317.66
  4460.2  314.77  4560.2  310.40  4908.1  310.35  5010.3  312.55  5228.7  309.49
  5393.2  309.28  5465.0  308.84  5467.7  308.34  5471.0  308.84  5731.1  309.24
  5951.9  311.85  6035.6  311.46  6092.4  312.90  6284.7  312.02  6463.7  321.31
  6483.8  318.86  6503.0  319.85  6513.9  322.86  6533.9  324.75  6544.0  325.44
  6554.0  324.14  6584.1  327.51  6614.2  327.83  6627.3  329.83  6684.5  333.06
#Mann=6,-1,0
  4190.1    0.12       0  4345.7    0.05       0  5393.2    0.16       0
  5465.0    0.03       0  5471.0    0.16       0  6284.7    0.12       0
Bank Sta=5465,5471
Exp/Cntr=0.3,0.1

Chan Stop Cuts=-1