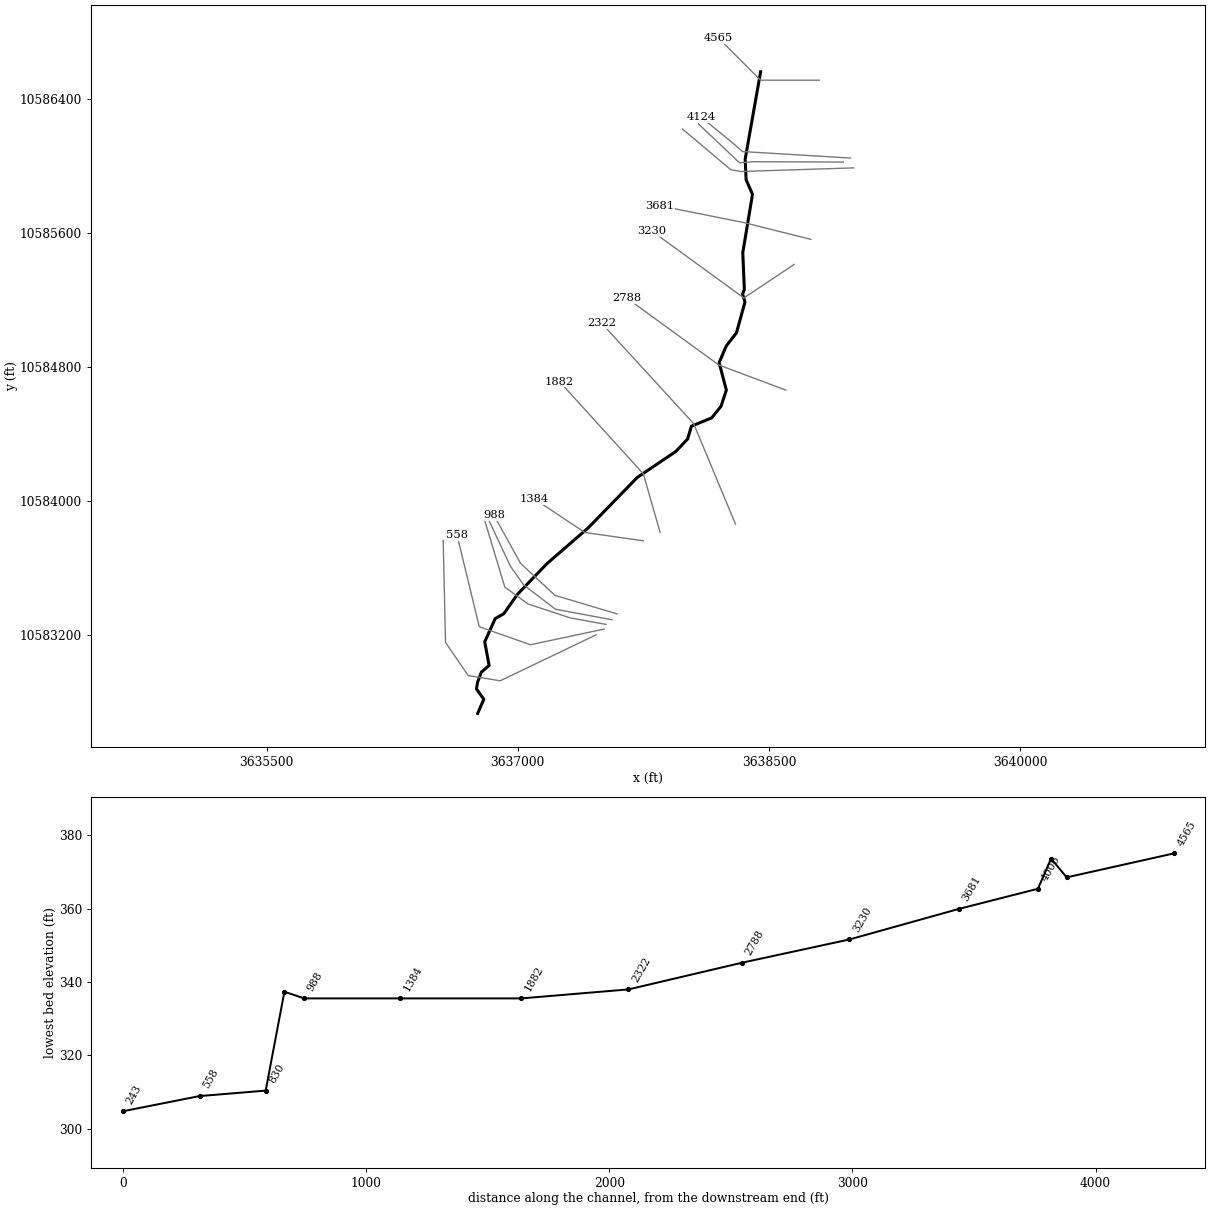
--- UNT 092 IN UKCR.prj (project) ---

Proj Title=UNT 092 IN UKCR Base Level Engineering
Current Plan=p01
Default Exp/Contr=0.3,0.1
English Units
Geom File=g01
Flow File=f01
Plan File=p01
BEGIN DESCRIPTION:
UNT 092 IN UKCR
END DESCRIPTION:

--- UNT 092 IN UKCR.p01 (plan) ---

Plan Title=Multiple Run
Short Identifier=Multiple
Geom File=g01
Flow File=f01
Subcritical Flow
K Sum by GR= 0
Std Step Tol= 0.01
Critical Tol= 0.01
Num of Std Step Trials= 20
Max Error Tol= 0.3
Flow Tol Ratio= 0.001
Split Flow NTrial= 30
Split Flow Tol= 0.02
Split Flow Ratio= 0.02
Log Output Level= 0
Friction Slope Method= 1
Unsteady Friction Slope Method= 2
Unsteady Bridges Friction Slope Method= 1
Parabolic Critical Depth
Global Vel Dist=  1 , 1 , 1
Global Log Level= 0
CheckData=True
Encroach Param= -1, 0, 0, 0
BEGIN DESCRIPTION:
Multiple Run
END DESCRIPTION:

--- UNT 092 IN UKCR.f01 (steady flow) ---

Flow Title=Multiple
Number of Profiles=7
Profile Names=10-year,25-year,50-year,1pct_min,100-year,1pct_plu,500-year
River Rch & RM= UNT 092 IN UKCR,Reach-1,4565
     727     988    1202    1072    1450    1961    2096
Boundary for River Rch & Prof#=UNT 092 IN UKCR,Reach-1,1
Up Type=0
Dn Type=3
Dn Slope=0.005
Boundary for River Rch & Prof#=UNT 092 IN UKCR,Reach-1,2
Up Type=0
Dn Type=3
Dn Slope=0.005
Boundary for River Rch & Prof#=UNT 092 IN UKCR,Reach-1,3
Up Type=0
Dn Type=3
Dn Slope=0.005
Boundary for River Rch & Prof#=UNT 092 IN UKCR,Reach-1,4
Up Type=0
Dn Type=3
Dn Slope=0.005
Boundary for River Rch & Prof#=UNT 092 IN UKCR,Reach-1,5
Up Type=0
Dn Type=3
Dn Slope=0.005
Boundary for River Rch & Prof#=UNT 092 IN UKCR,Reach-1,6
Up Type=0
Dn Type=3
Dn Slope=0.005
Boundary for River Rch & Prof#=UNT 092 IN UKCR,Reach-1,7
Up Type=0
Dn Type=3
Dn Slope=0.005

--- UNT 092 IN UKCR.g01 (geometry) ---

Geom Title=Existing Conditions

River Reach=UNT 092 IN UKCR,Reach-1
Reach XY= 30
      3638449.61     10586560.19      3638357.50     10586039.00
      3638363.00     10585916.00      3638401.25     10585829.00
      3638343.25     10585481.00      3638352.50     10585261.00
      3638342.00     10585234.00      3638356.25     10585186.00
      3638305.50     10585002.00      3638244.25     10584923.00
      3638202.00     10584824.00      3638245.00     10584660.00
      3638213.25     10584563.00      3638157.25     10584494.00
      3638036.75     10584445.00      3638013.75     10584368.00
      3637942.50     10584293.00      3637713.75     10584139.00
      3637419.75     10583837.00      3637174.00     10583624.00
      3636999.00     10583442.00      3636916.25     10583325.00
      3636865.00     10583296.00      3636802.50     10583157.00
      3636828.75     10583016.00      3636782.25     10582976.00
      3636760.00     10582917.00      3636753.25     10582876.00
      3636797.00     10582814.00      3636760.50     10582730.00

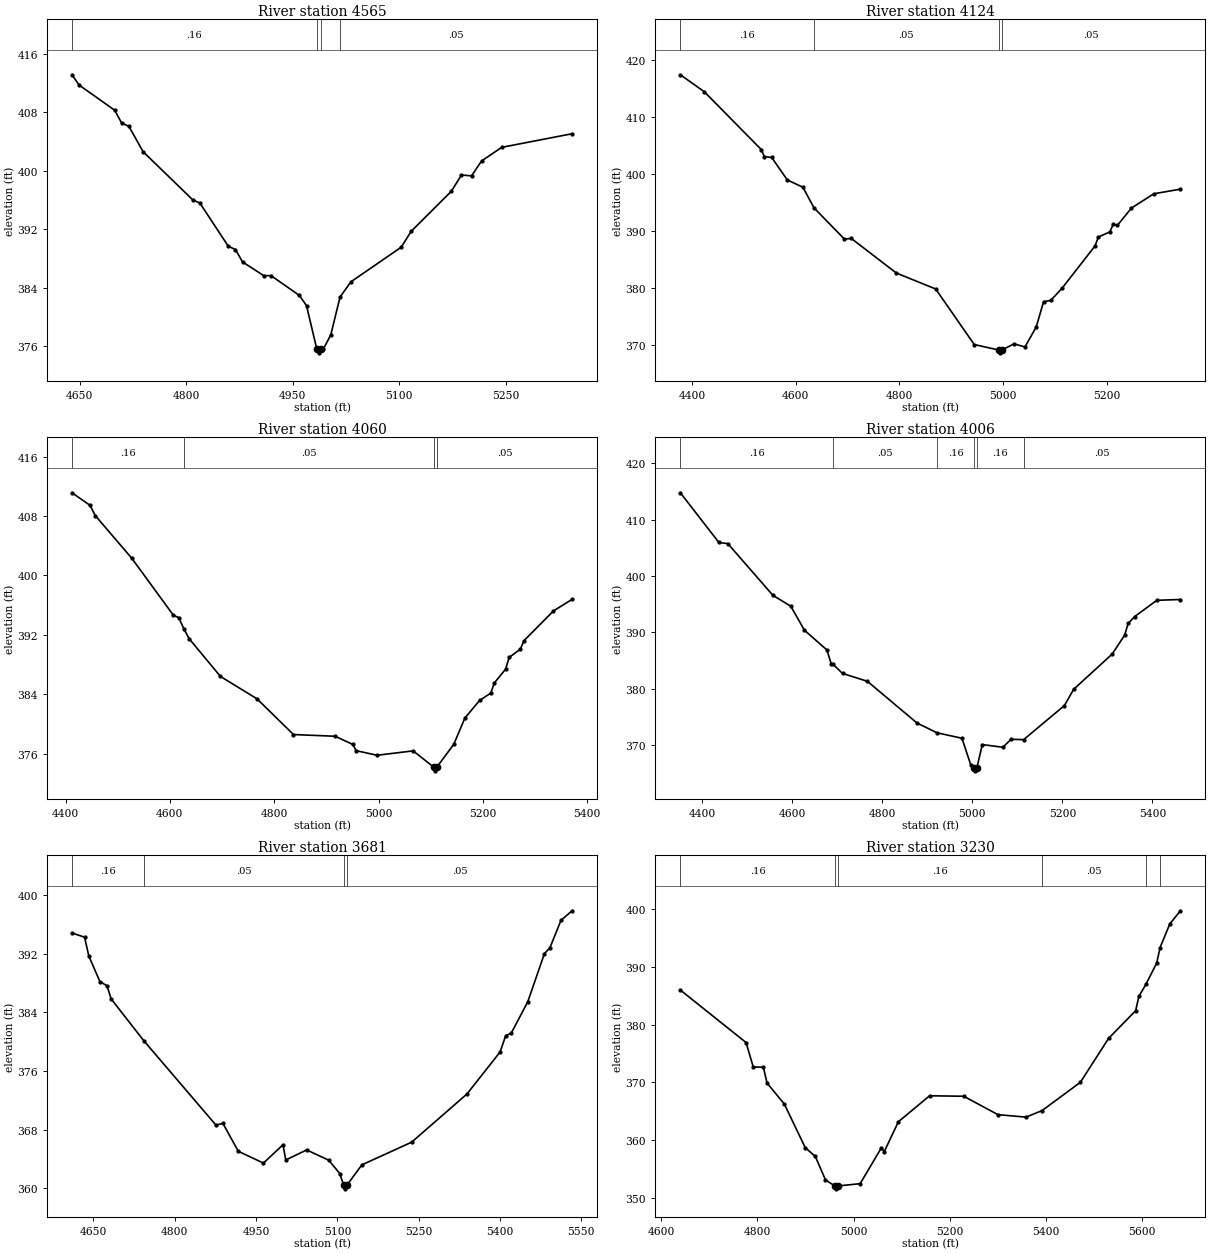
Type RM Length L Ch R = 1,4565,441,441,441
BEGIN DESCRIPTION:
UNT 092 IN UKCR 10.0
END DESCRIPTION:
XS GIS Cut Line= 3
      3638799.65     10586510.19      3638449.61     10586510.19
      3638199.60     10586760.19
#Sta/Elev= 30
  4639.4  413.12  4649.4  411.72  4699.4  408.27  4709.4  406.50  4719.4  406.08
  4739.4  402.60  4809.4  396.00  4819.4  395.56  4859.4  389.65  4869.4  389.21
  4879.4  387.51  4909.4  385.62  4919.4  385.64  4959.4  382.92  4969.4  381.53
  4983.9  375.57  4986.7  375.07  4989.9  375.57  4993.0  375.57  5003.6  377.55
  5016.6  382.71  5031.9  384.79  5102.6  389.52  5116.7  391.70  5173.3  397.19
  5187.4  399.40  5201.6  399.29  5215.7  401.32  5244.0  403.19  5343.0  405.05
#Mann=4,-1,0
  4639.4    0.16       0  4983.9    0.07       0  4989.9    0.16       0
  5016.6    0.05       0
Bank Sta=4983.9,4989.9
Exp/Cntr=0.3,0.1

Type RM Length L Ch R = 1,4124,64,64,64
BEGIN DESCRIPTION:
Mapping XS 9b4620b3
END DESCRIPTION:
XS GIS Cut Line= 4
      3638985.57     10586045.35      3638340.99     10586084.41
      3638284.57     10586134.33      3638095.76     10586288.41
#Sta/Elev= 30
  4377.5  417.45  4423.5  414.48  4533.7  404.29  4539.5  403.07  4553.8  402.90
  4583.8  398.95  4613.9  397.67  4635.3  394.05  4694.0  388.55  4707.3  388.66
  4794.2  382.58  4870.1  379.77  4944.5  370.00  4991.6  369.04  4994.3  368.54
  4997.6  369.04  5021.5  370.12  5042.3  369.57  5064.1  373.09  5078.3  377.54
  5091.9  377.75  5113.6  379.86  5177.5  387.34  5184.0  388.91  5206.2  389.82
  5212.7  391.18  5220.6  390.95  5247.9  394.01  5291.0  396.52  5342.3  397.33
#Mann=4,-1,0
  4377.5    0.16       0  4635.3    0.05       0  4991.6    0.03       0
  4997.6    0.05       0
Bank Sta=4991.6,4997.6
Exp/Cntr=0.3,0.1

Type RM Length L Ch R = 1,4060,54,54,54
BEGIN DESCRIPTION:
UNT 092 IN UKCR 9.0
END DESCRIPTION:
XS GIS Cut Line= 4
      3638944.24     10586021.48      3638406.09     10586023.65
      3638323.63     10586017.14      3638078.40     10586249.35
#Sta/Elev= 30
  4412.4  411.14  4447.0  409.45  4457.0  408.07  4527.0  402.32  4607.0  394.62
  4617.0  394.32  4626.9  392.80  4637.0  391.48  4697.0  386.39  4767.0  383.38
  4837.0  378.56  4917.0  378.33  4950.6  377.23  4957.1  376.39  4997.2  375.77
  5066.4  376.36  5105.9  374.17  5108.6  373.67  5111.9  374.17  5144.4  377.26
  5165.5  380.77  5193.8  383.16  5215.2  384.14  5222.1  385.52  5243.6  387.37
  5250.4  388.95  5271.9  390.06  5278.8  391.20  5335.4  395.22  5371.0  396.77
#Mann=4,-1,0
  4412.4    0.16       0  4626.9    0.05       0  5105.9    0.03       0
  5111.9    0.05       0
Bank Sta=5105.9,5111.9
Exp/Cntr=0.3,0.1

Type RM Length L Ch R = 1,4006,325,325,325
BEGIN DESCRIPTION:
Mapping XS 0abec377
END DESCRIPTION:
XS GIS Cut Line= 4
      3639005.02     10585986.76      3638330.14     10585965.06
      3638271.55     10585975.91      3637983.73     10586218.28
#Sta/Elev= 30
  4351.3  414.76  4436.8  405.95  4456.8  405.74  4556.8  396.58  4596.8  394.63
  4626.9  390.39  4676.9  386.88  4686.9  384.33  4690.9  384.31  4711.6  382.72
  4766.9  381.32  4877.0  373.93  4921.5  372.19  4977.0  371.22  4997.0  366.39
  5004.1  365.94  5006.8  365.44  5010.1  365.94  5022.2  370.10  5067.8  369.62
  5086.1  371.04  5114.0  370.97  5204.5  377.01  5225.3  379.91  5310.9  386.16
  5338.5  389.51  5346.3  391.58  5360.6  392.79  5410.0  395.69  5462.4  395.83
#Mann=6,-1,0
  4351.3    0.16       0  4690.9    0.05       0  4921.5    0.16       0
  5004.1    0.07       0  5010.1    0.16       0  5114.0    0.05       0
Bank Sta=5004.1,5010.1
Exp/Cntr=0.3,0.1

Type RM Length L Ch R = 1,3681,451,451,451
BEGIN DESCRIPTION:
UNT 092 IN UKCR 8.0
END DESCRIPTION:
XS GIS Cut Line= 3
      3638749.65     10585560.18      3638349.61     10585660.19
      3637849.57     10585760.20
#Sta/Elev= 30
  4610.5  394.82  4633.7  394.25  4641.5  391.70  4662.1  388.18  4675.0  387.64
  4682.7  385.84  4743.3  380.11  4876.0  368.64  4888.9  368.87  4917.2  365.07
  4963.6  363.46  4999.7  365.96  5004.8  363.88  5043.3  365.25  5084.0  363.86
  5104.4  362.04  5111.6  360.45  5114.4  359.95  5117.6  360.45  5145.2  363.22
  5237.0  366.31  5339.0  372.88  5400.2  378.61  5410.4  380.82  5420.6  381.16
  5451.2  385.45  5481.8  392.00  5492.0  392.81  5512.4  396.54  5532.8  397.85
#Mann=4,-1,0
  4610.5    0.16       0  4743.3    0.05       0  5111.6    0.03       0
  5117.6    0.05       0
Bank Sta=5111.6,5117.6
Exp/Cntr=0.3,0.1

Type RM Length L Ch R = 1,3230,442,442,442
BEGIN DESCRIPTION:
UNT 092 IN UKCR 7.0
END DESCRIPTION:
XS GIS Cut Line= 3
      3638649.61     10585410.19      3638349.61     10585210.19
      3637799.63     10585610.17
#Sta/Elev= 30
  4639.6  385.98  4776.3  376.91  4791.3  372.68  4812.4  372.64  4819.9  369.91
  4855.9  366.28  4899.5  358.73  4920.5  357.21  4941.6  353.15  4961.1  352.11
  4963.8  351.61  4967.1  352.11  5013.7  352.50  5057.7  358.67  5063.9  358.05
  5093.3  363.21  5158.2  367.70  5229.3  367.62  5300.4  364.44  5358.7  364.01
  5392.3  365.14  5472.0  370.03  5530.7  377.62  5587.1  382.42  5593.7  384.87
  5608.9  387.06  5630.8  390.64  5637.9  393.33  5658.2  397.43  5680.2  399.69
#Mann=6,-1,0
  4639.6    0.16       0  4961.1    0.07       0  4967.1    0.16       0
  5392.3    0.05       0  5608.9    0.08       0  5637.9    0.05       0
Bank Sta=4961.1,4967.1
Exp/Cntr=0.3,0.1

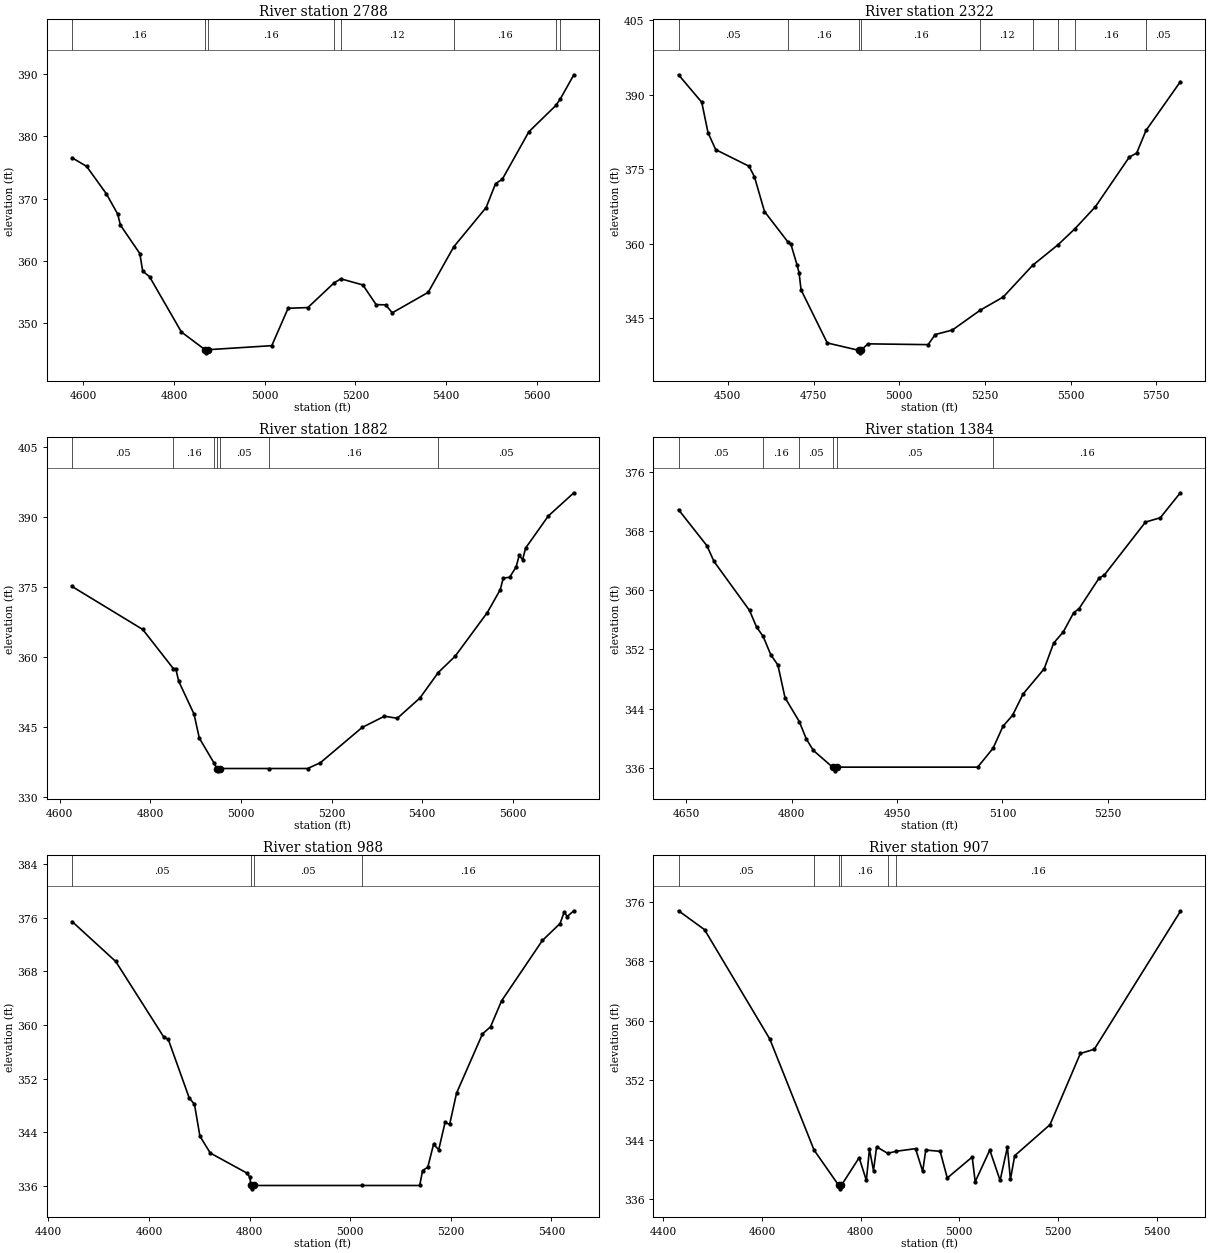
Type RM Length L Ch R = 1,2788,466,466,466
BEGIN DESCRIPTION:
UNT 092 IN UKCR 6.0
END DESCRIPTION:
XS GIS Cut Line= 3
      3638599.63     10584660.18      3638199.61     10584810.19
      3637649.61     10585210.19
#Sta/Elev= 30
  4574.9  376.56  4607.0  375.18  4650.6  370.77  4675.5  367.54  4681.7  365.74
  4724.4  361.20  4730.7  358.38  4745.8  357.49  4816.1  348.62  4868.3  345.77
  4871.0  345.27  4874.3  345.77  5015.6  346.42  5051.6  352.42  5095.2  352.53
  5153.1  356.49  5168.0  357.14  5216.6  356.16  5245.9  353.00  5266.8  352.97
  5281.5  351.69  5360.7  354.97  5417.2  362.28  5488.6  368.58  5509.5  372.42
  5524.2  373.10  5582.9  380.73  5642.8  384.97  5651.9  385.95  5682.2  389.87
#Mann=8,-1,0
  4574.9    0.16       0  4868.3    0.07       0  4874.3    0.16       0
  5153.1    0.05       0  5168.0    0.12       0  5417.2    0.16       0
  5642.8    0.08       0  5651.9    0.05       0
Bank Sta=4868.3,4874.3
Exp/Cntr=0.3,0.1

Type RM Length L Ch R = 1,2322,440,440,440
BEGIN DESCRIPTION:
UNT 092 IN UKCR 5.0
END DESCRIPTION:
XS GIS Cut Line= 3
      3638299.62     10583860.17      3638049.61     10584460.19
      3637499.58     10585060.22
#Sta/Elev= 30
  4356.1  393.99  4423.8  388.46  4442.2  382.32  4464.5  378.92  4562.0  375.57
  4577.7  373.42  4606.9  366.46  4675.7  360.29  4683.8  359.92  4702.2  355.61
  4707.7  354.17  4713.6  350.69  4790.0  340.00  4882.3  338.51  4885.1  338.01
  4888.3  338.51  4908.6  339.82  5084.1  339.66  5105.1  341.70  5155.0  342.60
  5236.6  346.61  5303.6  349.26  5389.5  355.65  5463.1  359.76  5512.7  363.00
  5572.5  367.44  5671.1  377.41  5692.7  378.22  5720.0  382.78  5820.1  392.59
#Mann=9,-1,0
  4356.1    0.05       0  4675.7    0.16       0  4882.3    0.07       0
  4888.3    0.16       0  5236.6    0.12       0  5389.5    0.16       0
  5463.1    0.12       0  5512.7    0.16       0  5720.0    0.05       0
Bank Sta=4882.3,4888.3
Exp/Cntr=0.3,0.1

Type RM Length L Ch R = 1,1882,498,498,498
BEGIN DESCRIPTION:
UNT 092 IN UKCR 4.0
END DESCRIPTION:
XS GIS Cut Line= 3
      3637849.61     10583810.19      3637749.61     10584160.19
      3637249.61     10584710.19
#Sta/Elev= 30
  4627.3  375.10  4783.3  365.88  4850.6  357.51  4856.1  357.48  4862.6  354.78
  4896.4  347.74  4908.1  342.58  4940.5  337.25  4946.7  336.06  4949.4  335.56
  4952.7  336.06  5061.7  336.06  5147.1  336.06  5175.4  337.31  5267.3  344.86
  5316.7  347.28  5345.0  346.83  5395.0  351.19  5435.4  356.65  5472.8  360.16
  5543.7  369.52  5572.1  374.41  5578.8  376.88  5593.0  377.09  5607.2  379.30
  5614.0  381.79  5621.4  380.83  5628.2  383.35  5678.2  390.22  5734.6  395.20
#Mann=7,-1,0
  4627.3    0.05       0  4850.6    0.16       0  4940.5    0.05       0
  4946.7   0.033       0  4952.7    0.05       0  5061.7    0.16       0
  5435.4    0.05       0
Bank Sta=4946.7,4952.7
Exp/Cntr=0.3,0.1

Type RM Length L Ch R = 1,1384,396,396,396
BEGIN DESCRIPTION:
UNT 092 IN UKCR 3.0
END DESCRIPTION:
XS GIS Cut Line= 3
      3637749.62     10583760.19      3637399.61     10583810.19
      3637099.63     10584010.18
#Sta/Elev= 30
  4639.1  370.92  4679.5  366.04  4689.6  363.91  4740.1  357.28  4750.2  355.02
  4759.5  353.77  4770.4  351.27  4780.5  349.89  4790.6  345.47  4811.0  342.22
  4820.9  339.88  4831.0  338.32  4858.3  336.06  4861.1  335.56  4864.3  336.06
  5064.8  336.06  5086.7  338.62  5100.8  341.59  5114.4  343.07  5129.4  345.96
  5159.4  349.37  5172.9  352.85  5186.5  354.35  5201.5  356.98  5209.0  357.51
  5237.5  361.64  5245.1  362.08  5303.6  369.24  5324.7  369.83  5353.2  373.21
#Mann=6,-1,0
  4639.1    0.05       0  4759.5    0.16       0  4811.0    0.05       0
  4858.3   0.033       0  4864.3    0.05       0  5086.7    0.16       0
Bank Sta=4858.3,4864.3
Exp/Cntr=0.3,0.1

Type RM Length L Ch R = 1,988,81,81,81
BEGIN DESCRIPTION:
Mapping XS 0d03f41a
END DESCRIPTION:
XS GIS Cut Line= 4
      3637592.75     10583323.81      3637221.20     10583434.93
      3637016.34     10583625.91      3636856.60     10583914.12
#Sta/Elev= 30
  4447.1  375.43  4533.9  369.47  4629.7  358.16  4638.3  357.85  4680.0  349.11
  4690.4  348.17  4701.2  343.42  4721.8  340.90  4794.8  337.90  4800.5  337.30
  4802.7  336.06  4805.4  335.56  4808.7  336.06  5024.1  336.06  5138.1  336.06
  5143.8  338.29  5154.1  338.78  5165.6  342.19  5175.9  341.41  5188.5  345.46
  5197.6  345.17  5211.3  349.83  5262.9  358.67  5278.9  359.73  5300.7  363.58
  5381.9  372.60  5417.1  375.13  5425.4  376.86  5431.1  376.17  5444.5  377.03
#Mann=4,-1,0
  4447.1    0.05       0  4802.7   0.033       0  4808.7    0.05       0
  5024.1    0.16       0
Bank Sta=4802.7,4808.7
Exp/Cntr=0.3,0.1

Type RM Length L Ch R = 1,907,77,77,77
BEGIN DESCRIPTION:
Mapping XS d4a16ff2
END DESCRIPTION:
XS GIS Cut Line= 5
      3637561.43     10583289.11      3637224.45     10583351.85
      3637034.61     10583497.17      3636955.79     10583608.62
      3636828.84     10583879.38
#Sta/Elev= 30
  4430.8  374.81  4483.5  372.27  4615.8  357.55  4705.6  342.60  4755.2  337.88
  4757.9  337.38  4761.2  337.88  4797.0  341.57  4811.6  338.52  4817.9  342.71
  4826.1  339.83  4832.4  343.04  4854.8  342.16  4872.4  342.44  4911.3  342.79
  4925.8  339.74  4932.1  342.60  4961.2  342.43  4975.7  338.84  5026.2  341.66
  5032.3  338.34  5061.9  342.60  5082.8  338.51  5097.6  343.00  5103.7  338.65
  5112.4  341.84  5184.0  346.02  5245.5  355.60  5273.8  356.17  5448.2  374.72
#Mann=6,-1,0
  4430.8    0.05       0  4705.6    0.16       0  4755.2    0.07       0
  4761.2    0.16       0  4854.8    0.05       0  4872.4    0.16       0
Bank Sta=4755.2,4761.2
Exp/Cntr=0.3,0.1

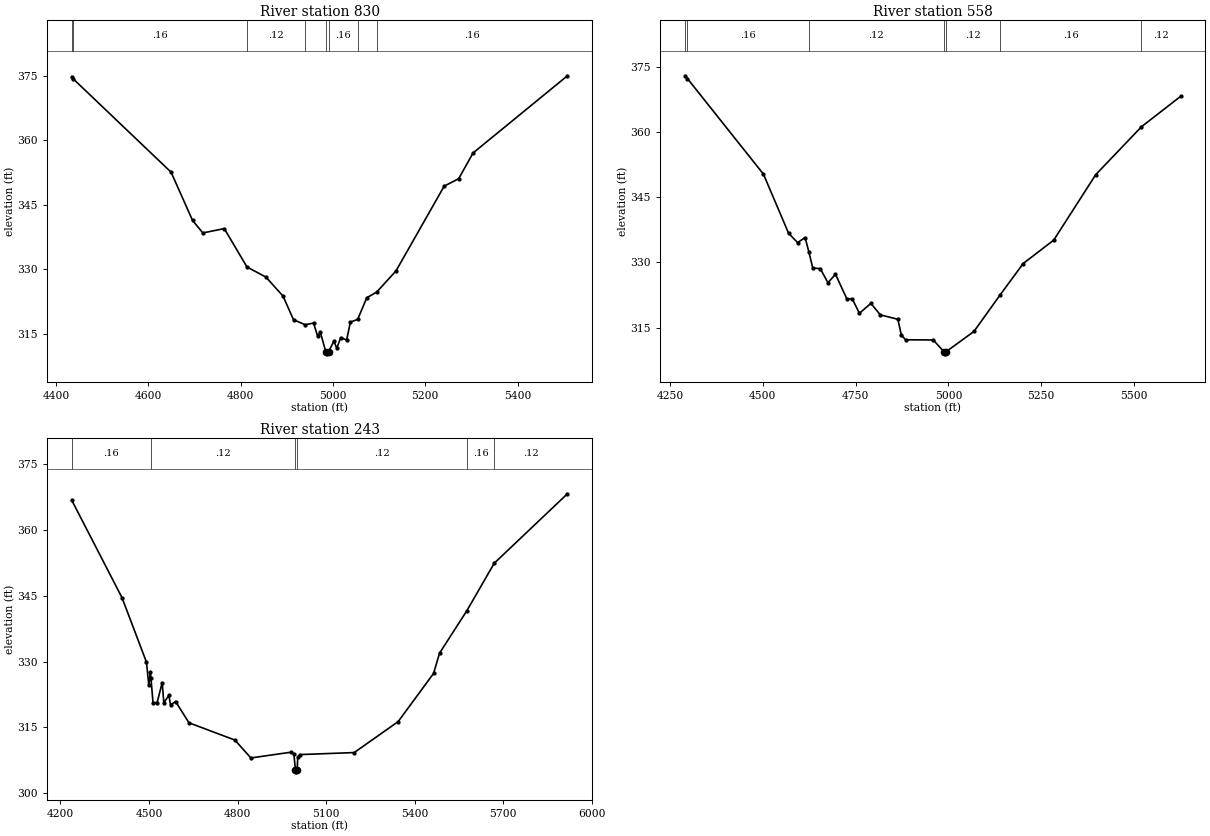
Type RM Length L Ch R = 1,830,272,272,272
BEGIN DESCRIPTION:
UNT 092 IN UKCR 2.0
END DESCRIPTION:
XS GIS Cut Line= 5
      3637526.76     10583261.32      3637314.95     10583299.52
      3637061.48     10583382.85      3636922.59     10583483.55
      3636801.24     10583885.74
#Sta/Elev= 30
  4434.4  374.74  4438.0  374.18  4649.6  352.57  4696.0  341.39  4718.4  338.48
  4764.8  339.49  4813.9  330.59  4854.9  328.24  4892.0  323.84  4914.8  318.33
  4939.9  317.19  4958.2  317.56  4966.8  314.58  4972.9  315.47  4984.6  310.93
  4987.4  310.43  4990.6  310.93  5002.3  313.36  5008.5  311.71  5017.0  314.19
  5029.9  313.64  5037.9  317.77  5053.8  318.44  5073.5  323.45  5094.7  324.74
  5136.7  329.66  5241.2  349.34  5272.5  351.06  5303.8  357.04  5508.1  374.94
#Mann=8,-1,0
  4434.4    0.05       0  4438.0    0.16       0  4813.9    0.12       0
  4939.9    0.16       0  4984.6    0.07       0  4990.6    0.16       0
  5053.8    0.12       0  5094.7    0.16       0
Bank Sta=4984.6,4990.6
Exp/Cntr=0.3,0.1

Type RM Length L Ch R = 1,558,315,315,315
BEGIN DESCRIPTION:
Mapping XS e350b8fc
END DESCRIPTION:
XS GIS Cut Line= 4
      3637516.35     10583233.55      3637075.37     10583139.80
      3636769.81     10583247.43      3636637.86     10583792.59
#Sta/Elev= 30
  4290.2  373.05  4296.7  372.41  4501.6  350.38  4569.4  336.74  4593.6  334.59
  4613.9  335.75  4623.8  332.53  4634.5  328.74  4654.9  328.57  4675.4  325.34
  4695.8  327.28  4726.5  321.61  4741.0  321.63  4760.2  318.29  4791.1  320.57
  4816.8  317.92  4863.8  316.91  4873.4  313.23  4885.0  312.18  4959.2  312.14
  4988.0  309.44  4990.7  308.94  4994.0  309.44  5069.0  314.11  5140.2  322.61
  5201.6  329.76  5283.9  335.16  5397.1  350.25  5520.3  361.29  5625.9  368.31
#Mann=7,-1,0
  4290.2    0.05       0  4296.7    0.16       0  4623.8    0.12       0
  4988.0    0.07       0  4994.0    0.12       0  5140.2    0.16       0
  5520.3    0.12       0
Bank Sta=4988,4994
Exp/Cntr=0.3,0.1

Type RM Length L Ch R = 1,243,0,0,0
BEGIN DESCRIPTION:
UNT 092 IN UKCR 1.0
END DESCRIPTION:
XS GIS Cut Line= 5
      3637467.77     10583198.84      3636894.81     10582924.52
      3636703.84     10582955.77      3636568.42     10583153.68
      3636554.57     10583763.06
#Sta/Elev= 30
  4238.8  366.83  4409.0  344.57  4491.8  329.84  4499.6  324.59  4505.2  327.60
  4506.9  326.23  4513.9  320.60  4527.9  320.64  4545.0  325.18  4550.5  320.58
  4567.6  322.29  4573.2  320.07  4590.3  320.87  4635.6  316.01  4791.1  312.07
  4845.2  307.98  4980.6  309.29  4990.8  308.93  4995.9  305.31  4998.7  304.81
  5001.9  305.31  5004.0  308.17  5011.0  308.75  5195.1  309.21  5343.9  316.28
  5463.9  327.30  5483.9  331.90  5576.5  341.61  5669.3  352.46  5916.9  368.31
#Mann=6,-1,0
  4238.8    0.16       0  4506.9    0.12       0  4995.9    0.07       0
  5001.9    0.12       0  5576.5    0.16       0  5669.3    0.12       0
Bank Sta=4995.9,5001.9
Exp/Cntr=0.3,0.1

Chan Stop Cuts=-1