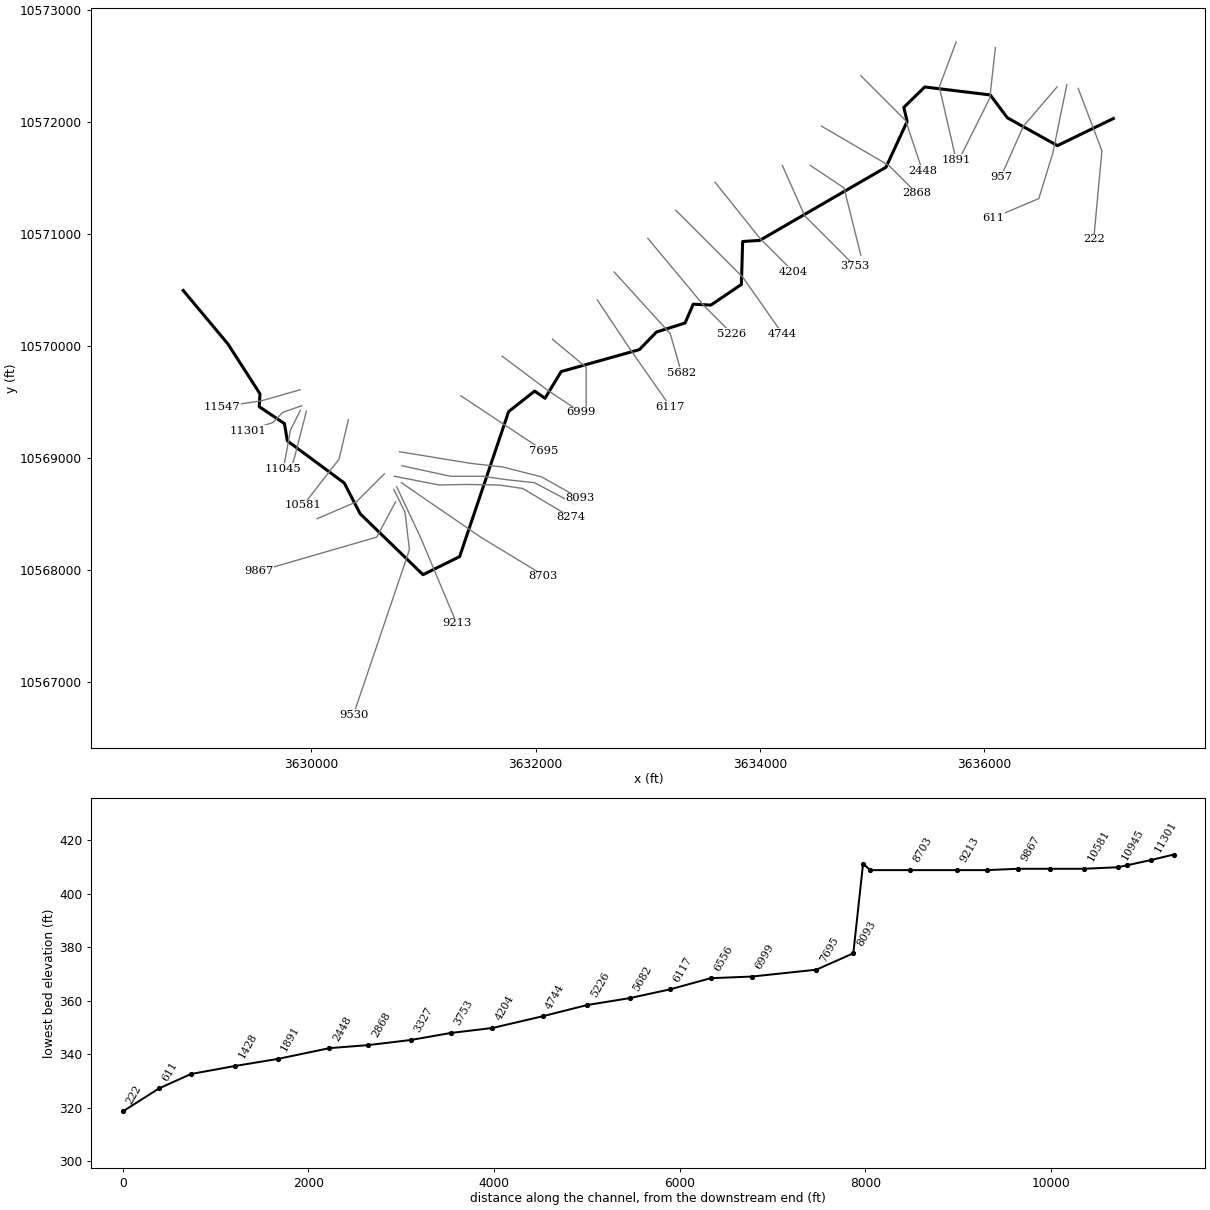
--- UNT 097 IN UKCR.prj (project) ---

Proj Title=UNT 097 IN UKCR Base Level Engineering
Current Plan=p01
Default Exp/Contr=0.3,0.1
English Units
Geom File=g01
Flow File=f01
Plan File=p01
Y Axis Title=Elevation
X Axis Title(PF)=Main Channel Distance
X Axis Title(XS)=Station
BEGIN DESCRIPTION:
UNT 097 IN UKCR
END DESCRIPTION:
DSS Export Rating Curves= 0
DSS Export Rating Curve Sorted= 0
DSS Export Volume Flow Curves= 0
DXF OffsetX= 0
DXF OffsetY= 0
DXF ScaleX= 1
DXF ScaleY= 10

--- UNT 097 IN UKCR.p01 (plan) ---

Plan Title=Multiple Run
Short Identifier=Multiple
Geom File=g01
Flow File=f01
Subcritical Flow
K Sum by GR= 0
Std Step Tol= 0.01
Critical Tol= 0.01
Num of Std Step Trials= 20
Max Error Tol= 0.3
Flow Tol Ratio= 0.001
Split Flow NTrial= 30
Split Flow Tol= 0.02
Split Flow Ratio= 0.02
Log Output Level= 0
Friction Slope Method= 1
Unsteady Friction Slope Method= 2
Unsteady Bridges Friction Slope Method= 1
Parabolic Critical Depth
Global Vel Dist=  1 , 1 , 1
Global Log Level= 0
CheckData=True
Encroach Param= -1, 0, 0, 0
BEGIN DESCRIPTION:
Multiple Run
END DESCRIPTION:

--- UNT 097 IN UKCR.f01 (steady flow) ---

Flow Title=Multiple
Program Version=4.10
Number of Profiles= 7
Profile Names=10-year,25-year,50-year,1pct_min,100-year,1pct_plu,500-year
River Rch & RM=UNT 097 IN UKCR,Reach-1         ,11547
     370     477     561     484     654     885     884
River Rch & RM=UNT 097 IN UKCR,Reach-1         ,9213
    1215    1692    2092    1889    2555    3455    3795
Boundary for River Rch & Prof#=UNT 097 IN UKCR,Reach-1         , 1
Up Type= 0
Dn Type= 3
Dn Slope=0.0067
Boundary for River Rch & Prof#=UNT 097 IN UKCR,Reach-1         , 2
Up Type= 0
Dn Type= 3
Dn Slope=0.0067
Boundary for River Rch & Prof#=UNT 097 IN UKCR,Reach-1         , 3
Up Type= 0
Dn Type= 3
Dn Slope=0.0067
Boundary for River Rch & Prof#=UNT 097 IN UKCR,Reach-1         , 4
Up Type= 0
Dn Type= 3
Dn Slope=0.0067
Boundary for River Rch & Prof#=UNT 097 IN UKCR,Reach-1         , 5
Up Type= 0
Dn Type= 3
Dn Slope=0.0067
Boundary for River Rch & Prof#=UNT 097 IN UKCR,Reach-1         , 6
Up Type= 0
Dn Type= 3
Dn Slope=0.0067
Boundary for River Rch & Prof#=UNT 097 IN UKCR,Reach-1         , 7
Up Type= 0
Dn Type= 3
Dn Slope=0.0067
DSS Import GetInterval= 0
DSS Import GetPeak= 0
DSS Import FillOption= 0

--- UNT 097 IN UKCR.g01 (geometry) ---

Geom Title=Existing Conditions
Program Version=4.10

River Reach=UNT 097 IN UKCR ,Reach-1
Reach XY= 30
      3628856.21     10570494.91      3629254.28     10570018.69
      3629540.52     10569574.03      3629534.01     10569459.01
      3629758.75       10569308.      3629784.75       10569154.
      3630291.75       10568779.      3630434.25       10568504.
       3630994.5       10567961.      3631321.25       10568122.
        3631758.       10569415.      3631990.75       10569598.
      3632082.75       10569534.      3632226.75       10569772.
      3632924.25       10569968.      3633077.25       10570125.
      3633331.75       10570205.      3633404.75       10570373.
      3633562.25       10570365.      3633834.25       10570549.
       3633845.5       10570932.       3633998.5       10570942.
      3635123.75       10571594.       3635312.5       10572002.
      3635283.25       10572128.      3635469.75       10572310.
      3636053.75       10572239.       3636206.5       10572035.
       3636653.5       10571787.      3637152.75       10572029.

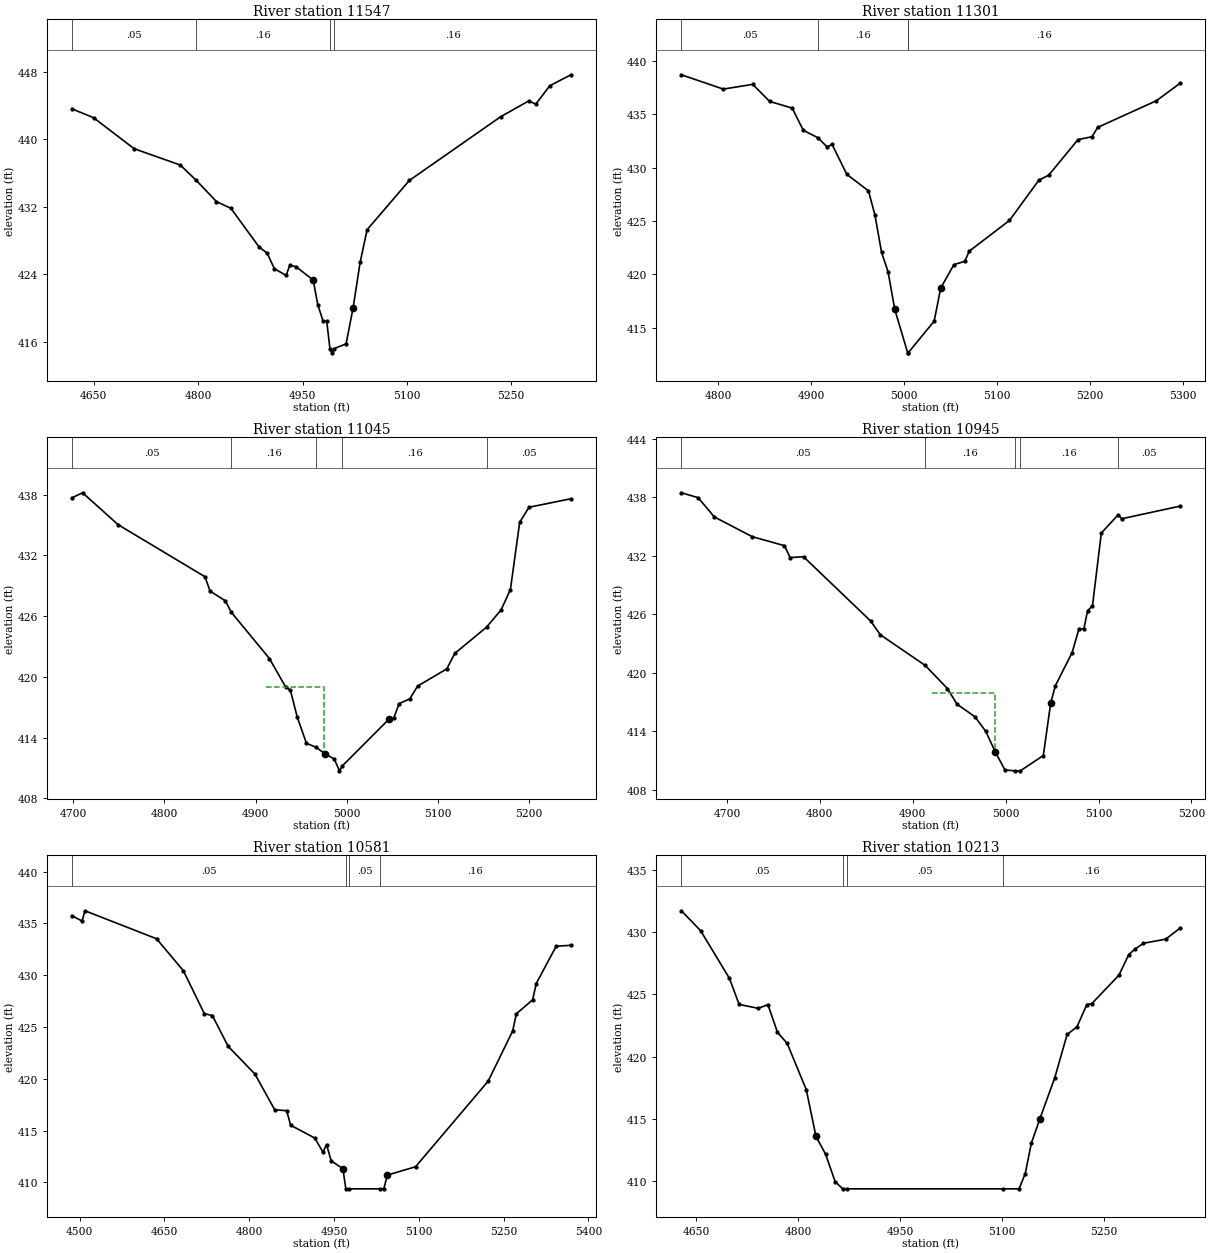
Type RM Length L Ch R = 1 ,11547   ,246,246,246
BEGIN DESCRIPTION:
UNT 097 IN UKCR 24.0
END DESCRIPTION:
XS GIS Cut Line= 3
      3629899.58     10569610.18      3629549.61     10569510.19
      3629199.63     10569460.19
#Sta/Elev= 30
  4618.3  443.62  4649.5  442.57    4708  438.89  4774.3  436.96  4797.3  435.14
  4826.3  432.63  4847.1  431.83  4887.4  427.27  4899.1  426.53  4909.5  424.69
  4926.4  423.89  4931.6  425.07  4940.7  424.92  4965.4  423.33  4971.9  420.43
  4979.7  418.45  4984.8  418.45  4989.4  415.22  4992.1  414.72  4995.4  415.22
  5012.6  415.78  5022.7  420.04  5032.8  425.44  5042.9  429.31  5103.5  435.13
  5234.8  442.68  5275.2  444.55  5285.3  444.17  5305.5  446.35  5335.8  447.65
#Mann= 4 ,-1 , 0
  4618.3     .05       0  4797.3     .16       0  4989.4     .07       0
  4995.4     .16       0
Bank Sta=4965.4,5022.7
XS Rating Curve= 0 ,0
Exp/Cntr=0.3,0.1

Type RM Length L Ch R = 1 ,11301   ,256,256,256
BEGIN DESCRIPTION:
UNT 097 IN UKCR 23.0
END DESCRIPTION:
XS GIS Cut Line= 4
       3629912.1     10569467.24      3629743.75     10569408.23
      3629655.21     10569317.95      3629434.99     10569245.12
#Sta/Elev= 30
  4760.5  438.69  4805.5  437.35  4837.3  437.79  4855.3   436.2  4879.7  435.57
  4891.6  433.49  4907.4  432.79  4917.3  431.93  4922.6  432.17  4938.4  429.37
  4961.7  427.82  4968.7  425.55  4975.8  422.06  4982.8  420.24    4990  416.72
  5003.9  412.65  5004.4  412.65  5032.4  415.62  5039.4  418.71  5053.6  420.91
  5065.3  421.22  5070.1  422.17  5113.4  425.05    5145  428.82  5155.5  429.28
  5187.1  432.62  5202.2  432.89  5208.2  433.76  5271.4  436.26  5297.3  437.92
#Mann= 4 ,-1 , 0
  4760.5     .05       0  4907.4     .16       0  5003.9     .07       0
  5004.4     .16       0
Bank Sta=4990,5039.4
XS Rating Curve= 0 ,0
Exp/Cntr=0.3,0.1

Type RM Length L Ch R = 1 ,11045   ,100,100,100
BEGIN DESCRIPTION:
Mapping XS ec7aa2c2
END DESCRIPTION:
XS GIS Cut Line= 4
        3629900.     10569425.58      3629811.46      10569248.5
      3629781.94     10569081.84      3629749.01     10568905.02
#Sta/Elev= 30
  4698.5  437.67  4710.3  438.17  4749.3  435.02  4844.5  429.88  4850.1  428.46
  4866.9   427.5  4873.3  426.38  4915.1  421.81    4933  418.99  4938.1  418.69
  4945.5  416.07  4955.7  413.44  4965.9  413.06    4976  412.41  4986.2  411.89
  4991.9  410.72  4995.2  411.22  5046.2  415.82  5051.3  415.89  5057.3  417.36
  5069.1  417.83  5077.6  419.09  5109.5  420.78  5118.3  422.31  5153.1   424.9
  5169.1  426.61  5179.3  428.61  5189.5  435.26  5199.7  436.74  5245.6  437.58
#Mann= 5 ,-1 , 0
  4698.5     .05       0  4873.3     .16       0  4965.9     .07       0
  4995.2     .16       0  5153.1     .05       0
#XS Ineff= 1 ,-1
 4911.42 4974.66  419.01
Permanent Ineff=
       F
Bank Sta=4976,5046.2
XS Rating Curve= 0 ,0
Exp/Cntr=0.3,0.1

Type RM Length L Ch R = 1 ,10945   ,364,364,364
BEGIN DESCRIPTION:
UNT 097 IN UKCR 22.0
END DESCRIPTION:
XS GIS Cut Line= 3
      3629953.95      10569417.6      3629847.18     10569000.94
      3629813.32     10568899.36
#Sta/Elev= 30
    4651  438.46    4669  437.96  4686.5  435.98  4727.3  433.96  4761.9  433.04
  4768.1  431.82  4782.5   431.9  4854.9   425.3  4865.1  423.91  4913.5  420.76
  4937.4  418.39  4947.7  416.79  4966.9  415.51  4978.7     414    4989  411.87
  4999.3  410.05  5009.8  409.96  5015.8  409.96  5040.6  411.53  5048.5  416.91
  5053.6   418.7  5071.6  422.08  5078.9  424.51  5084.2  424.51  5088.2  426.36
  5093.5  426.88    5103  434.33  5121.1   436.2  5125.1   435.8  5188.2   437.1
#Mann= 5 ,-1 , 0
    4651     .05       0  4913.5     .16       0  5009.8     .07       0
  5015.8     .16       0  5121.1     .05       0
#XS Ineff= 1 ,-1
 4921.14  4988.3417.9264
Permanent Ineff=
       F
Bank Sta=4989,5048.5
XS Rating Curve= 0 ,0
Exp/Cntr=0.3,0.1

Type RM Length L Ch R = 1 ,10581   ,368,368,368
BEGIN DESCRIPTION:
Mapping XS df98c42f
END DESCRIPTION:
XS GIS Cut Line= 3
      3630328.95     10569342.11      3630245.61     10568990.52
      3629925.28     10568579.04
#Sta/Elev= 30
  4486.3  435.74  4504.4  435.22  4509.6  436.21  4636.2  433.51  4683.6  430.43
  4720.7  426.29  4734.9   426.1  4762.9  423.13  4810.3  420.45  4845.2  417.01
  4866.3  416.92  4873.4  415.52  4916.1  414.28  4930.5  412.92  4936.9  413.65
    4945  412.09  4965.8  411.32    4971  409.38    4977  409.38  5031.2  409.38
  5038.1  409.38  5044.6  410.71  5094.3  411.51  5222.8  419.77  5266.2  424.62
  5272.6  426.27  5301.5  427.62  5307.8  429.19  5343.1  432.79  5369.1  432.88
#Mann= 4 ,-1 , 0
  4486.3     .05       0    4971    .033       0    4977     .05       0
  5031.2     .16       0
Bank Sta=4965.8,5044.6
XS Rating Curve= 0 ,0
Exp/Cntr=0.3,0.1

Type RM Length L Ch R = 1 ,10213   ,346,346,346
BEGIN DESCRIPTION:
UNT 097 IN UKCR 21.0
END DESCRIPTION:
XS GIS Cut Line= 3
      3630649.61     10568860.19      3630399.61     10568610.19
      3630049.65      10568460.2
#Sta/Elev= 30
  4628.3  431.72  4656.6  430.12    4699  426.29  4713.2   424.2  4741.4  423.88
  4755.6  424.18  4769.7  421.95  4783.9  421.07  4812.1  417.34  4826.3  413.59
  4840.4  412.17  4854.6  409.95  4865.7  409.38  4871.7  409.38  5101.5  409.38
  5125.1  409.38  5134.2   410.6  5143.2  413.05  5155.9  415.03  5177.7  418.31
  5195.8  421.78  5210.3  422.39  5224.8  424.18  5232.1  424.26    5272  426.54
  5286.5   428.2  5295.6  428.64  5308.2  429.11  5340.9  429.44  5362.6  430.35
#Mann= 4 ,-1 , 0
  4628.3     .05       0  4865.7    .033       0  4871.7     .05       0
  5101.5     .16       0
Bank Sta=4826.3,5155.9
XS Rating Curve= 0 ,0
Exp/Cntr=0.3,0.1

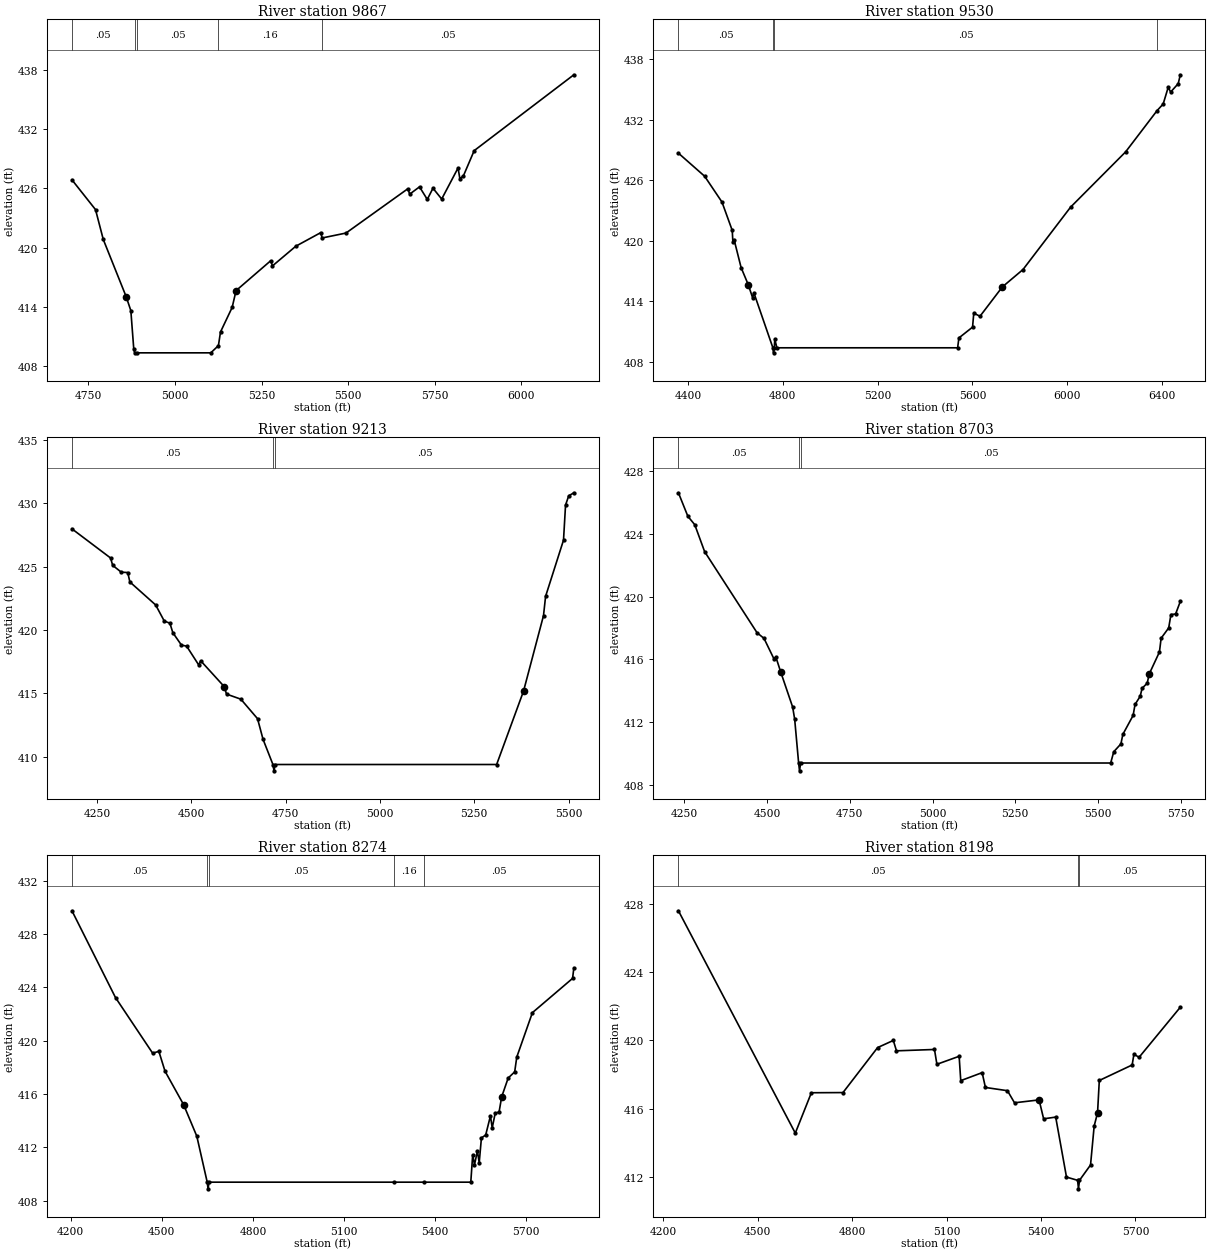
Type RM Length L Ch R = 1 ,9867    ,337,337,337
BEGIN DESCRIPTION:
UNT 097 IN UKCR 20.0
END DESCRIPTION:
XS GIS Cut Line= 3
      3630749.62     10568610.21       3630582.5     10568295.91
      3629533.37     10567992.45
#Sta/Elev= 30
    4703  426.87    4771  423.86  4793.4  420.84  4859.3  415.07  4872.9  413.65
  4881.3  409.79    4884  409.38    4890  409.38  5103.6  409.38  5125.6  410.11
  5131.6  411.49  5165.2  413.97  5176.5  415.67  5276.4  418.69  5281.6  418.17
  5348.9  420.16  5421.3  421.54  5424.5  420.99  5493.7  421.49  5672.2  425.97
  5677.4  425.42  5705.8  426.16  5728.2  424.89  5744.6  426.02  5769.8  424.93
    5817  428.07  5822.2  426.99  5832.3  427.26  5863.5  429.82  6151.1  437.49
#Mann= 5 ,-1 , 0
    4703     .05       0    4884    .033       0    4890     .05       0
  5125.6     .16       0  5424.5     .05       0
Bank Sta=4859.3,5176.5
XS Rating Curve= 0 ,0
Exp/Cntr=0.3,0.1

Type RM Length L Ch R = 1 ,9530    ,317,317,317
BEGIN DESCRIPTION:
Mapping XS 9e6dfaa7
END DESCRIPTION:
XS GIS Cut Line= 4
       3630734.4     10568721.27      3630834.23     10568517.27
       3630873.3     10568183.07      3630374.17     10566711.72
#Sta/Elev= 30
  4359.4   428.7    4470  426.41  4543.1  423.85  4586.5  421.03  4589.2  419.85
  4594.2  420.12  4623.9  417.34  4654.1  415.64  4672.5  414.34  4677.6  414.85
  4757.9  409.38  4760.7  408.88  4763.9  409.38  4765.9  410.23  4774.9  409.38
  5537.3  409.38  5542.6  410.36  5600.2  411.43  5605.4  412.82  5631.6  412.51
  5725.8  415.42  5813.1  417.15  6013.7  423.34    6246  428.83  6378.9  432.93
  6404.4  433.58  6425.5  435.23  6436.1  434.77  6467.8   435.6  6476.7  436.48
#Mann= 4 ,-1 , 0
  4359.4     .05       0  4757.9    .033       0  4763.9     .05       0
  6378.9     .16       0
Bank Sta=4654.1,5725.8
XS Rating Curve= 0 ,0
Exp/Cntr=0.3,0.1

Type RM Length L Ch R = 1 ,9213    ,510,510,510
BEGIN DESCRIPTION:
UNT 097 IN UKCR 19.0
END DESCRIPTION:
XS GIS Cut Line= 3
      3630759.67     10568744.96      3630973.22     10568291.82
      3631294.31     10567527.68
#Sta/Elev= 30
    4184  427.99  4286.3  425.69  4291.9  425.11  4314.6  424.57  4331.9  424.54
  4337.4   423.8  4405.8  421.98  4428.6  420.71  4443.5  420.54  4451.3  419.79
  4474.1  418.81  4487.8  418.73  4519.7  417.25  4525.2  417.57  4587.2  415.54
  4593.6  414.94  4631.5  414.54  4675.7     413  4690.3  411.37  4716.5  409.38
  4719.3  408.88  4722.5  409.38  5309.2  409.38  5380.5  415.18  5433.4  421.14
  5438.9  422.66  5486.4   427.1  5491.8  429.87  5500.2   430.6  5513.8  430.84
#Mann= 3 ,-1 , 0
    4184     .05       0  4716.5    .033       0  4722.5     .05       0
Bank Sta=4587.2,5380.5
XS Rating Curve= 0 ,0
Exp/Cntr=0.3,0.1

Type RM Length L Ch R = 1 ,8703    ,429,429,429
BEGIN DESCRIPTION:
Mapping XS 8f378055
END DESCRIPTION:
XS GIS Cut Line= 4
      3630801.33     10568781.41      3631514.88     10568291.82
      3632023.47     10567983.41      3632065.27     10567945.79
#Sta/Elev= 30
  4232.3  426.64  4260.8  425.14  4281.7   424.6  4311.5  422.88  4469.9   417.7
  4490.9  417.34  4520.7  416.04  4526.7  416.15  4541.6  415.18  4577.5  412.95
  4583.6  412.17  4595.5  409.38  4598.2  408.88  4601.5  409.38  5538.3  409.38
  5547.6   410.1  5569.2   410.6  5575.1  411.21  5606.1  412.42  5611.9  413.12
  5627.4  413.64  5633.2  414.15  5648.7  414.48  5654.6  415.06  5685.6  416.47
  5690.7  417.35  5713.6  418.01  5720.3  418.86  5734.5   418.9  5748.7   419.7
#Mann= 3 ,-1 , 0
  4232.3     .05       0  4595.5    .033       0  4601.5     .05       0
Bank Sta=4541.6,5654.6
XS Rating Curve= 0 ,0
Exp/Cntr=0.3,0.1

Type RM Length L Ch R = 1 ,8274    ,76,76,76
BEGIN DESCRIPTION:
Mapping XS 0c9ed73b
END DESCRIPTION:
XS GIS Cut Line= 6
      3630738.83      10568838.7      3631139.88     10568760.57
      3631379.47     10568765.78      3631676.34     10568760.57
      3631884.68     10568729.32      3632310.87     10568474.65
#Sta/Elev= 30
  4204.1  429.73  4347.5  423.22  4469.8  419.05  4490.2  419.19  4510.5   417.7
  4571.7  415.19  4615.1  412.83  4649.4  409.38  4652.2  408.88  4655.4  409.38
  5262.7  409.38  5363.8  409.38  5517.1  409.38  5523.4  411.44  5529.3  410.69
    5539  411.72  5544.8  410.83  5552.1   412.7  5566.2  412.92  5581.8  414.35
  5587.6  413.45  5597.4  414.54  5610.3  414.65  5618.8  415.78  5640.2  417.19
  5661.6  417.65  5668.5  418.76  5719.9  422.09  5852.2  424.66  5856.4  425.45
#Mann= 5 ,-1 , 0
  4204.1     .05       0  4649.4     .03       0  4655.4     .05       0
  5262.7     .16       0  5363.8     .05       0
Bank Sta=4571.7,5618.8
XS Rating Curve= 0 ,0
Exp/Cntr=0.3,0.1

Type RM Length L Ch R = 1 ,8198    ,105,105,105
BEGIN DESCRIPTION:
UNT 097 IN UKCR 18.0
END DESCRIPTION:
XS GIS Cut Line= 6
      3630806.58     10568932.44      3631238.84      10568838.7
       3631525.3      10568838.7      3631744.05     10568807.45
      3631988.84      10568781.4      3632341.82     10568594.53
#Sta/Elev= 30
  4247.5  427.61    4619  414.56  4670.1  416.93  4770.6  416.94  4880.6  419.58
  4930.6     420  4940.6  419.39  5061.4  419.47  5069.1   418.6  5139.8  419.07
  5144.9  417.64  5212.9  418.11  5223.3  417.24  5293.3  417.05  5315.8  416.34
  5393.9  416.51  5408.3   415.4  5446.7   415.5    5481  411.98  5516.3  411.79
  5519.1  411.29  5522.3  411.79  5557.4  412.69    5569  414.98  5579.7  415.75
  5585.3  417.65  5689.7  418.56  5695.3  419.19  5711.7  419.01  5842.8  421.95
#Mann= 3 ,-1 , 0
  4247.5     .05       0  5516.3     .03       0  5522.3     .05       0
Bank Sta=5393.9,5579.7
XS Rating Curve= 0 ,0
Exp/Cntr=0.3,0.1

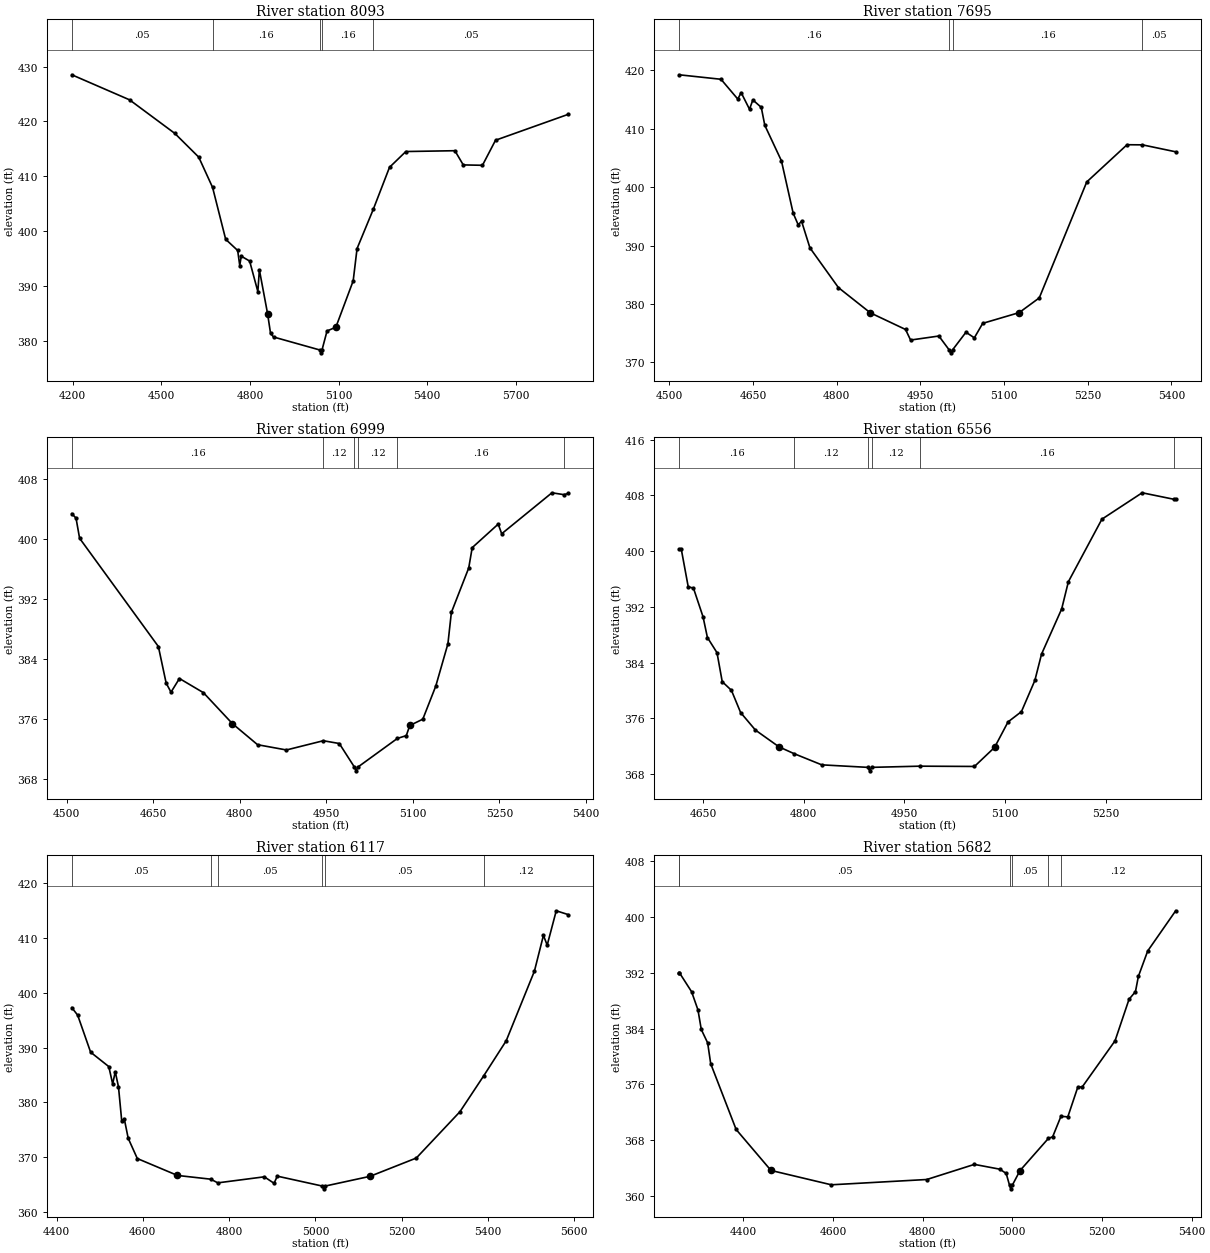
Type RM Length L Ch R = 1 ,8093    ,398,398,398
BEGIN DESCRIPTION:
UNT 097 IN UKCR 17.0
END DESCRIPTION:
XS GIS Cut Line= 5
      3630785.72     10569057.44      3631421.13     10568953.28
      3631702.38     10568922.03      3632051.34     10568833.49
      3632394.85     10568640.91
#Sta/Elev= 30
  4197.3   428.5  4392.7  423.93  4545.8  417.81  4626.8  413.48  4673.7  407.95
    4718  398.49  4758.6  396.45  4765.6  393.71  4770.7  395.41  4799.1  394.52
  4826.9  388.95    4832  392.93  4859.8  384.92  4869.8  381.35  4879.9  380.67
  5037.9  378.28  5040.6  377.78  5043.9  378.28    5061  381.77  5090.9  382.46
  5149.5  390.91  5162.6   396.8  5217.6  403.97  5272.4  411.62  5327.7   414.5
  5493.7  414.65    5522  412.06    5587  411.99  5631.2  416.56    5878   421.3
#Mann= 5 ,-1 , 0
  4197.3     .05       0  4673.7     .16       0  5037.9     .07       0
  5043.9     .16       0  5217.6     .05       0
Bank Sta=4859.8,5090.9
XS Rating Curve= 0 ,0
Exp/Cntr=0.3,0.1

Type RM Length L Ch R = 1 ,7695    ,696,696,696
BEGIN DESCRIPTION:
UNT 097 IN UKCR 16.0
END DESCRIPTION:
XS GIS Cut Line= 2
      3631331.54      10569556.5       3632073.3      10569064.3
#Sta/Elev= 30
  4517.4  419.26  4592.6  418.49  4622.7   415.1  4628.7  416.21  4643.7  413.36
  4649.7  414.95  4664.8  413.68  4671.1  410.61  4700.9  404.53  4721.9  395.58
    4731  393.56    4737  394.18    4752  389.62  4803.1  382.81  4860.3  378.49
  4923.4  375.64  4932.4  373.83  4983.1  374.52  5001.6  372.14  5004.4  371.64
  5007.6  372.14  5031.7  375.17  5046.7  374.21  5061.7  376.69  5127.1  378.53
  5163.1  381.05  5248.2  400.91  5320.4  407.28    5348  407.26  5407.6  406.07
#Mann= 4 ,-1 , 0
  4517.4     .16       0  5001.6     .07       0  5007.6     .16       0
    5348     .05       0
Bank Sta=4860.3,5127.1
XS Rating Curve= 0 ,0
Exp/Cntr=0.3,0.1

Type RM Length L Ch R = 1 ,6999    ,443,443,443
BEGIN DESCRIPTION:
UNT 097 IN UKCR 15.0
END DESCRIPTION:
XS GIS Cut Line= 3
      3631699.61     10569910.19      3632099.61     10569610.19
      3632399.65     10569410.16
#Sta/Elev= 30
    4509  403.33  4516.3  402.73  4522.5  400.05    4659  385.63  4672.5  380.75
  4680.9  379.55  4695.5  381.37  4737.1  379.48  4787.1  375.37  4830.9  372.55
  4880.9  371.85  4944.8  373.08  4972.5  372.71  4998.7  369.57  5001.5  369.07
  5004.7  369.57  5073.2  373.39  5088.6  373.76  5094.6  375.11  5117.2  375.95
  5139.7  380.36  5160.7  385.99  5166.7  390.17  5196.8   396.1  5202.8   398.8
  5247.9  401.94  5253.9  400.65    5341  406.11  5361.7  405.86  5369.6  406.02
#Mann= 6 ,-1 , 0
    4509     .16       0  4944.8     .12       0  4998.7     .07       0
  5004.7     .12       0  5073.2     .16       0  5361.7     .05       0
Bank Sta=4787.1,5094.6
XS Rating Curve= 0 ,0
Exp/Cntr=0.3,0.1

Type RM Length L Ch R = 1 ,6556    ,439,439,439
BEGIN DESCRIPTION:
UNT 097 IN UKCR 14.0
END DESCRIPTION:
XS GIS Cut Line= 3
       3632149.6     10570060.19      3632449.61     10569810.19
      3632449.61     10569460.21
#Sta/Elev= 30
  4614.1   400.3  4617.4   400.3  4627.8  394.88  4635.6  394.69  4649.9  390.57
  4656.4   387.6  4670.7  385.42  4678.5  381.26  4692.2  380.02  4705.9  376.83
    4728  374.31  4763.2   371.9  4785.3  370.94  4826.9  369.32  4895.5  368.96
  4898.3  368.46  4901.5  368.96  4972.9  369.13  5054.6  369.09  5084.6  371.83
  5104.6  375.48  5124.6  376.96  5144.6  381.43  5154.6  385.22  5184.6   391.7
  5194.6  395.61  5244.6  404.59  5304.6  408.38  5351.8  407.45  5354.6  407.43
#Mann= 6 ,-1 , 0
  4614.1     .16       0  4785.3     .12       0  4895.5     .07       0
  4901.5     .12       0  4972.9     .16       0  5351.8     .05       0
Bank Sta=4763.2,5084.6
XS Rating Curve= 0 ,0
Exp/Cntr=0.3,0.1

Type RM Length L Ch R = 1 ,6117    ,435,435,435
BEGIN DESCRIPTION:
UNT 097 IN UKCR 13.0
END DESCRIPTION:
XS GIS Cut Line= 3
      3632549.59     10570410.21      3632849.61     10569960.19
      3633199.61     10569460.18
#Sta/Elev= 30
  4435.3  397.28  4448.9   395.9  4478.9  389.16    4521  386.54    4530  383.38
    4536   385.6  4543.5  382.84    4551  376.64    4557  376.98    4566  373.48
  4587.1  369.79  4680.2  366.71  4757.2  366.03  4773.7  365.36  4881.5  366.46
  4904.1  365.28  4911.6  366.58  5016.3  364.77  5019.1  364.27  5022.3  364.77
  5126.6  366.55  5233.8  369.88    5335  378.32  5390.5  384.91  5442.2  391.24
  5507.6  403.93  5528.5  410.44  5537.2  408.66  5558.2  414.92  5586.5  414.21
#Mann= 6 ,-1 , 0
  4435.3     .05       0  4757.2     .16       0  4773.7     .05       0
  5016.3     .03       0  5022.3     .05       0  5390.5     .12       0
Bank Sta=4680.2,5126.6
XS Rating Curve= 0 ,0
Exp/Cntr=0.3,0.1

Type RM Length L Ch R = 1 ,5682    ,456,456,456
BEGIN DESCRIPTION:
UNT 097 IN UKCR 12.0
END DESCRIPTION:
XS GIS Cut Line= 3
      3632699.63     10570660.16      3633199.61     10570110.19
      3633299.62     10569760.16
#Sta/Elev= 30
    4257  392.02  4257.8  392.02    4285  389.29  4299.2  386.68  4306.6  383.87
  4320.8  381.95  4327.6  378.96  4384.3  369.52    4462  363.64  4596.5  361.58
  4809.4  362.34  4915.5  364.51  4972.2  363.82  4986.4  363.21  4993.9   361.5
  4996.6     361  4999.9   361.5  5017.2  363.62  5080.5  368.24    5090  368.47
  5108.5  371.41  5123.8  371.33  5145.9  375.57  5156.3  375.66  5229.1  382.25
  5260.3  388.21  5274.6   389.3  5281.1  391.49  5301.9  395.14  5364.3  400.91
#Mann= 6 ,-1 , 0
    4257     .16       0  4257.8     .05       0  4993.9     .03       0
  4999.9     .05       0  5080.5     .16       0  5108.5     .12       0
Bank Sta=4462,5017.2
XS Rating Curve= 0 ,0
Exp/Cntr=0.3,0.1

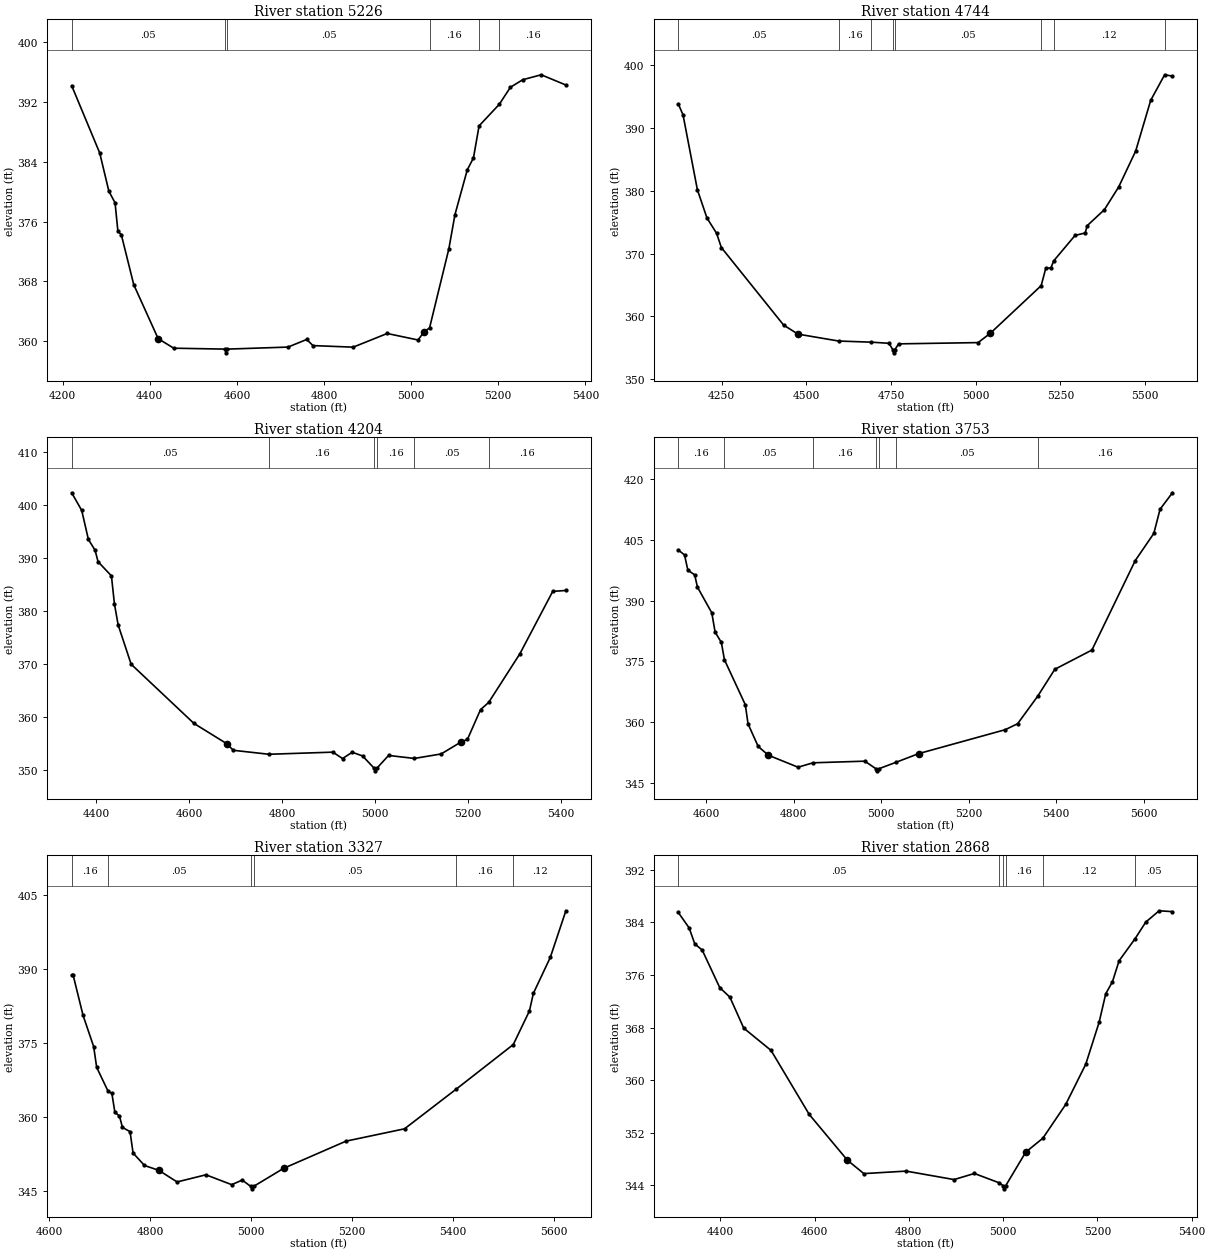
Type RM Length L Ch R = 1 ,5226    ,482,482,482
BEGIN DESCRIPTION:
UNT 097 IN UKCR 11.0
END DESCRIPTION:
XS GIS Cut Line= 3
      3632999.61     10570960.19      3633499.61     10570360.19
      3633749.62     10570110.17
#Sta/Elev= 30
  4220.7  394.18  4285.1  385.17    4306  380.07  4320.3   378.5  4326.8   374.7
  4334.6  374.25  4363.2  367.55  4419.2  360.33    4455  359.05  4572.4  358.93
  4575.2  358.43  4578.4  358.93  4717.3   359.2  4760.3  360.22  4774.6   359.4
    4867  359.19  4945.1  361.02  5015.9  360.15    5030  361.26  5042.3  361.76
  5086.6  372.34  5100.7  376.94    5129  382.93  5143.1  384.51    5156   388.8
  5202.3  391.68    5228  393.97  5256.3  394.98  5298.7  395.64  5355.3  394.27
#Mann= 6 ,-1 , 0
  4220.7     .05       0  4572.4     .03       0  4578.4     .05       0
  5042.3     .16       0    5156     .12       0  5202.3     .16       0
Bank Sta=4419.2,5030
XS Rating Curve= 0 ,0
Exp/Cntr=0.3,0.1

Type RM Length L Ch R = 1 ,4744    ,540,540,540
BEGIN DESCRIPTION:
UNT 097 IN UKCR 10.0
END DESCRIPTION:
XS GIS Cut Line= 3
      3633249.63     10571210.17      3633849.61     10570610.19
      3634199.59     10570110.21
#Sta/Elev= 30
  4121.7  393.87  4135.8  392.12  4178.2  380.19  4206.5  375.68  4234.8  373.26
    4249  370.98  4432.8  358.63  4475.2  357.19  4595.1  356.09  4691.4  355.91
  4743.9  355.73  4755.1  354.71  4757.8  354.21  4761.1  354.71  4772.2  355.64
  5006.8  355.84    5043  357.33    5193  364.91  5206.9  367.73  5221.7  367.71
    5230  368.86  5293.2  372.92  5322.9   373.3    5329  374.47  5379.6  377.01
  5421.8  380.63    5472  386.35  5516.4  394.44  5557.5   398.5  5580.5  398.29
#Mann= 8 ,-1 , 0
  4121.7     .05       0  4595.1     .16       0  4691.4     .05       0
  4755.1     .03       0  4761.1     .05       0    5193     .16       0
    5230     .12       0  5557.5     .05       0
Bank Sta=4475.2,5043
XS Rating Curve= 0 ,0
Exp/Cntr=0.3,0.1

Type RM Length L Ch R = 1 ,4204    ,451,451,451
BEGIN DESCRIPTION:
UNT 097 IN UKCR 9.0
END DESCRIPTION:
XS GIS Cut Line= 3
       3633599.6     10571460.19      3633999.61     10570960.19
      3634299.62     10570660.18
#Sta/Elev= 30
  4346.8  402.35  4368.4  399.02  4382.8  393.53  4397.2   391.5  4403.6  389.33
  4432.4  386.66  4438.9  381.35  4446.9  377.39  4474.9  369.97  4610.1   358.8
  4680.6  354.98    4695  353.72  4771.7  352.97  4909.5  353.37  4930.3  352.16
  4951.1  353.35  4973.5  352.65  4998.3  350.34    5001  349.84  5004.3  350.34
  5029.5  352.75  5084.9  352.18  5142.7  353.03  5185.1  355.26  5199.3  355.77
  5227.5  361.39  5245.1  362.76  5312.4  371.96  5383.1  383.73  5411.4   383.9
#Mann= 6 ,-1 , 0
  4346.8     .05       0  4771.7     .16       0  4998.3     .07       0
  5004.3     .16       0  5084.9     .05       0  5245.1     .16       0
Bank Sta=4680.6,5185.1
XS Rating Curve= 0 ,0
Exp/Cntr=0.3,0.1

Type RM Length L Ch R = 1 ,3753    ,426,426,426
BEGIN DESCRIPTION:
UNT 097 IN UKCR 8.0
END DESCRIPTION:
XS GIS Cut Line= 3
       3634199.6     10571610.22      3634399.61     10571160.19
      3634849.63     10570710.17
#Sta/Elev= 30
  4536.4  402.56  4550.8  401.32  4558.3  397.57    4574  396.39  4580.2  393.39
    4613  387.02  4620.6  382.26  4634.9  379.69  4641.9  375.42  4689.6   364.3
  4695.8  359.58    4719  353.99  4742.3  351.82    4810  348.86  4844.5  349.95
  4962.5  350.35  4988.3  348.46    4991  347.96  4994.3  348.46  5033.1  350.04
  5085.4  352.21  5283.4  358.13  5311.7  359.61  5357.6  366.42  5396.6  373.06
  5481.4  377.82  5580.4  399.94  5622.8  406.65    5637  412.62  5665.3  416.69
#Mann= 7 ,-1 , 0
  4536.4     .16       0  4641.9     .05       0  4844.5     .16       0
  4988.3     .07       0  4994.3     .16       0  5033.1     .05       0
  5357.6     .16       0
Bank Sta=4742.3,5085.4
XS Rating Curve= 0 ,0
Exp/Cntr=0.3,0.1

Type RM Length L Ch R = 1 ,3327    ,459,459,459
BEGIN DESCRIPTION:
UNT 097 IN UKCR 7.0
END DESCRIPTION:
XS GIS Cut Line= 3
      3634449.64     10571610.17      3634749.61     10571410.19
      3634899.61     10570810.17
#Sta/Elev= 30
  4644.7  388.68  4647.7  388.68  4667.2  380.57  4688.2  374.24  4694.2  370.02
  4716.8  365.16  4724.3  364.73  4730.3  360.88  4739.3  360.15  4745.3  357.82
  4760.3  356.97  4766.3  352.63  4788.9   350.1  4817.4  349.11  4853.5  346.76
  4910.6  348.21  4961.6  346.21  4982.7  347.14  4999.2  345.86    5002  345.36
  5005.2  345.86  5064.5  349.52  5188.2  355.04  5304.1  357.54  5406.9  365.63
  5519.5  374.64  5551.5  381.46  5559.3  385.03  5592.8  392.32  5623.7  401.79
#Mann= 6 ,-1 , 0
  4644.7     .16       0  4716.8     .05       0  4999.2     .03       0
  5005.2     .05       0  5406.9     .16       0  5519.5     .12       0
Bank Sta=4817.4,5064.5
XS Rating Curve= 0 ,0
Exp/Cntr=0.3,0.1

Type RM Length L Ch R = 1 ,2868    ,420,420,420
BEGIN DESCRIPTION:
UNT 097 IN UKCR 6.0
END DESCRIPTION:
XS GIS Cut Line= 3
      3634549.64     10571960.17      3635149.61     10571610.19
      3635399.58     10571360.21
#Sta/Elev= 30
    4311  385.53  4334.1  383.17  4346.1  380.73  4361.8   379.8    4399  374.08
  4420.5  372.63  4449.9  367.91  4507.8  364.52  4588.8  354.77  4669.8   347.8
  4704.6  345.76  4794.3  346.14    4896  344.85    4939  345.78  4991.9  344.35
  4999.7  343.94  5002.4  343.44  5005.7  343.94    5048  349.03  5084.3  351.15
  5132.9  356.31  5175.3  362.42  5203.6   368.8  5217.7  373.15  5231.9  374.98
    5246  378.17  5279.7  381.51  5302.6  384.06  5330.9  385.78  5359.1  385.65
#Mann= 6 ,-1 , 0
    4311     .05       0  4991.9     .16       0  4999.7     .07       0
  5005.7     .16       0  5084.3     .12       0  5279.7     .05       0
Bank Sta=4669.8,5048
XS Rating Curve= 0 ,0
Exp/Cntr=0.3,0.1

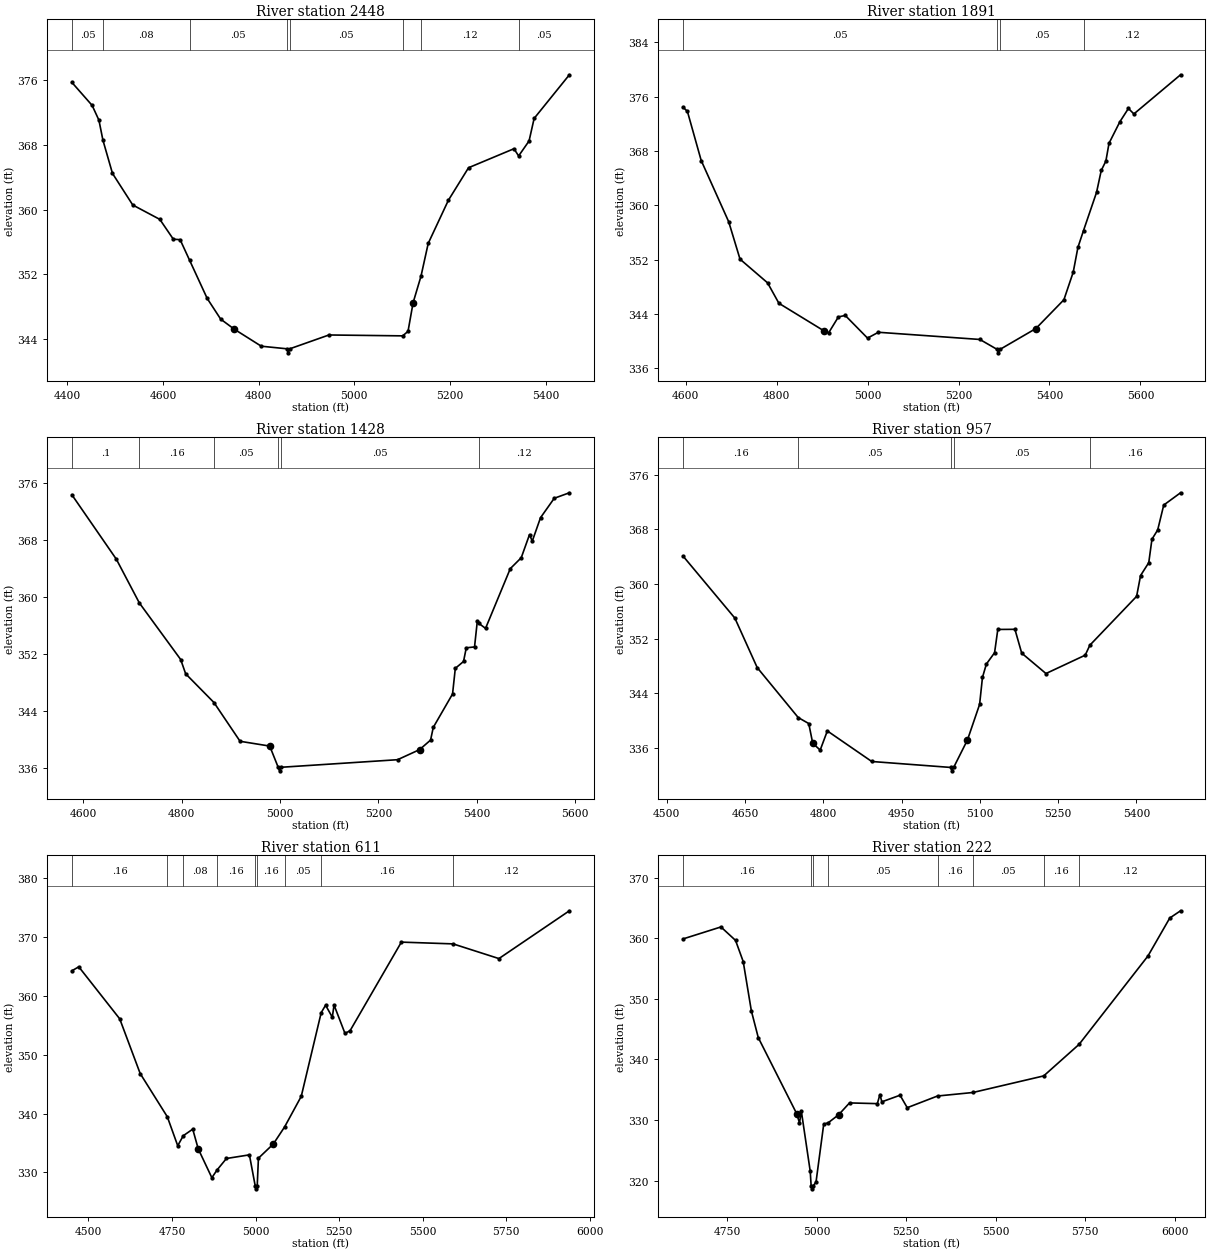
Type RM Length L Ch R = 1 ,2448    ,557,557,557
BEGIN DESCRIPTION:
UNT 097 IN UKCR 5.0
END DESCRIPTION:
XS GIS Cut Line= 3
       3634899.6      10572410.2      3635299.61     10572010.19
       3635449.6     10571560.23
#Sta/Elev= 30
  4409.6  375.76    4452  372.91  4466.2  371.08  4474.5  368.62  4494.5   364.5
  4536.9  360.59  4593.5  358.81  4621.7  356.36  4635.9   356.3  4655.9  353.73
  4692.5  349.03  4720.7  346.47    4749  345.23  4805.6  343.12  4859.2   342.8
  4861.9   342.3  4865.2   342.8    4947  344.51  5101.1   344.4  5112.3  344.96
  5122.9   348.5  5139.4  351.78  5154.5  355.84  5196.7  361.18  5238.8   365.2
  5333.7  367.55  5343.5  366.66  5365.3  368.51  5375.9   371.3  5449.6   376.7
#Mann= 8 ,-1 , 0
  4409.6     .05       0  4474.5     .08       0  4655.9     .05       0
  4859.2     .03       0  4865.2     .05       0  5101.1     .16       0
  5139.4     .12       0  5343.5     .05       0
Bank Sta=4749,5122.9
XS Rating Curve= 0 ,0
Exp/Cntr=0.3,0.1

Type RM Length L Ch R = 1 ,1891    ,463,463,463
BEGIN DESCRIPTION:
UNT 097 IN UKCR 4.0
END DESCRIPTION:
XS GIS Cut Line= 3
      3635749.59     10572710.15      3635599.61     10572310.19
       3635749.6     10571660.23
#Sta/Elev= 30
    4594  374.45  4603.7  373.82    4634  366.59  4694.5  357.57  4719.4  352.06
    4780  348.57  4804.9  345.56  4903.7  341.51  4914.4  341.22  4935.7  343.55
  4950.8  343.77  4999.8  340.43  5023.7  341.29  5246.9  340.23    5285  338.76
  5287.7  338.26    5291  338.76  5370.1  341.84  5431.7  346.08  5452.2  350.15
  5462.5  353.79  5474.8  356.27  5503.5   361.9  5513.8  365.12    5524  366.51
  5530.9  369.13  5554.8   372.3  5573.6  374.26  5585.6  373.45  5688.2  379.22
#Mann= 4 ,-1 , 0
    4594     .05       0    5285     .03       0    5291     .05       0
  5474.8     .12       0
Bank Sta=4903.7,5370.1
XS Rating Curve= 0 ,0
Exp/Cntr=0.3,0.1

Type RM Length L Ch R = 1 ,1428    ,471,471,471
BEGIN DESCRIPTION:
UNT 097 IN UKCR 3.0
END DESCRIPTION:
XS GIS Cut Line= 3
      3636099.61     10572660.16      3636049.61     10572210.19
      3635799.59     10571710.15
#Sta/Elev= 30
  4576.6  374.29  4667.1  365.26  4713.8  359.14  4797.9  351.21    4808  349.21
  4865.6  345.18  4918.7  339.75    4979  339.08  4996.2  336.11  4998.9  335.61
  5002.2  336.11    5239  337.17  5283.7  338.58  5306.1  339.92  5311.6   341.7
  5350.8  346.38  5356.4  349.97  5373.1  350.93  5378.7  352.85  5395.5  352.97
  5401.1  356.55  5403.9  356.29  5417.9  355.57  5468.2  363.94  5490.5  365.47
  5507.3  368.71  5512.9  367.79  5529.7  371.08  5557.6   373.8  5588.4  374.57
#Mann= 6 ,-1 , 0
  4576.6      .1       0  4713.8     .16       0  4865.6     .05       0
  4996.2     .04       0  5002.2     .05       0  5403.9     .12       0
Bank Sta=4979,5283.7
XS Rating Curve= 0 ,0
Exp/Cntr=0.3,0.1

Type RM Length L Ch R = 1 ,957     ,346,346,346
BEGIN DESCRIPTION:
UNT 097 IN UKCR 2.0
END DESCRIPTION:
XS GIS Cut Line= 3
      3636649.63     10572310.22      3636349.61     10571960.19
      3636149.59     10571510.15
#Sta/Elev= 30
  4531.1  364.11  4630.5  355.01  4673.3  347.76  4751.9  340.44  4772.1  339.56
  4779.7  336.67    4794  335.67  4807.7  338.48  4892.8     334  5043.8  333.13
  5046.6  332.63  5049.8  333.13  5076.2  337.15  5099.5  342.36    5105  346.32
  5112.5  348.28  5128.2  349.94  5134.4  353.35  5167.2  353.37  5180.2  349.88
  5226.7  346.89  5301.9  349.58  5310.8  351.04  5400.4   358.2    5408  361.25
  5423.7  363.14  5429.8  366.57  5440.8  367.93  5452.4  371.58  5484.6  373.38
#Mann= 5 ,-1 , 0
  4531.1     .16       0  4751.9     .05       0  5043.8     .03       0
  5049.8     .05       0  5310.8     .16       0
Bank Sta=4779.7,5076.2
XS Rating Curve= 0 ,0
Exp/Cntr=0.3,0.1

Type RM Length L Ch R = 1 ,611     ,389,389,389
BEGIN DESCRIPTION:
Mapping XS 593e10af
END DESCRIPTION:
XS GIS Cut Line= 4
      3636737.07     10572330.45      3636612.06     10571721.05
      3636487.06      10571314.8      3636080.77      10571142.9
#Sta/Elev= 30
  4450.4   364.3  4471.1  364.98  4593.6  356.13  4654.8  346.83    4736  339.47
  4767.1  334.55  4783.6  336.25    4812  337.37  4828.4  334.02  4869.2  329.11
  4884.5  330.41  4912.8  332.38  4981.5     333  4998.9  327.72  5001.7  327.22
  5004.9  327.72  5008.5  332.43    5053  334.84  5086.8  337.75  5136.6  342.95
  5196.3  357.19  5209.4  358.45  5229.5  356.41  5234.7  358.48  5267.4  353.66
  5282.6  354.11  5436.1  369.18  5590.7  368.88  5727.9  366.38  5938.7  374.51
#Mann= 9 ,-1 , 0
  4450.4     .16       0    4736     .05       0  4783.6     .08       0
  4884.5     .16       0  4998.9     .07       0  5004.9     .16       0
  5086.8     .05       0  5196.3     .16       0  5590.7     .12       0
Bank Sta=4828.4,5053
XS Rating Curve= 0 ,0
Exp/Cntr=0.3,0.1

Type RM Length L Ch R = 1 ,222     ,0,0,0
BEGIN DESCRIPTION:
UNT 097 IN UKCR 1.0
END DESCRIPTION:
XS GIS Cut Line= 3
      3636838.05     10572297.28      3637049.84     10571741.76
      3636976.65     10570950.26
#Sta/Elev= 30
  4627.2   359.9  4733.1  361.88  4773.9  359.66  4795.3  356.17  4818.1  348.01
  4837.4   343.6  4945.2  330.98  4952.4  329.51  4957.8  331.41  4982.5  321.52
    4985  319.13  4987.7  318.63    4991  319.13  4998.7  319.76  5020.1  329.29
  5032.9  329.55  5062.1  330.88  5092.2  332.82  5169.9   332.7  5177.1   334.2
  5182.5     333  5233.3  334.09  5253.4  332.03  5337.9  333.96  5436.8  334.54
  5634.5  337.28  5733.3  342.49  5925.7  357.09  5986.5  363.35  6016.6  364.55
#Mann= 8 ,-1 , 0
  4627.2     .16       0    4985     .07       0    4991     .16       0
  5032.9     .05       0  5337.9     .16       0  5436.8     .05       0
  5634.5     .16       0  5733.3     .12       0
Bank Sta=4945.2,5062.1
XS Rating Curve= 0 ,0
Exp/Cntr=0.3,0.1

Chan Stop Cuts=-1
Use User Specified Reach Order=0
Composite Channel Slope=5