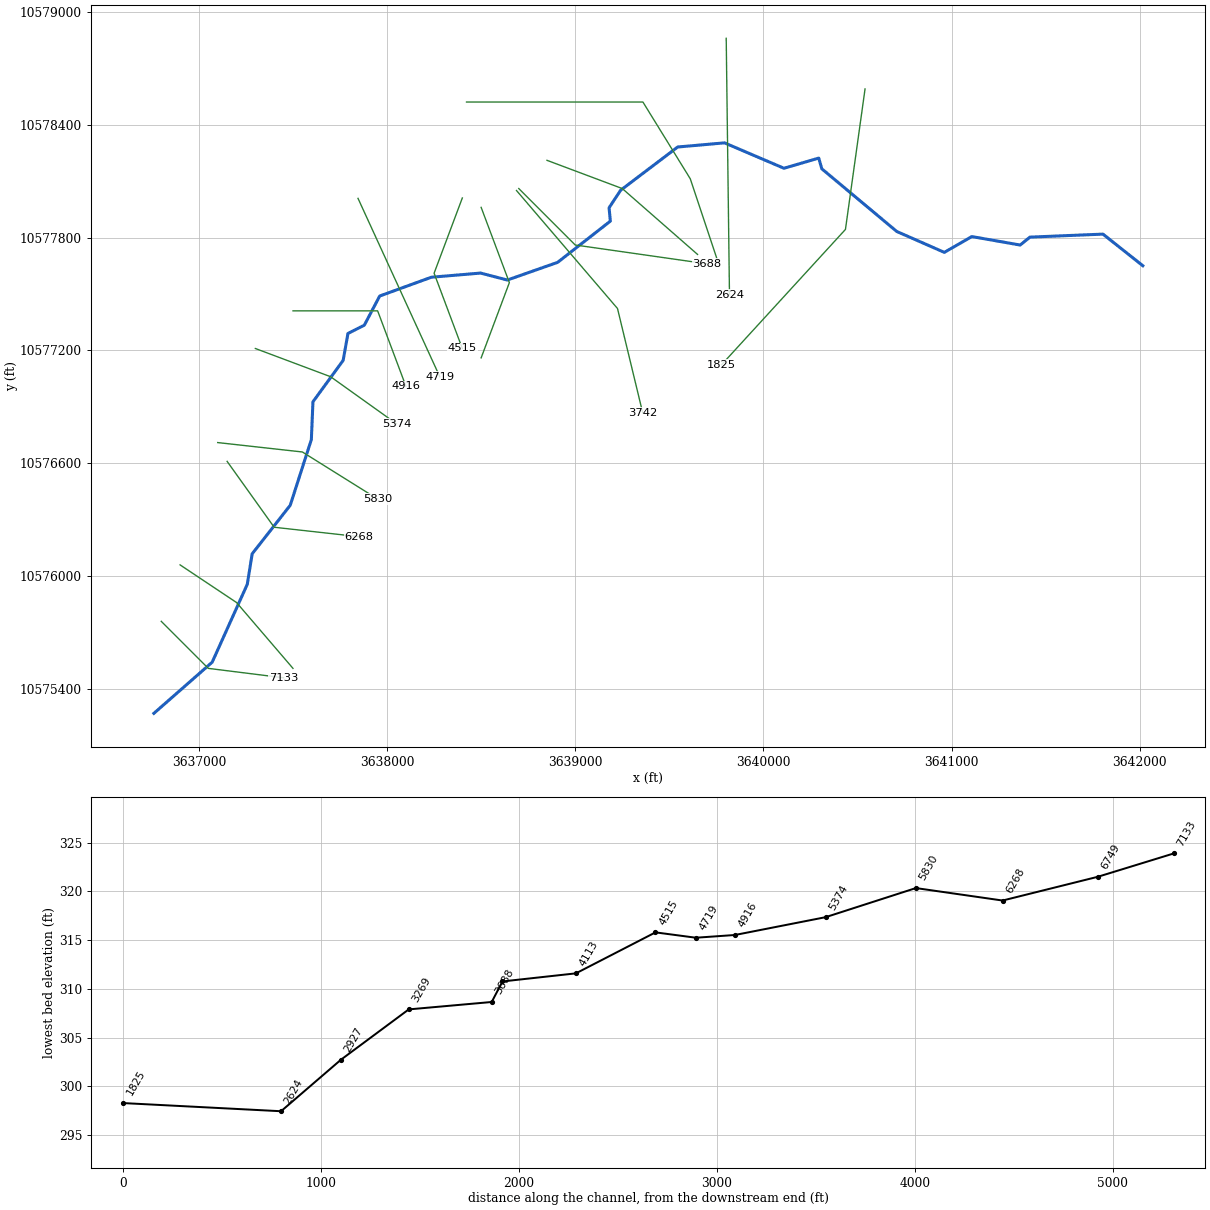
--- UNT 102 IN UKCR.prj (project) ---

Proj Title=UNT 102 IN UKCR Base Level Engineering
Current Plan=p01
Default Exp/Contr=0.3,0.1
English Units
Geom File=g01
Flow File=f01
Plan File=p01
BEGIN DESCRIPTION:
UNT 102 IN UKCR
END DESCRIPTION:

--- UNT 102 IN UKCR.p01 (plan) ---

Plan Title=Multiple Run
Short Identifier=Multiple
Geom File=g01
Flow File=f01
Subcritical Flow
K Sum by GR= 0
Std Step Tol= 0.01
Critical Tol= 0.01
Num of Std Step Trials= 20
Max Error Tol= 0.3
Flow Tol Ratio= 0.001
Split Flow NTrial= 30
Split Flow Tol= 0.02
Split Flow Ratio= 0.02
Log Output Level= 0
Friction Slope Method= 1
Unsteady Friction Slope Method= 2
Unsteady Bridges Friction Slope Method= 1
Parabolic Critical Depth
Global Vel Dist=  1 , 1 , 1
Global Log Level= 0
CheckData=True
Encroach Param= -1, 0, 0, 0
BEGIN DESCRIPTION:
Multiple Run
END DESCRIPTION:

--- UNT 102 IN UKCR.f01 (steady flow) ---

Flow Title=Multiple
Number of Profiles=7
Profile Names=10-year,25-year,50-year,1pct_min,100-year,1pct_plu,500-year
River Rch & RM= UNT 102 IN UKCR,Reach-1,7133
    1144    1588    1958    1763    2385    3225    3524
River Rch & RM= UNT 102 IN UKCR,Reach-1,6268
    1435    2009    2491    2254    3048    4122    4546
Boundary for River Rch & Prof#=UNT 102 IN UKCR,Reach-1,1
Up Type=0
Dn Type=3
Dn Slope=0.005
Boundary for River Rch & Prof#=UNT 102 IN UKCR,Reach-1,2
Up Type=0
Dn Type=3
Dn Slope=0.005
Boundary for River Rch & Prof#=UNT 102 IN UKCR,Reach-1,3
Up Type=0
Dn Type=3
Dn Slope=0.005
Boundary for River Rch & Prof#=UNT 102 IN UKCR,Reach-1,4
Up Type=0
Dn Type=3
Dn Slope=0.005
Boundary for River Rch & Prof#=UNT 102 IN UKCR,Reach-1,5
Up Type=0
Dn Type=3
Dn Slope=0.005
Boundary for River Rch & Prof#=UNT 102 IN UKCR,Reach-1,6
Up Type=0
Dn Type=3
Dn Slope=0.005
Boundary for River Rch & Prof#=UNT 102 IN UKCR,Reach-1,7
Up Type=0
Dn Type=3
Dn Slope=0.005

--- UNT 102 IN UKCR.g01 (geometry) ---

Geom Title=Existing Conditions

River Reach=UNT 102 IN UKCR,Reach-1
Reach XY= 30
      3636760.25     10575271.00      3637070.25     10575543.00
      3637256.75     10575957.00      3637282.75     10576119.00
      3637485.00     10576377.00      3637597.25     10576726.00
      3637605.75     10576927.00      3637766.25     10577147.00
      3637791.75     10577290.00      3637878.75     10577334.00
      3637960.50     10577489.00      3638235.50     10577589.00
      3638496.75     10577611.00      3638638.75     10577574.00
      3638906.25     10577668.00      3639186.25     10577887.00
      3639179.50     10577958.00      3639240.75     10578051.00
      3639544.25     10578281.00      3639793.00     10578303.00
      3640109.00     10578168.00      3640293.75     10578222.00
      3640310.25     10578165.00      3640708.50     10577832.00
      3640961.25     10577721.00      3641107.25     10577805.00
      3641364.25     10577760.00      3641416.25     10577802.00
      3641804.25     10577818.00      3642016.25     10577650.00

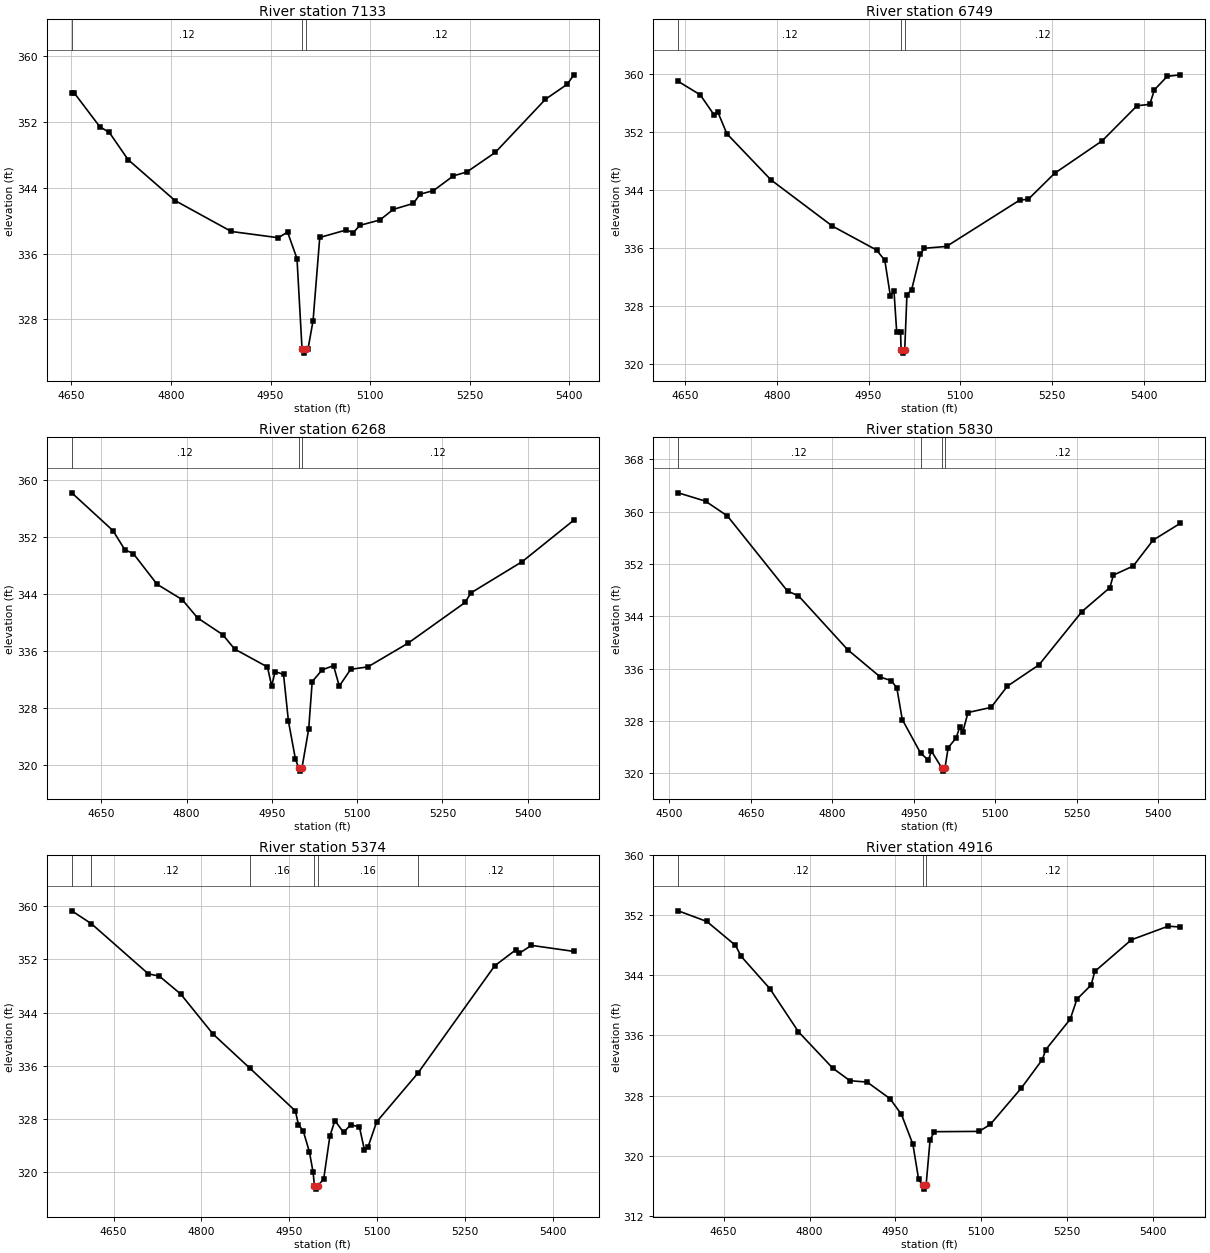
Type RM Length L Ch R = 1,7133,384,384,384
BEGIN DESCRIPTION:
UNT 102 IN UKCR 11.0
END DESCRIPTION:
XS GIS Cut Line= 3
      3636799.63     10575760.17      3637049.61     10575510.19
      3637449.57     10575460.19
#Sta/Elev= 30
  4650.5  355.54  4654.0  355.54  4692.9  351.40  4707.0  350.73  4735.3  347.42
  4806.0  342.45  4890.9  338.69  4961.6  337.93  4975.7  338.61  4989.9  335.39
  4997.5  324.41  5000.2  323.91  5003.5  324.41  5006.5  324.41  5014.1  327.84
  5024.2  337.96  5064.5  338.88  5074.6  338.53  5084.6  339.43  5114.9  340.09
  5135.0  341.37  5165.3  342.10  5175.3  343.22  5195.5  343.65  5225.7  345.45
  5245.9  345.92  5288.7  348.29  5364.3  354.75  5397.1  356.57  5407.1  357.72
#Mann=3,-1,0
  4650.5    0.12       0  4997.5    0.07       0  5003.5    0.12       0
Bank Sta=4997.5,5003.5
Exp/Cntr=0.3,0.1

Type RM Length L Ch R = 1,6749,481,481,481
BEGIN DESCRIPTION:
UNT 102 IN UKCR 10.0
END DESCRIPTION:
XS GIS Cut Line= 3
      3636899.65     10576060.16      3637199.61     10575860.19
      3637499.62     10575510.18
#Sta/Elev= 30
  4638.5  359.04  4674.5  357.19  4697.0  354.43  4703.1  354.84  4718.1  351.81
  4790.2  345.44  4890.8  339.05  4963.0  335.75  4976.5  334.33  4985.5  329.45
  4991.5  330.09  4996.0  324.38  5002.3  324.38  5003.1  322.01  5005.9  321.51
  5009.1  322.01  5012.7  329.58  5020.4  330.27  5034.7  335.19  5041.3  335.99
  5077.5  336.25  5197.1  342.64  5211.4  342.77  5254.2  346.34  5332.1  350.83
  5389.2  355.68  5410.0  355.87  5417.7  357.89  5438.6  359.74  5460.0  359.95
#Mann=3,-1,0
  4638.5    0.12       0  5003.1    0.07       0  5009.1    0.12       0
Bank Sta=5003.1,5009.1
Exp/Cntr=0.3,0.1

Type RM Length L Ch R = 1,6268,438,438,438
BEGIN DESCRIPTION:
UNT 102 IN UKCR 9.0
END DESCRIPTION:
XS GIS Cut Line= 3
      3637149.59     10576610.21      3637399.61     10576260.19
      3637849.60     10576210.19
#Sta/Elev= 30
  4598.2  358.21  4670.7  352.89  4691.6  350.19  4706.4  349.67  4748.2  345.35
  4792.4  343.19  4819.4  340.62  4863.7  338.26  4884.6  336.24  4942.3  333.72
  4949.7  331.05  4955.8  333.07  4970.6  332.67  4979.2  326.09  4991.5  320.77
  4997.1  319.57  4999.8  319.07  5003.1  319.57  5014.8  324.97  5021.0  331.66
  5038.4  333.30  5058.5  333.91  5068.6  331.03  5088.7  333.39  5118.9  333.73
  5189.3  337.05  5289.9  342.79  5300.0  344.13  5390.6  348.55  5481.1  354.37
#Mann=3,-1,0
  4598.2    0.12       0  4997.1    0.07       0  5003.1    0.12       0
Bank Sta=4997.1,5003.1
Exp/Cntr=0.3,0.1

Type RM Length L Ch R = 1,5830,456,456,456
BEGIN DESCRIPTION:
UNT 102 IN UKCR 8.0
END DESCRIPTION:
XS GIS Cut Line= 3
      3637099.59     10576710.19      3637549.61     10576660.19
      3637949.62     10576410.18
#Sta/Elev= 30
  4516.4  362.89  4566.7  361.61  4607.0  359.35  4717.6  347.87  4737.8  347.15
  4828.3  338.92  4888.7  334.72  4908.8  334.18  4918.9  333.07  4928.9  328.24
  4962.5  323.13  4976.9  322.03  4982.7  323.40  5001.6  320.85  5004.3  320.35
  5007.6  320.85  5013.4  323.92  5028.1  325.43  5034.6  327.04  5040.5  326.38
  5050.0  329.31  5092.4  330.09  5122.5  333.34  5180.9  336.61  5259.9  344.75
  5311.2  348.40  5317.7  350.32  5354.2  351.70  5390.8  355.66  5440.9  358.23
#Mann=4,-1,0
  4516.4    0.12       0  4962.5    0.16       0  5001.6    0.07       0
  5007.6    0.12       0
Bank Sta=5001.6,5007.6
Exp/Cntr=0.3,0.1

Type RM Length L Ch R = 1,5374,458,458,458
BEGIN DESCRIPTION:
UNT 102 IN UKCR 7.0
END DESCRIPTION:
XS GIS Cut Line= 3
      3637299.65     10577210.17      3637699.61     10577060.19
      3638049.63     10576810.17
#Sta/Elev= 30
  4578.5  359.34  4612.1  357.39  4709.3  349.83  4728.0  349.49  4764.5  346.79
  4819.6  340.76  4882.5  335.61  4960.3  329.15  4965.6  327.06  4973.6  326.18
  4984.3  322.96  4990.5  319.94  4992.9  317.86  4995.6  317.36  4998.9  317.86
  5008.7  318.91  5019.2  325.35  5027.8  327.70  5042.5  325.92  5054.8  327.06
  5069.6  326.76  5078.2  323.30  5084.3  323.70  5099.1  327.51  5169.5  334.85
  5300.6  351.04  5336.2  353.42  5342.4  352.92  5363.3  354.13  5435.8  353.22
#Mann=6,-1,0
  4578.5    0.16       0  4612.1    0.12       0  4882.5    0.16       0
  4992.9    0.07       0  4998.9    0.16       0  5169.5    0.12       0
Bank Sta=4992.9,4998.9
Exp/Cntr=0.3,0.1

Type RM Length L Ch R = 1,4916,197,197,197
BEGIN DESCRIPTION:
UNT 102 IN UKCR 6.0
END DESCRIPTION:
XS GIS Cut Line= 3
      3637499.63     10577410.19      3637949.61     10577410.19
      3638099.62     10577010.17
#Sta/Elev= 30
  4570.6  352.60  4620.6  351.18  4670.6  348.00  4680.6  346.53  4730.6  342.24
  4780.6  336.49  4840.6  331.64  4870.6  329.97  4900.6  329.79  4940.6  327.58
  4960.6  325.48  4980.6  321.50  4990.6  316.83  4997.6  316.03  5000.3  315.53
  5003.6  316.03  5010.6  322.08  5018.1  323.18  5096.2  323.22  5115.8  324.14
  5170.1  329.00  5206.6  332.77  5212.8  334.11  5255.5  338.17  5267.1  340.82
  5292.0  342.72  5298.3  344.52  5362.3  348.74  5426.4  350.55  5447.8  350.45
#Mann=3,-1,0
  4570.6    0.12       0  4997.6    0.07       0  5003.6    0.12       0
Bank Sta=4997.6,5003.6
Exp/Cntr=0.3,0.1

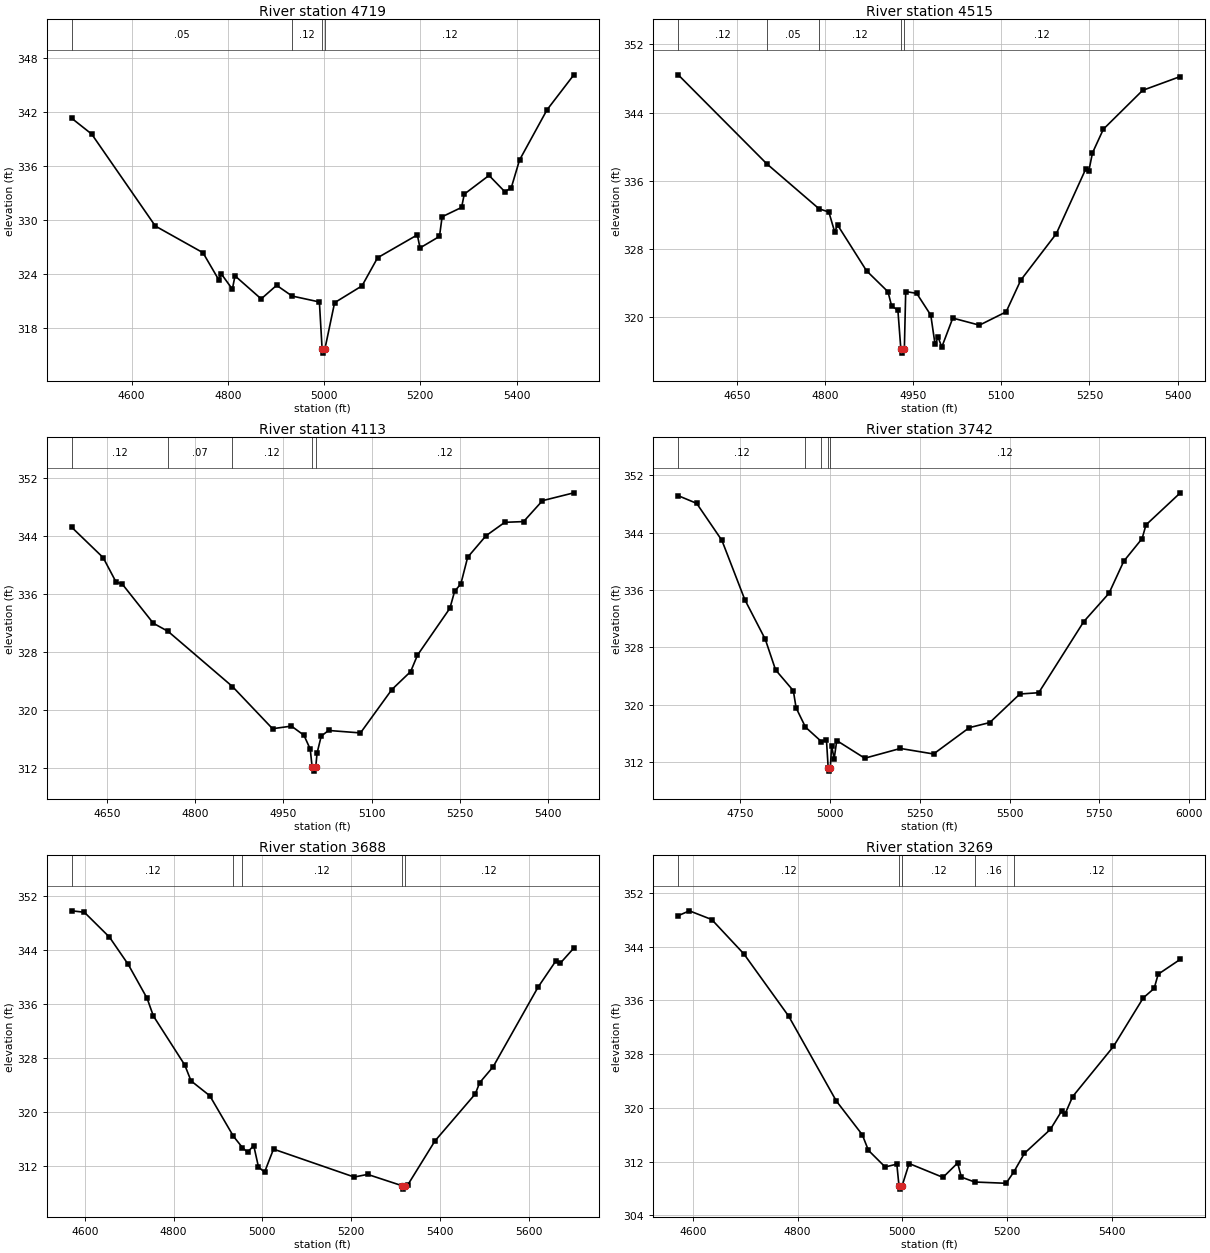
Type RM Length L Ch R = 1,4719,204,204,204
BEGIN DESCRIPTION:
Mapping XS cf08bc2d
END DESCRIPTION:
XS GIS Cut Line= 2
      3637845.21     10578008.07      3638280.19     10577059.44
#Sta/Elev= 30
  4475.5  341.32  4516.9  339.57  4649.2  329.36  4748.2  326.40  4780.8  323.41
  4786.3  324.05  4809.3  322.35  4814.8  323.83  4869.2  321.27  4901.3  322.78
  4933.4  321.59  4990.2  320.93  4995.8  315.75  4998.5  315.25  5001.8  315.75
  5021.8  320.85  5078.8  322.72  5111.2  325.84  5193.8  328.38  5199.3  326.93
  5239.8  328.21  5245.3  330.39  5285.8  331.43  5291.3  332.90  5342.8  334.98
  5375.3  333.19  5388.8  333.57  5406.2  336.69  5463.3  342.26  5519.1  346.15
#Mann=4,-1,0
  4475.5    0.05       0  4933.4    0.12       0  4995.8    0.07       0
  5001.8    0.12       0
Bank Sta=4995.8,5001.8
Exp/Cntr=0.3,0.1

Type RM Length L Ch R = 1,4515,402,402,402
BEGIN DESCRIPTION:
UNT 102 IN UKCR 5.0
END DESCRIPTION:
XS GIS Cut Line= 3
      3638399.60     10578010.16      3638249.61     10577610.19
      3638399.62     10577210.16
#Sta/Elev= 30
  4550.2  348.44  4700.8  338.01  4789.8  332.73  4806.5  332.35  4816.3  330.05
  4821.6  330.80  4870.6  325.46  4907.1  323.00  4913.3  321.34  4924.0  320.83
  4929.0  316.30  4931.7  315.80  4935.0  316.30  4937.3  323.02  4956.0  322.81
  4980.0  320.25  4987.2  316.84  4992.5  317.65  4998.7  316.51  5017.4  319.91
  5062.8  319.08  5108.2  320.64  5133.1  324.36  5193.6  329.81  5243.5  337.37
  5248.8  337.13  5255.1  339.28  5273.7  342.07  5340.5  346.62  5404.6  348.24
#Mann=5,-1,0
  4550.2    0.12       0  4700.8    0.05       0  4789.8    0.12       0
  4929.0    0.07       0  4935.0    0.12       0
Bank Sta=4929,4935
Exp/Cntr=0.3,0.1

Type RM Length L Ch R = 1,4113,371,371,371
BEGIN DESCRIPTION:
UNT 102 IN UKCR 4.0
END DESCRIPTION:
XS GIS Cut Line= 3
      3638499.61     10577960.17      3638649.61     10577560.19
      3638499.60     10577160.17
#Sta/Elev= 30
  4589.7  345.16  4643.1  340.99  4665.3  337.59  4675.1  337.40  4728.5  331.95
  4753.5  330.84  4863.1  323.24  4931.4  317.43  4963.5  317.79  4984.8  316.53
  4995.5  314.62  4998.8  312.09  5001.5  311.59  5004.8  312.09  5007.1  314.06
  5014.2  316.41  5026.7  317.19  5081.0  316.85  5134.4  322.82  5166.4  325.30
  5178.0  327.56  5233.2  334.02  5241.2  336.35  5251.8  337.37  5263.4  341.04
  5294.6  344.00  5326.6  345.85  5358.6  345.95  5390.7  348.83  5444.1  349.91
#Mann=5,-1,0
  4589.7    0.12       0  4753.5    0.07       0  4863.1    0.12       0
  4998.8    0.07       0  5004.8    0.12       0
Bank Sta=4998.8,5004.8
Exp/Cntr=0.3,0.1

Type RM Length L Ch R = 1,3742,54,54,54
BEGIN DESCRIPTION:
Mapping XS 887af6a2
END DESCRIPTION:
XS GIS Cut Line= 3
      3638687.47     10578049.74      3639224.28     10577422.70
      3639358.49     10576867.32
#Sta/Elev= 30
  4578.3  349.15  4629.6  348.08  4699.8  342.92  4763.5  334.66  4820.6  329.12
  4849.1  324.87  4898.5  321.97  4906.2  319.58  4932.3  316.89  4976.6  314.88
  4990.7  315.08  4995.4  311.26  4998.2  310.76  5001.4  311.26  5005.0  314.28
  5012.1  312.48  5019.3  315.02  5097.2  312.56  5196.4  313.92  5288.6  313.15
  5388.1  316.82  5445.0  317.53  5528.7  321.51  5581.2  321.69  5706.5  331.60
  5776.7  335.55  5817.8  340.02  5868.8  343.17  5879.6  345.08  5975.1  349.55
#Mann=5,-1,0
  4578.3    0.12       0  4932.3    0.16       0  4976.6    0.12       0
  4995.4    0.07       0  5001.4    0.12       0
Bank Sta=4995.4,5001.4
Exp/Cntr=0.3,0.1

Type RM Length L Ch R = 1,3688,419,419,419
BEGIN DESCRIPTION:
UNT 102 IN UKCR 3.0
END DESCRIPTION:
XS GIS Cut Line= 3
      3638699.60     10578060.20      3638999.61     10577760.19
      3639699.62     10577660.19
#Sta/Elev= 30
  4570.4  349.83  4598.7  349.62  4655.3  345.94  4697.7  341.89  4740.1  336.89
  4754.3  334.27  4825.0  327.02  4839.1  324.67  4881.5  322.46  4934.7  316.47
  4954.9  314.80  4966.4  314.12  4980.5  315.08  4991.1  311.94  5004.8  311.15
  5025.0  314.57  5206.8  310.44  5237.1  310.83  5314.9  309.15  5317.7  308.65
  5320.9  309.15  5328.0  309.32  5388.6  315.76  5479.6  322.73  5489.7  324.41
  5520.0  326.76  5621.0  338.52  5661.4  342.43  5671.5  342.10  5701.8  344.32
#Mann=5,-1,0
  4570.4    0.12       0  4934.7    0.16       0  4954.9    0.12       0
  5314.9    0.07       0  5320.9    0.12       0
Bank Sta=5314.9,5320.9
Exp/Cntr=0.3,0.1

Type RM Length L Ch R = 1,3269,342,342,342
BEGIN DESCRIPTION:
UNT 102 IN UKCR 2.0
END DESCRIPTION:
XS GIS Cut Line= 3
      3638849.65     10578210.17      3639249.61     10578060.19
      3639649.64     10577710.16
#Sta/Elev= 30
  4572.1  348.61  4593.4  349.33  4636.1  348.03  4697.5  342.91  4783.0  333.64
  4873.8  321.03  4923.6  315.98  4935.2  313.67  4967.2  311.19  4989.5  311.61
  4993.6  308.39  4996.3  307.89  4999.6  308.39  5013.0  311.70  5077.6  309.64
  5105.6  311.78  5112.7  309.68  5138.1  308.95  5198.1  308.76  5212.8  310.44
  5233.2  313.23  5282.6  316.78  5304.4  319.54  5311.0  319.13  5325.3  321.68
  5403.1  329.13  5460.1  336.37  5480.9  337.78  5488.5  339.89  5530.8  342.11
#Mann=5,-1,0
  4572.1    0.12       0  4993.6    0.07       0  4999.6    0.12       0
  5138.1    0.16       0  5212.8    0.12       0
Bank Sta=4993.6,4999.6
Exp/Cntr=0.3,0.1

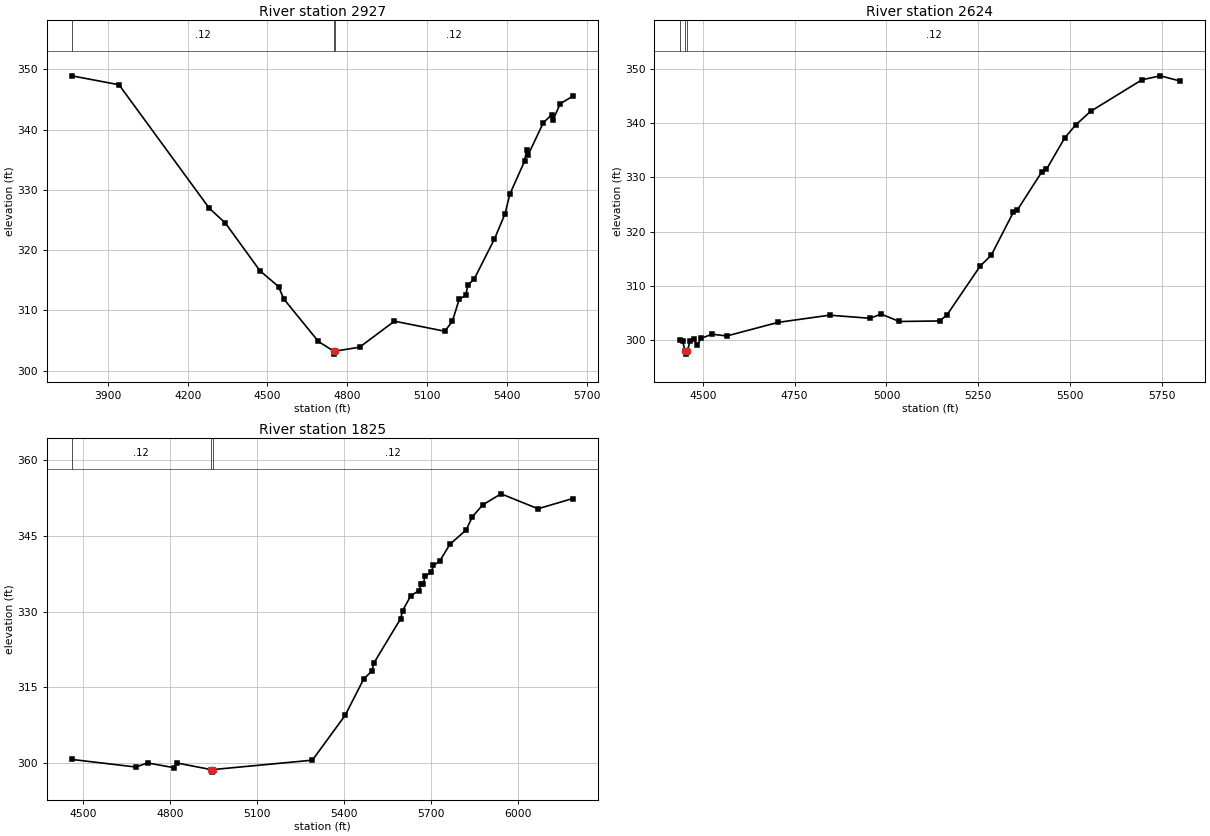
Type RM Length L Ch R = 1,2927,303,303,303
BEGIN DESCRIPTION:
Mapping XS e2f8b4ec
END DESCRIPTION:
XS GIS Cut Line= 4
      3638421.82     10578520.03      3639359.33     10578520.03
      3639611.06     10578112.05      3639758.65     10577669.30
#Sta/Elev= 30
  3763.8  348.94  3941.6  347.46  4281.6  326.93  4341.6  324.50  4471.6  316.58
  4541.6  313.94  4561.6  311.88  4691.6  304.83  4748.7  303.23  4751.5  302.73
  4754.7  303.23  4846.3  303.88  4977.6  308.20  5166.8  306.53  5195.2  308.16
  5221.5  311.89  5245.9  312.47  5253.2  314.16  5277.5  315.20  5353.3  321.81
  5393.5  326.02  5411.3  329.26  5467.3  334.80  5474.5  336.64  5479.8  335.76
  5537.8  341.18  5569.4  342.49  5574.7  341.67  5601.0  344.32  5647.4  345.52
#Mann=3,-1,0
  3763.8    0.12       0  4748.7    0.07       0  4754.7    0.12       0
Bank Sta=4748.7,4754.7
Exp/Cntr=0.3,0.1

Type RM Length L Ch R = 1,2624,799,799,799
BEGIN DESCRIPTION:
Mapping XS ee6d5ed4
END DESCRIPTION:
XS GIS Cut Line= 2
      3639802.04     10578858.52      3639819.40     10577495.74
#Sta/Elev= 30
  4436.9  300.03  4445.2  299.84  4452.2  297.93  4455.0  297.43  4458.2  297.93
  4465.2  299.87  4475.2  300.16  4485.2  299.11  4495.2  300.31  4525.2  301.11
  4565.2  300.77  4705.3  303.28  4845.3  304.60  4955.3  304.03  4985.3  304.80
  5035.3  303.44  5145.3  303.54  5165.3  304.71  5255.3  313.67  5285.3  315.66
  5345.3  323.56  5355.3  323.88  5422.1  330.92  5435.3  331.44  5485.3  337.28
  5515.3  339.65  5555.3  342.13  5695.3  347.95  5745.3  348.68  5799.8  347.71
#Mann=3,-1,0
  4436.9    0.12       0  4452.2    0.07       0  4458.2    0.12       0
Bank Sta=4452.2,4458.2
Exp/Cntr=0.3,0.1

Type RM Length L Ch R = 1,1825,0,0,0
BEGIN DESCRIPTION:
UNT 102 IN UKCR 1.0
END DESCRIPTION:
XS GIS Cut Line= 3
      3640539.88     10578589.44      3640435.72     10577842.95
      3639777.23     10577123.81
#Sta/Elev= 30
  4459.7  300.78  4681.1  299.28  4721.5  300.09  4812.3  299.15  4822.4  300.08
  4940.6  298.77  4943.3  298.27  4946.6  298.77  5290.4  300.63  5403.9  309.52
  5467.4  316.66  5495.8  318.24  5502.6  319.82  5595.1  328.59  5601.8  330.16
  5630.2  333.14  5658.6  334.14  5665.3  335.45  5672.8  335.36  5679.5  337.00
  5701.1  337.77  5707.9  339.12  5729.5  339.91  5764.6  343.25  5821.4  346.14
  5842.3  348.69  5878.1  351.06  5941.6  353.26  6069.3  350.31  6188.5  352.32
#Mann=3,-1,0
  4459.7    0.12       0  4940.6    0.07       0  4946.6    0.12       0
Bank Sta=4940.6,4946.6
Exp/Cntr=0.3,0.1

Chan Stop Cuts=-1