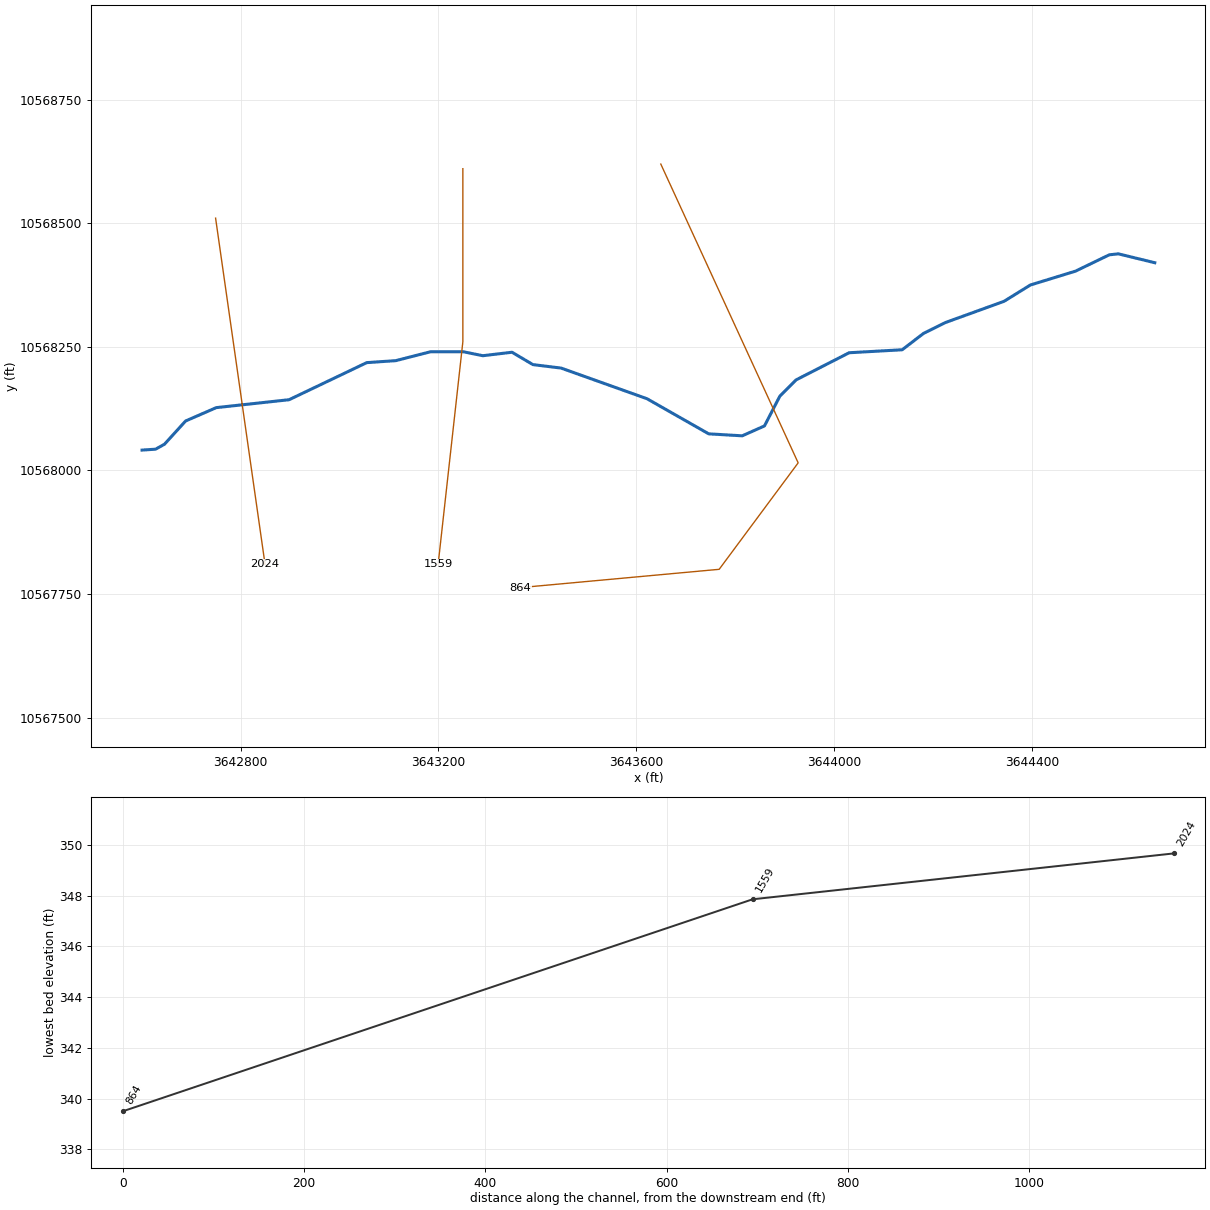
--- UNT 105 IN UKCR.prj (project) ---

Proj Title=UNT 105 IN UKCR Base Level Engineering
Current Plan=p01
Default Exp/Contr=0.3,0.1
English Units
Geom File=g01
Flow File=f01
Plan File=p01
BEGIN DESCRIPTION:
UNT 105 IN UKCR
END DESCRIPTION:

--- UNT 105 IN UKCR.p01 (plan) ---

Plan Title=Multiple Run
Short Identifier=Multiple
Geom File=g01
Flow File=f01
Subcritical Flow
K Sum by GR= 0
Std Step Tol= 0.01
Critical Tol= 0.01
Num of Std Step Trials= 20
Max Error Tol= 0.3
Flow Tol Ratio= 0.001
Split Flow NTrial= 30
Split Flow Tol= 0.02
Split Flow Ratio= 0.02
Log Output Level= 0
Friction Slope Method= 1
Unsteady Friction Slope Method= 2
Unsteady Bridges Friction Slope Method= 1
Parabolic Critical Depth
Global Vel Dist=  1 , 1 , 1
Global Log Level= 0
CheckData=True
Encroach Param= -1, 0, 0, 0
BEGIN DESCRIPTION:
Multiple Run
END DESCRIPTION:

--- UNT 105 IN UKCR.f01 (steady flow) ---

Flow Title=Multiple
Number of Profiles=7
Profile Names=10-year,25-year,50-year,1pct_min,100-year,1pct_plu,500-year
River Rch & RM= UNT 105 IN UKCR,Reach-1,2024
     897    1223    1490    1327    1794    2427    2591
Boundary for River Rch & Prof#=UNT 105 IN UKCR,Reach-1,1
Up Type=0
Dn Type=3
Dn Slope=0.005
Boundary for River Rch & Prof#=UNT 105 IN UKCR,Reach-1,2
Up Type=0
Dn Type=3
Dn Slope=0.005
Boundary for River Rch & Prof#=UNT 105 IN UKCR,Reach-1,3
Up Type=0
Dn Type=3
Dn Slope=0.005
Boundary for River Rch & Prof#=UNT 105 IN UKCR,Reach-1,4
Up Type=0
Dn Type=3
Dn Slope=0.005
Boundary for River Rch & Prof#=UNT 105 IN UKCR,Reach-1,5
Up Type=0
Dn Type=3
Dn Slope=0.005
Boundary for River Rch & Prof#=UNT 105 IN UKCR,Reach-1,6
Up Type=0
Dn Type=3
Dn Slope=0.005
Boundary for River Rch & Prof#=UNT 105 IN UKCR,Reach-1,7
Up Type=0
Dn Type=3
Dn Slope=0.005

--- UNT 105 IN UKCR.g01 (geometry) ---

Geom Title=Existing Conditions

River Reach=UNT 105 IN UKCR,Reach-1
Reach XY= 30
      3642600.91     10568041.14      3642628.25     10568043.00
      3642646.25     10568053.00      3642689.00     10568100.00
      3642751.00     10568127.00      3642898.25     10568143.00
      3643055.25     10568218.00      3643114.00     10568222.00
      3643184.25     10568240.00      3643250.50     10568240.00
      3643290.00     10568232.00      3643349.00     10568239.00
      3643391.25     10568214.00      3643448.25     10568207.00
      3643622.00     10568145.00      3643746.75     10568074.00
      3643814.50     10568070.00      3643859.50     10568090.00
      3643890.50     10568150.00      3643923.25     10568183.00
      3644030.75     10568238.00      3644138.00     10568244.00
      3644181.00     10568277.00      3644225.25     10568299.00
      3644344.00     10568342.00      3644397.25     10568375.00
      3644488.50     10568403.00      3644556.75     10568436.00
      3644575.00     10568438.00      3644648.75     10568420.00

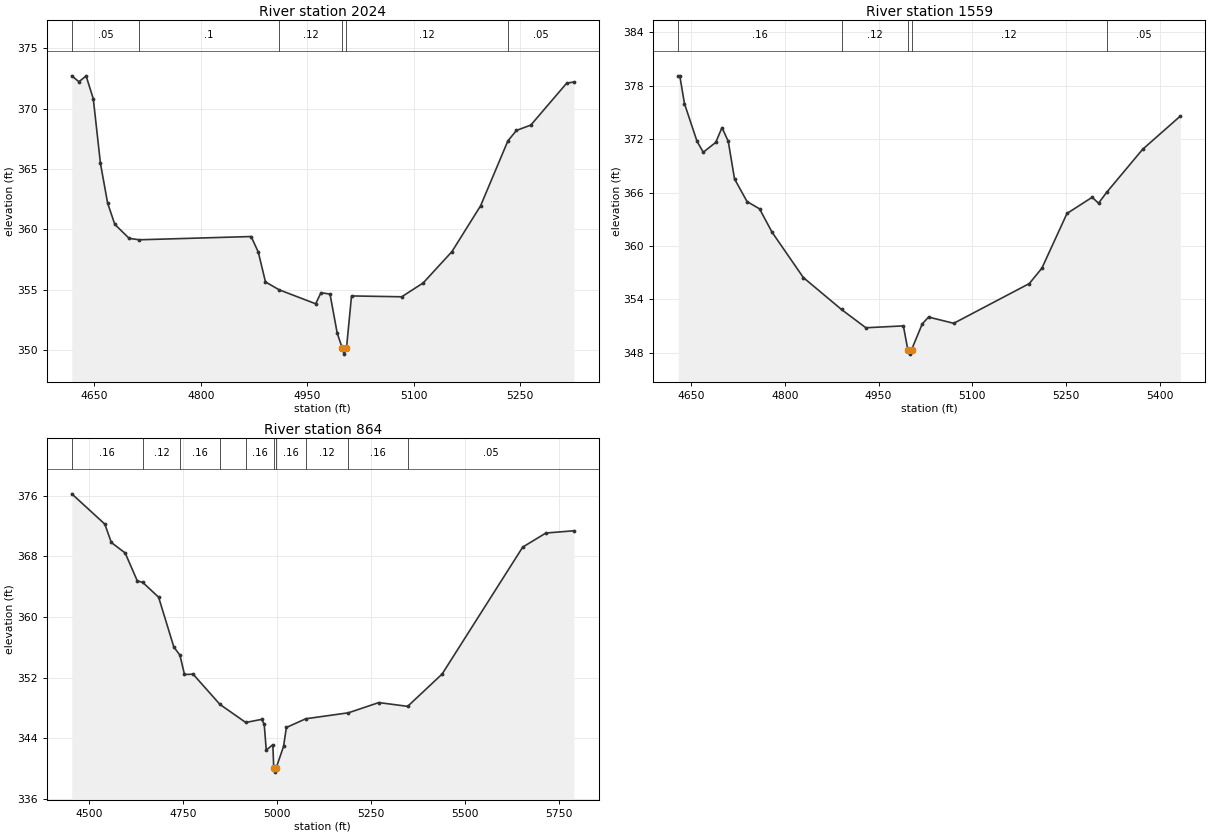
Type RM Length L Ch R = 1,2024,465,465,465
BEGIN DESCRIPTION:
UNT 105 IN UKCR 3.0
END DESCRIPTION:
XS GIS Cut Line= 3
      3642749.61     10568510.20      3642799.61     10568160.19
      3642849.61     10567810.21
#Sta/Elev= 30
  4618.3  372.72  4628.4  372.23  4638.5  372.71  4648.6  370.82  4658.7  365.46
  4668.8  362.18  4678.9  360.42  4699.1  359.26  4713.3  359.14  4870.9  359.41
  4881.0  358.12  4891.1  355.65  4910.3  355.00  4961.8  353.84  4969.3  354.76
  4982.0  354.64  4992.1  351.42  4999.2  350.17  5001.9  349.67  5005.2  350.17
  5012.3  354.49  5083.0  354.42  5113.3  355.57  5153.7  358.16  5194.1  361.96
  5232.5  367.33  5244.6  368.20  5264.8  368.64  5315.3  372.11  5325.4  372.21
#Mann=6,-1,0
  4618.3    0.05       0  4713.3     0.1       0  4910.3    0.12       0
  4999.2    0.07       0  5005.2    0.12       0  5232.5    0.05       0
Bank Sta=4999.2,5005.2
Exp/Cntr=0.3,0.1

Type RM Length L Ch R = 1,1559,695,695,695
BEGIN DESCRIPTION:
UNT 105 IN UKCR 2.0
END DESCRIPTION:
XS GIS Cut Line= 3
      3643249.61     10568610.18      3643249.61     10568260.19
      3643199.60     10567810.15
#Sta/Elev= 30
  4629.7  379.10  4632.2  379.10  4639.7  375.97  4659.7  371.76  4669.7  370.52
  4689.7  371.63  4699.7  373.29  4709.7  371.74  4719.7  367.53  4739.7  364.99
  4759.7  364.17  4779.7  361.55  4829.7  356.46  4890.8  352.87  4929.7  350.82
  4989.7  351.03  4996.8  348.36  4999.6  347.86  5002.8  348.36  5019.9  351.26
  5030.0  352.02  5070.2  351.32  5191.0  355.78  5211.1  357.50  5251.3  363.65
  5291.6  365.47  5301.7  364.80  5314.6  366.01  5372.1  370.84  5432.5  374.58
#Mann=5,-1,0
  4629.7    0.16       0  4890.8    0.12       0  4996.8    0.07       0
  5002.8    0.12       0  5314.6    0.05       0
Bank Sta=4996.8,5002.8
Exp/Cntr=0.3,0.1

Type RM Length L Ch R = 1,864,0,0,0
BEGIN DESCRIPTION:
UNT 105 IN UKCR 1.0
END DESCRIPTION:
XS GIS Cut Line= 4
      3643649.88     10568619.48      3643927.64     10568015.34
      3643767.92     10567800.07      3643365.41     10567763.03
#Sta/Elev= 30
  4453.1  376.27  4541.1  372.27  4558.5  369.84  4595.4  368.45  4627.5  364.78
  4642.3  364.56  4684.4  362.61  4724.9  356.04  4741.2  354.95  4753.3  352.40
  4776.3  352.44  4847.7  348.45  4916.5  346.06  4958.6  346.47  4965.6  345.85
  4971.1  342.41  4988.6  343.12  4991.1  340.00  4993.9  339.50  4997.1  340.00
  5017.1  342.89  5024.7  345.40  5076.3  346.55  5190.0  347.34  5270.9  348.69
  5347.7  348.19  5439.5  352.46  5654.1  369.23  5715.8  371.09  5790.3  371.39
#Mann=10,-1,0
  4453.1    0.16       0  4642.3    0.12       0  4741.2    0.16       0
  4847.7    0.12       0  4916.5    0.16       0  4991.1    0.07       0
  4997.1    0.16       0  5076.3    0.12       0  5190.0    0.16       0
  5347.7    0.05       0
Bank Sta=4991.1,4997.1
Exp/Cntr=0.3,0.1

Chan Stop Cuts=-1