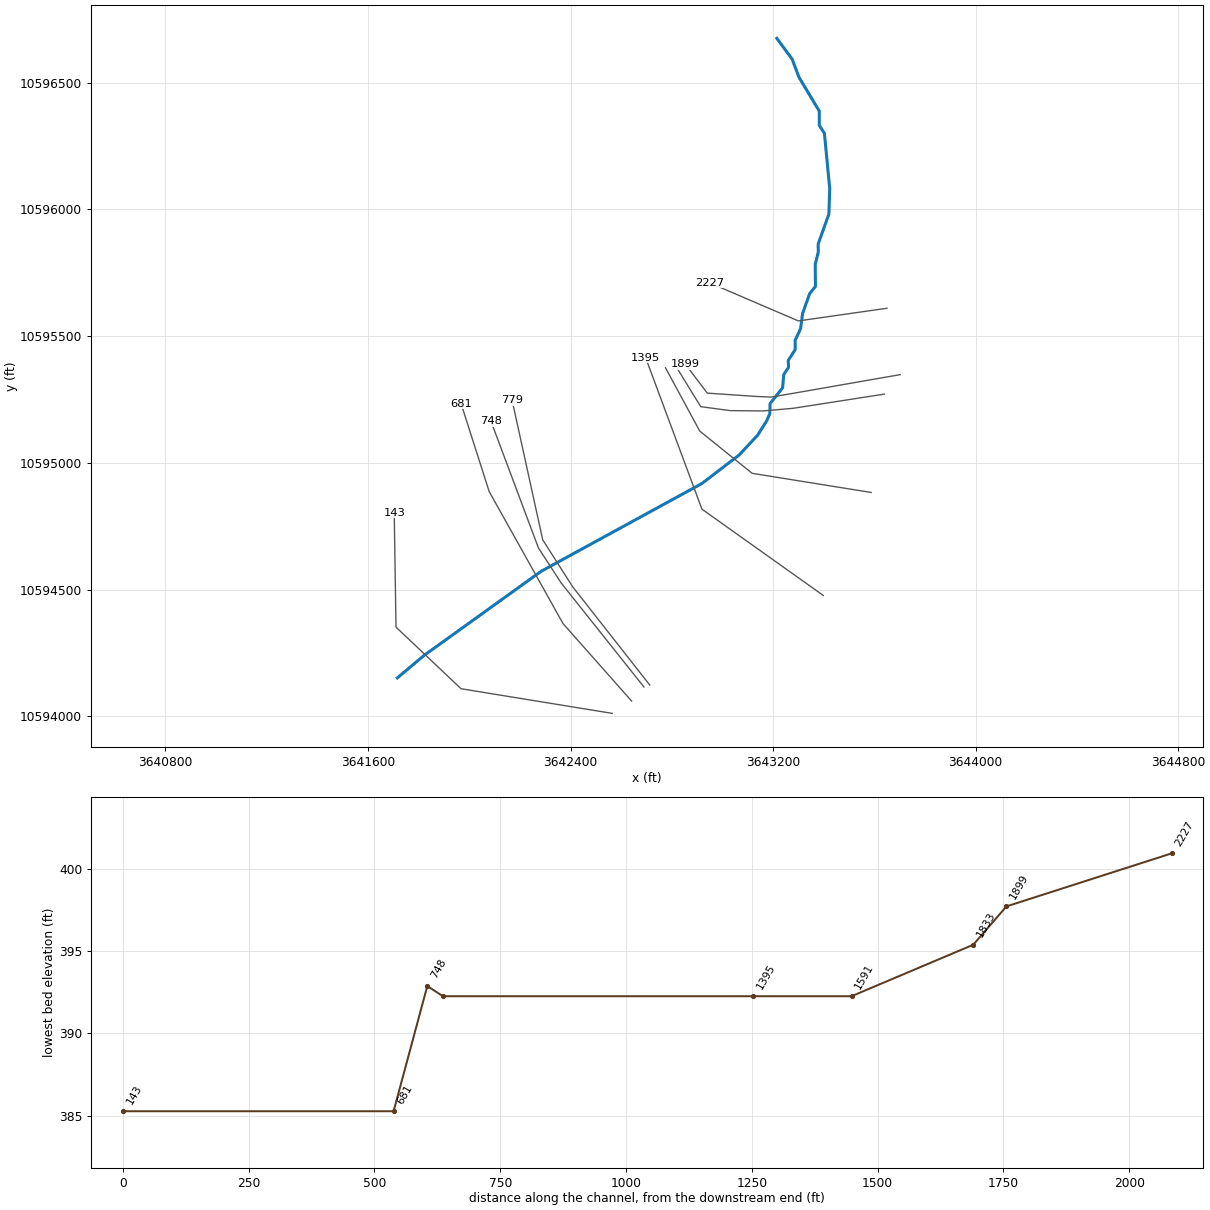
--- UNT 108 IN UKCR.prj (project) ---

Proj Title=UNT 108 IN UKCR Base Level Engineering
Current Plan=p01
Default Exp/Contr=0.3,0.1
English Units
Geom File=g01
Flow File=f01
Plan File=p01
BEGIN DESCRIPTION:
UNT 108 IN UKCR
END DESCRIPTION:

--- UNT 108 IN UKCR.p01 (plan) ---

Plan Title=Multiple Run
Short Identifier=Multiple
Geom File=g01
Flow File=f01
Subcritical Flow
K Sum by GR= 0
Std Step Tol= 0.01
Critical Tol= 0.01
Num of Std Step Trials= 20
Max Error Tol= 0.3
Flow Tol Ratio= 0.001
Split Flow NTrial= 30
Split Flow Tol= 0.02
Split Flow Ratio= 0.02
Log Output Level= 0
Friction Slope Method= 1
Unsteady Friction Slope Method= 2
Unsteady Bridges Friction Slope Method= 1
Parabolic Critical Depth
Global Vel Dist=  1 , 1 , 1
Global Log Level= 0
CheckData=True
Encroach Param= -1, 0, 0, 0
BEGIN DESCRIPTION:
Multiple Run
END DESCRIPTION:

--- UNT 108 IN UKCR.f01 (steady flow) ---

Flow Title=Multiple
Number of Profiles=7
Profile Names=10-year,25-year,50-year,1pct_min,100-year,1pct_plu,500-year
River Rch & RM= UNT 108 IN UKCR,Reach-1,2227
     469     613     726     630     853    1153    1168
Boundary for River Rch & Prof#=UNT 108 IN UKCR,Reach-1,1
Up Type=0
Dn Type=3
Dn Slope=0.005
Boundary for River Rch & Prof#=UNT 108 IN UKCR,Reach-1,2
Up Type=0
Dn Type=3
Dn Slope=0.005
Boundary for River Rch & Prof#=UNT 108 IN UKCR,Reach-1,3
Up Type=0
Dn Type=3
Dn Slope=0.005
Boundary for River Rch & Prof#=UNT 108 IN UKCR,Reach-1,4
Up Type=0
Dn Type=3
Dn Slope=0.005
Boundary for River Rch & Prof#=UNT 108 IN UKCR,Reach-1,5
Up Type=0
Dn Type=3
Dn Slope=0.005
Boundary for River Rch & Prof#=UNT 108 IN UKCR,Reach-1,6
Up Type=0
Dn Type=3
Dn Slope=0.005
Boundary for River Rch & Prof#=UNT 108 IN UKCR,Reach-1,7
Up Type=0
Dn Type=3
Dn Slope=0.005

--- UNT 108 IN UKCR.g01 (geometry) ---

Geom Title=Existing Conditions

River Reach=UNT 108 IN UKCR,Reach-1
Reach XY= 30
      3643214.50     10596675.00      3643275.00     10596593.00
      3643302.25     10596521.00      3643382.25     10596388.00
      3643382.25     10596332.00      3643402.50     10596300.00
      3643423.50     10596082.00      3643420.25     10595982.00
      3643378.00     10595864.00      3643378.25     10595831.00
      3643366.25     10595784.00      3643367.00     10595696.00
      3643344.25     10595668.00      3643316.50     10595590.00
      3643308.25     10595529.00      3643286.75     10595484.00
      3643286.75     10595446.00      3643259.75     10595405.00
      3643260.75     10595377.00      3643242.00     10595349.00
      3643237.25     10595296.00      3643187.75     10595234.00
      3643187.00     10595195.00      3643175.00     10595167.00
      3643139.25     10595110.00      3643065.50     10595031.00
      3642919.00     10594919.00      3642283.00     10594572.00
      3641822.00     10594241.00      3641715.75     10594152.00

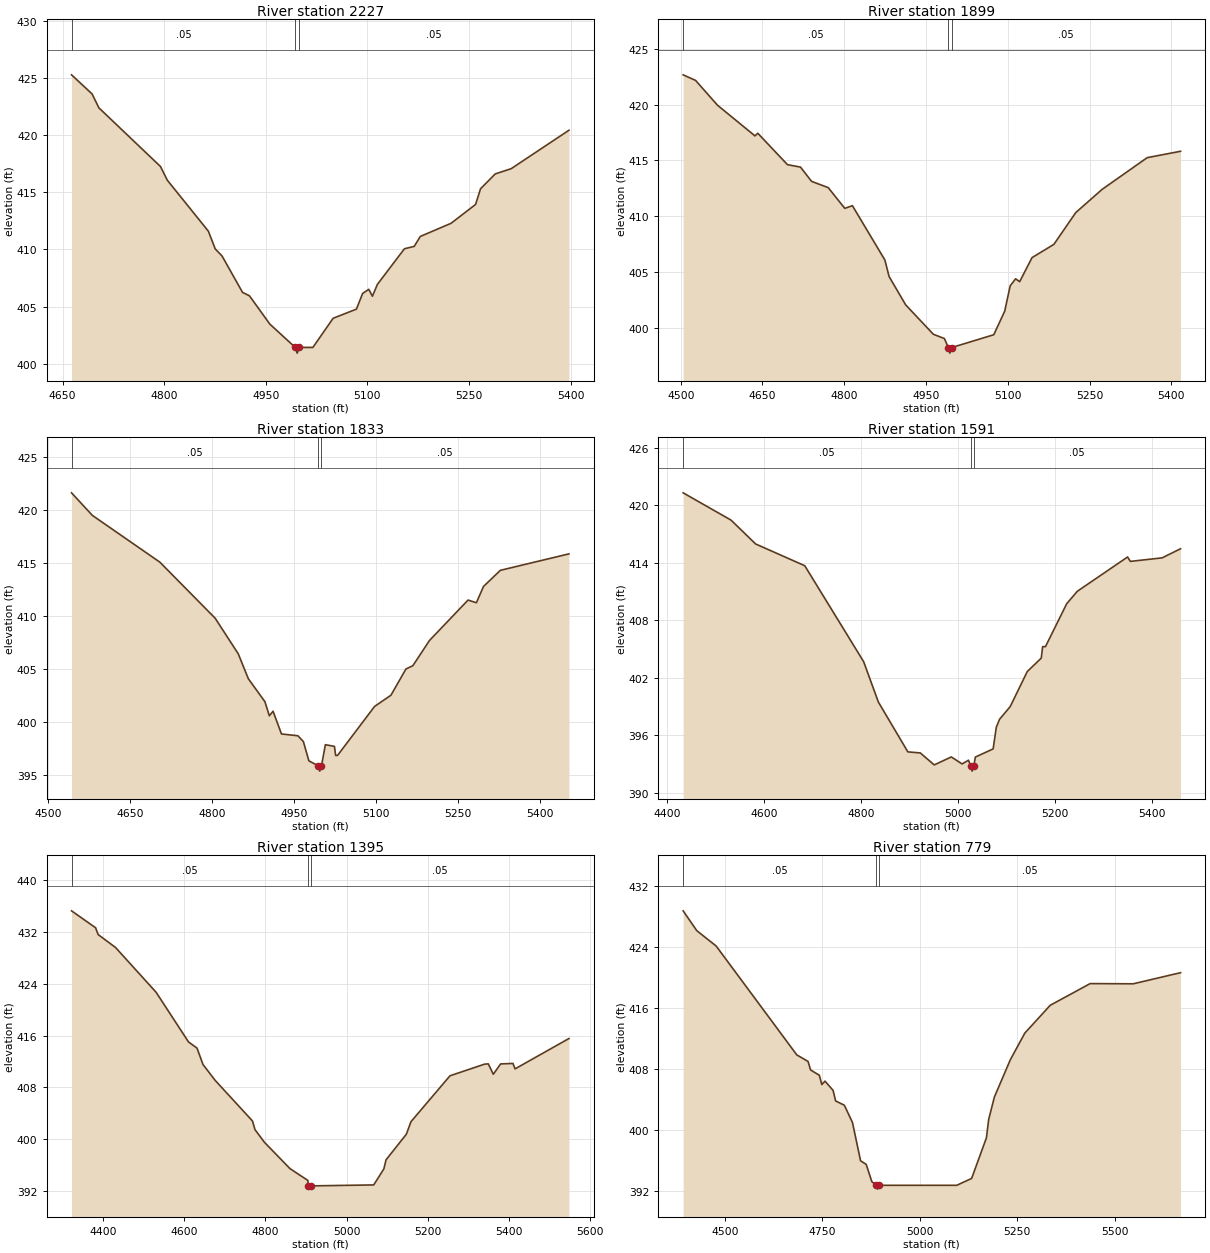
Type RM Length L Ch R = 1,2227,328,328,328
BEGIN DESCRIPTION:
UNT 108 IN UKCR 5.0
END DESCRIPTION:
XS GIS Cut Line= 3
      3643649.60     10595610.19      3643299.61     10595560.19
      3642949.64     10595710.18
#Sta/Elev= 30
  4663.2  425.28  4693.5  423.61  4703.6  422.39  4794.5  417.26  4804.6  416.06
  4865.2  411.60  4875.3  410.05  4885.4  409.43  4915.7  406.24  4925.8  405.95
  4956.1  403.46  4993.5  401.43  4996.3  400.93  4999.5  401.43  5019.5  401.43
  5049.4  403.98  5083.8  404.78  5092.9  406.15  5102.0  406.51  5107.4  405.91
  5114.7  406.94  5154.6  410.06  5169.1  410.27  5178.1  411.14  5223.5  412.29
  5259.7  413.94  5267.0  415.31  5288.7  416.61  5312.3  417.07  5397.5  420.43
#Mann=3,-1,0
  4663.2    0.05       0  4993.5    0.03       0  4999.5    0.05       0
Bank Sta=4993.5,4999.5
Exp/Cntr=0.3,0.1

Type RM Length L Ch R = 1,1899,66,66,66
BEGIN DESCRIPTION:
Mapping XS 6f112f2b
END DESCRIPTION:
XS GIS Cut Line= 6
      3643701.75     10595348.29      3643276.00     10595274.07
      3643192.66     10595259.75      3643131.47     10595262.36
      3642940.06     10595275.38      3642853.70     10595388.81
#Sta/Elev= 30
  4504.5  422.68  4527.3  422.18  4567.6  419.95  4636.3  417.20  4641.4  417.44
  4695.9  414.62  4719.8  414.40  4740.1  413.12  4770.6  412.56  4801.0  410.70
  4815.0  410.94  4874.6  406.06  4882.3  404.58  4912.7  402.04  4963.5  399.40
  4983.7  399.02  4991.0  398.21  4993.8  397.71  4997.0  398.21  5074.3  399.36
  5094.4  401.48  5104.4  403.75  5114.4  404.38  5121.8  404.12  5144.5  406.28
  5184.6  407.47  5224.7  410.32  5273.0  412.40  5355.8  415.25  5416.9  415.82
#Mann=3,-1,0
  4504.5    0.05       0  4991.0    0.03       0  4997.0    0.05       0
Bank Sta=4991,4997
Exp/Cntr=0.3,0.1

Type RM Length L Ch R = 1,1833,242,242,242
BEGIN DESCRIPTION:
UNT 108 IN UKCR 4.0
END DESCRIPTION:
XS GIS Cut Line= 6
      3643639.27     10595271.47      3643278.60     10595215.48
      3643160.11     10595205.06      3643029.90     10595206.37
      3642914.02     10595221.99      3642820.25     10595374.37
#Sta/Elev= 30
  4543.3  421.59  4581.3  419.47  4704.9  415.06  4806.1  409.78  4848.3  406.43
  4866.8  404.08  4897.1  401.92  4905.2  400.59  4912.0  401.02  4927.4  398.88
  4957.5  398.71  4967.5  398.16  4977.5  396.35  4994.6  395.88  4997.4  395.38
  5000.6  395.88  5007.7  397.87  5024.3  397.71  5026.5  396.86  5030.0  396.86
  5097.7  401.47  5127.7  402.53  5155.1  405.00  5167.8  405.31  5198.1  407.68
  5268.7  411.49  5284.0  411.24  5297.0  412.77  5327.8  414.29  5453.3  415.84
#Mann=3,-1,0
  4543.3    0.05       0  4994.6    0.03       0  5000.6    0.05       0
Bank Sta=4994.6,5000.6
Exp/Cntr=0.3,0.1

Type RM Length L Ch R = 1,1591,196,196,196
BEGIN DESCRIPTION:
Mapping XS 2fc0b937
END DESCRIPTION:
XS GIS Cut Line= 4
      3643587.21     10594883.45      3643117.14     10594958.97
      3642910.11     10595125.64      3642774.83     10595375.38
#Sta/Elev= 30
  4432.7  421.31  4531.5  418.46  4582.2  415.97  4683.5  413.70  4805.0  403.68
  4835.4  399.46  4896.2  394.26  4921.8  394.15  4950.6  392.90  4985.8  393.73
  5008.1  393.00  5021.2  393.39  5026.0  392.75  5028.7  392.25  5032.0  392.75
  5035.4  393.72  5072.1  394.57  5078.6  396.83  5085.4  397.67  5107.3  398.99
  5142.5  402.65  5171.3  404.05  5174.2  405.25  5180.0  405.25  5223.8  409.73
  5245.7  411.03  5349.4  414.61  5355.1  414.15  5420.7  414.52  5458.6  415.47
#Mann=3,-1,0
  4432.7    0.05       0  5026.0    0.03       0  5032.0    0.05       0
Bank Sta=5026,5032
Exp/Cntr=0.3,0.1

Type RM Length L Ch R = 1,1395,616,616,616
BEGIN DESCRIPTION:
Mapping XS 589774b0
END DESCRIPTION:
XS GIS Cut Line= 3
      3643397.97     10594477.25      3642918.82     10594817.52
      3642696.60     10595414.73
#Sta/Elev= 30
  4322.4  435.29  4381.7  432.67  4387.9  431.62  4430.8  429.62  4530.6  422.70
  4610.5  415.01  4631.4  414.06  4646.2  411.52  4675.7  409.10  4768.0  402.79
  4774.2  401.45  4797.5  399.49  4860.2  395.43  4904.5  393.59  4905.1  392.75
  4907.8  392.25  4911.1  392.75  5066.6  392.90  5091.6  395.39  5096.9  396.78
  5146.9  400.74  5158.3  402.68  5254.4  409.78  5339.7  411.58  5348.7  411.62
  5361.1  410.02  5379.0  411.61  5409.4  411.69  5414.7  410.85  5547.3  415.54
#Mann=3,-1,0
  4322.4    0.05       0  4905.1   0.033       0  4911.1    0.05       0
Bank Sta=4905.1,4911.1
Exp/Cntr=0.3,0.1

Type RM Length L Ch R = 1,779,31,31,31
BEGIN DESCRIPTION:
Mapping XS 400935f5
END DESCRIPTION:
XS GIS Cut Line= 4
      3642712.96     10594123.54      3642408.34     10594511.16
      3642289.94     10594696.73      3642169.14     10595246.60
#Sta/Elev= 30
  4393.3  428.74  4428.3  426.14  4478.1  424.12  4684.9  409.85  4713.8  408.99
  4720.2  407.88  4742.7  407.18  4749.1  405.96  4757.2  406.41  4778.0  405.20
  4784.4  403.82  4806.9  403.25  4827.7  400.99  4848.5  395.97  4863.0  395.49
  4877.4  393.23  4889.2  392.75  4891.9  392.25  4895.2  392.75  5095.2  392.75
  5133.4  393.65  5171.4  398.98  5177.2  401.39  5191.9  404.34  5232.8  409.22
  5269.9  412.71  5335.2  416.36  5437.6  419.20  5547.9  419.17  5669.4  420.63
#Mann=3,-1,0
  4393.3    0.05       0  4889.2    0.03       0  4895.2    0.05       0
Bank Sta=4889.2,4895.2
Exp/Cntr=0.3,0.1

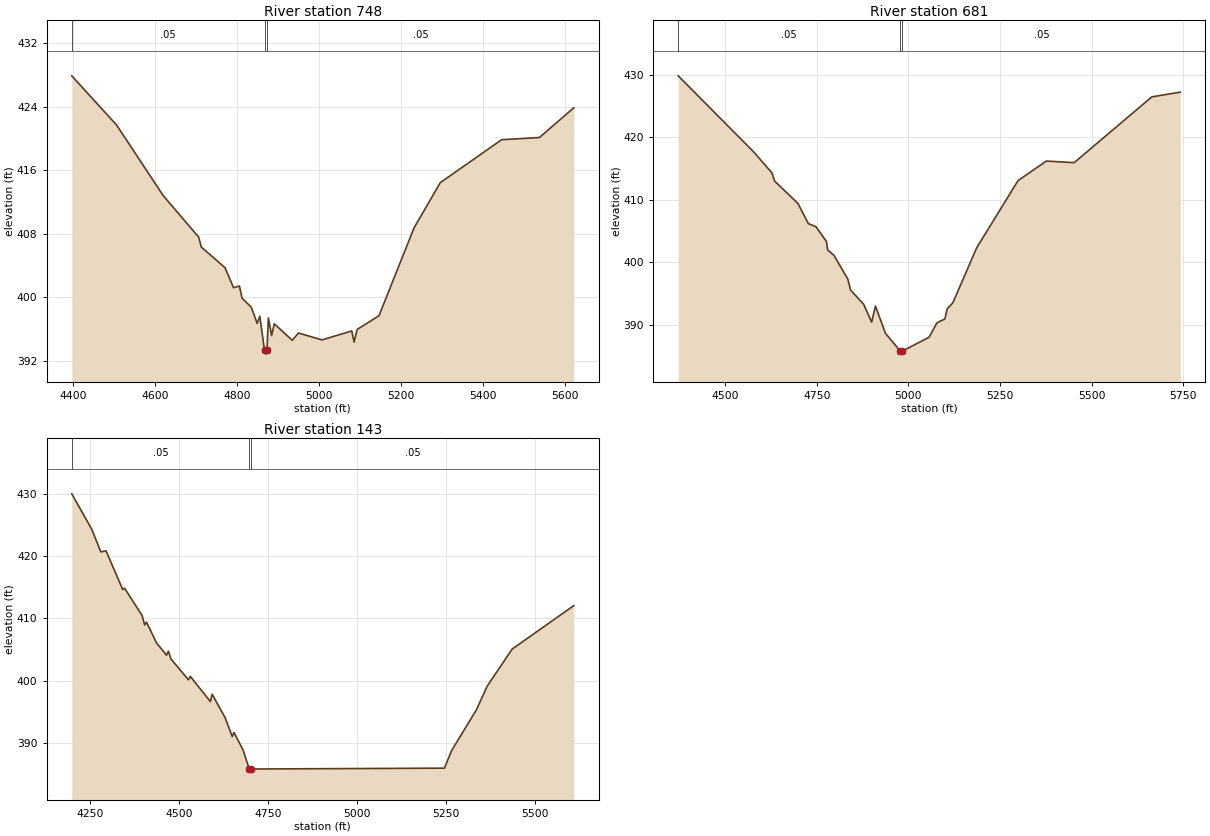
Type RM Length L Ch R = 1,748,67,67,67
BEGIN DESCRIPTION:
UNT 108 IN UKCR 3.0
END DESCRIPTION:
XS GIS Cut Line= 4
      3642689.64     10594116.14      3642363.26     10594525.85
      3642272.99     10594664.74      3642085.47     10595164.77
#Sta/Elev= 30
  4397.0  427.91  4506.1  421.72  4619.8  412.83  4706.3  407.60  4712.7  406.35
  4770.4  403.76  4791.2  401.24  4805.6  401.44  4812.0  399.92  4834.4  398.78
  4848.9  396.74  4855.2  397.64  4866.7  393.37  4869.4  392.87  4872.7  393.37
  4876.1  397.43  4884.1  395.21  4890.5  396.69  4934.3  394.61  4949.5  395.53
  5006.8  394.66  5079.3  395.79  5085.0  394.39  5092.3  395.97  5145.7  397.71
  5231.1  408.77  5295.2  414.47  5444.7  419.87  5536.5  420.14  5620.5  423.89
#Mann=3,-1,0
  4397.0    0.05       0  4866.7    0.03       0  4872.7    0.05       0
Bank Sta=4866.7,4872.7
Exp/Cntr=0.3,0.1

Type RM Length L Ch R = 1,681,538,538,538
BEGIN DESCRIPTION:
UNT 108 IN UKCR 2.0
END DESCRIPTION:
XS GIS Cut Line= 4
      3642641.05     10594060.56      3642370.21     10594366.13
      3642078.54     10594886.96      3641967.44     10595234.15
#Sta/Elev= 30
  4372.2  429.82  4578.4  417.62  4627.7  414.29  4635.2  412.97  4698.8  409.38
  4727.2  406.16  4748.1  405.65  4776.6  403.30  4779.9  401.94  4797.2  401.07
  4834.8  397.28  4842.5  395.51  4878.2  393.24  4899.9  390.38  4910.2  392.96
  4937.6  388.59  4978.0  385.76  4980.7  385.26  4984.0  385.76  5056.3  387.95
  5078.0  390.28  5099.7  390.89  5106.1  392.52  5121.4  393.48  5186.5  402.29
  5299.4  413.05  5376.4  416.17  5452.5  415.92  5664.3  426.45  5742.0  427.21
#Mann=3,-1,0
  4372.2    0.05       0  4978.0    0.03       0  4984.0    0.05       0
Bank Sta=4978,4984
Exp/Cntr=0.3,0.1

Type RM Length L Ch R = 1,143,0,0,0
BEGIN DESCRIPTION:
UNT 108 IN UKCR 1.0
END DESCRIPTION:
XS GIS Cut Line= 4
      3642564.64     10594011.96      3641967.43     10594109.18
      3641710.49     10594352.24      3641703.54     10594803.62
#Sta/Elev= 30
  4199.5  430.04  4255.3  424.38  4281.2  420.70  4295.8  420.86  4342.7  414.63
  4347.8  414.86  4397.1  410.45  4404.2  408.94  4409.3  409.40  4437.6  406.06
  4465.7  404.06  4470.8  404.73  4478.1  403.47  4527.3  400.11  4532.3  400.67
  4588.8  396.62  4593.8  397.79  4630.1  394.04  4650.3  390.98  4655.3  391.64
  4680.8  388.80  4698.0  385.76  4700.8  385.26  4704.0  385.76  5246.2  385.90
  5266.2  388.71  5336.2  395.30  5366.2  399.08  5436.2  405.05  5609.7  412.06
#Mann=3,-1,0
  4199.5    0.05       0  4698.0   0.033       0  4704.0    0.05       0
Bank Sta=4698,4704
Exp/Cntr=0.3,0.1

Chan Stop Cuts=-1