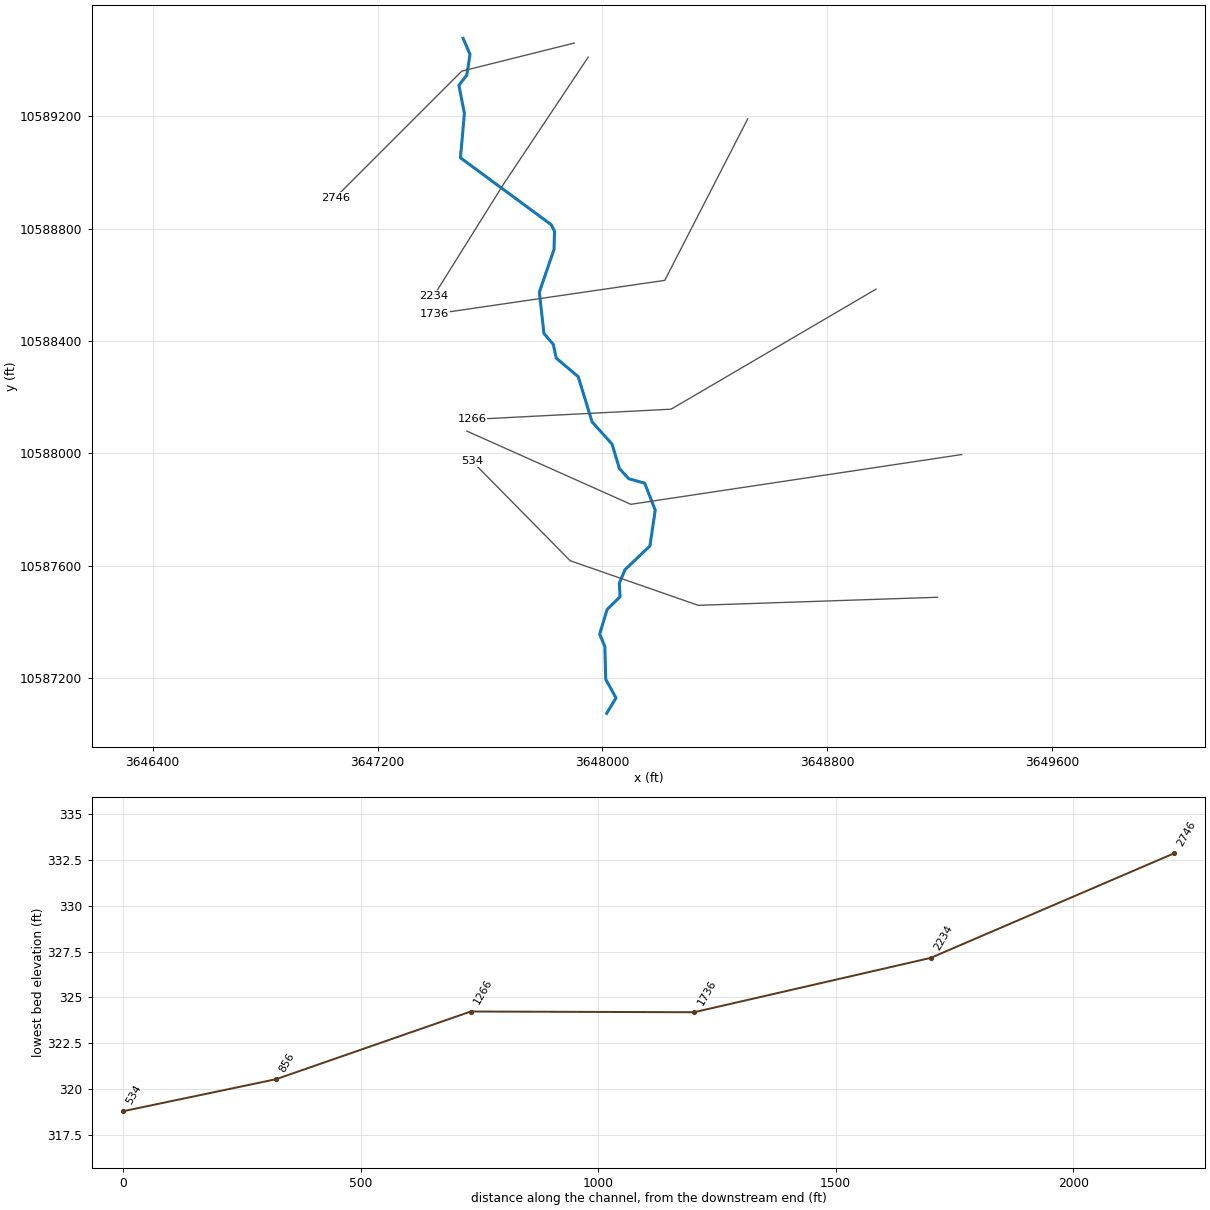
--- UNT 111 IN UKCR.prj (project) ---

Proj Title=UNT 111 IN UKCR Base Level Engineering
Current Plan=p01
Default Exp/Contr=0.3,0.1
English Units
Geom File=g01
Flow File=f01
Plan File=p01
Y Axis Title=Elevation
X Axis Title(PF)=Main Channel Distance
X Axis Title(XS)=Station
BEGIN DESCRIPTION:
UNT 111 IN UKCR
END DESCRIPTION:
DSS Export Rating Curves= 0
DSS Export Rating Curve Sorted= 0
DSS Export Volume Flow Curves= 0
DXF OffsetX= 0
DXF OffsetY= 0
DXF ScaleX= 1
DXF ScaleY= 10

--- UNT 111 IN UKCR.p01 (plan) ---

Plan Title=Multiple Run
Short Identifier=Multiple
Geom File=g01
Flow File=f01
Subcritical Flow
K Sum by GR= 0
Std Step Tol= 0.01
Critical Tol= 0.01
Num of Std Step Trials= 20
Max Error Tol= 0.3
Flow Tol Ratio= 0.001
Split Flow NTrial= 30
Split Flow Tol= 0.02
Split Flow Ratio= 0.02
Log Output Level= 0
Friction Slope Method= 1
Unsteady Friction Slope Method= 2
Unsteady Bridges Friction Slope Method= 1
Parabolic Critical Depth
Global Vel Dist=  1 , 1 , 1
Global Log Level= 0
CheckData=True
Encroach Param= -1, 0, 0, 0
BEGIN DESCRIPTION:
Multiple Run
END DESCRIPTION:

--- UNT 111 IN UKCR.f01 (steady flow) ---

Flow Title=Multiple
Number of Profiles=7
Profile Names=10-year,25-year,50-year,1pct_min,100-year,1pct_plu,500-year
River Rch & RM= UNT 111 IN UKCR,Reach-1,2746
     615     848    1044     947    1281    1732    1932
Boundary for River Rch & Prof#=UNT 111 IN UKCR,Reach-1,1
Up Type=0
Dn Type=3
Dn Slope=0.005
Boundary for River Rch & Prof#=UNT 111 IN UKCR,Reach-1,2
Up Type=0
Dn Type=3
Dn Slope=0.005
Boundary for River Rch & Prof#=UNT 111 IN UKCR,Reach-1,3
Up Type=0
Dn Type=3
Dn Slope=0.005
Boundary for River Rch & Prof#=UNT 111 IN UKCR,Reach-1,4
Up Type=0
Dn Type=3
Dn Slope=0.005
Boundary for River Rch & Prof#=UNT 111 IN UKCR,Reach-1,5
Up Type=0
Dn Type=3
Dn Slope=0.005
Boundary for River Rch & Prof#=UNT 111 IN UKCR,Reach-1,6
Up Type=0
Dn Type=3
Dn Slope=0.005
Boundary for River Rch & Prof#=UNT 111 IN UKCR,Reach-1,7
Up Type=0
Dn Type=3
Dn Slope=0.005

--- UNT 111 IN UKCR.g01 (geometry) ---

Geom Title=Existing Conditions
Program Version=4.10

River Reach=UNT 111 IN UKCR ,Reach-1
Reach XY= 30
       3647504.5       10589477.        3647529.       10589420.
       3647517.5       10589346.       3647489.5       10589310.
        3647509.       10589210.        3647495.       10589052.
      3647817.75       10588814.      3647829.75       10588791.
        3647828.       10588726.      3647775.75       10588574.
        3647792.       10588427.      3647825.25       10588388.
        3647836.       10588339.        3647914.       10588273.
       3647963.5       10588112.       3648034.5       10588033.
      3648060.25       10587947.       3648093.5       10587910.
      3648150.75       10587894.        3648188.       10587798.
      3648169.25       10587671.      3648080.25       10587586.
      3648060.25       10587538.        3648063.       10587490.
        3648017.       10587445.      3647990.25       10587357.
      3648008.75       10587313.        3648012.       10587196.
       3648048.5       10587130.      3648015.25       10587075.

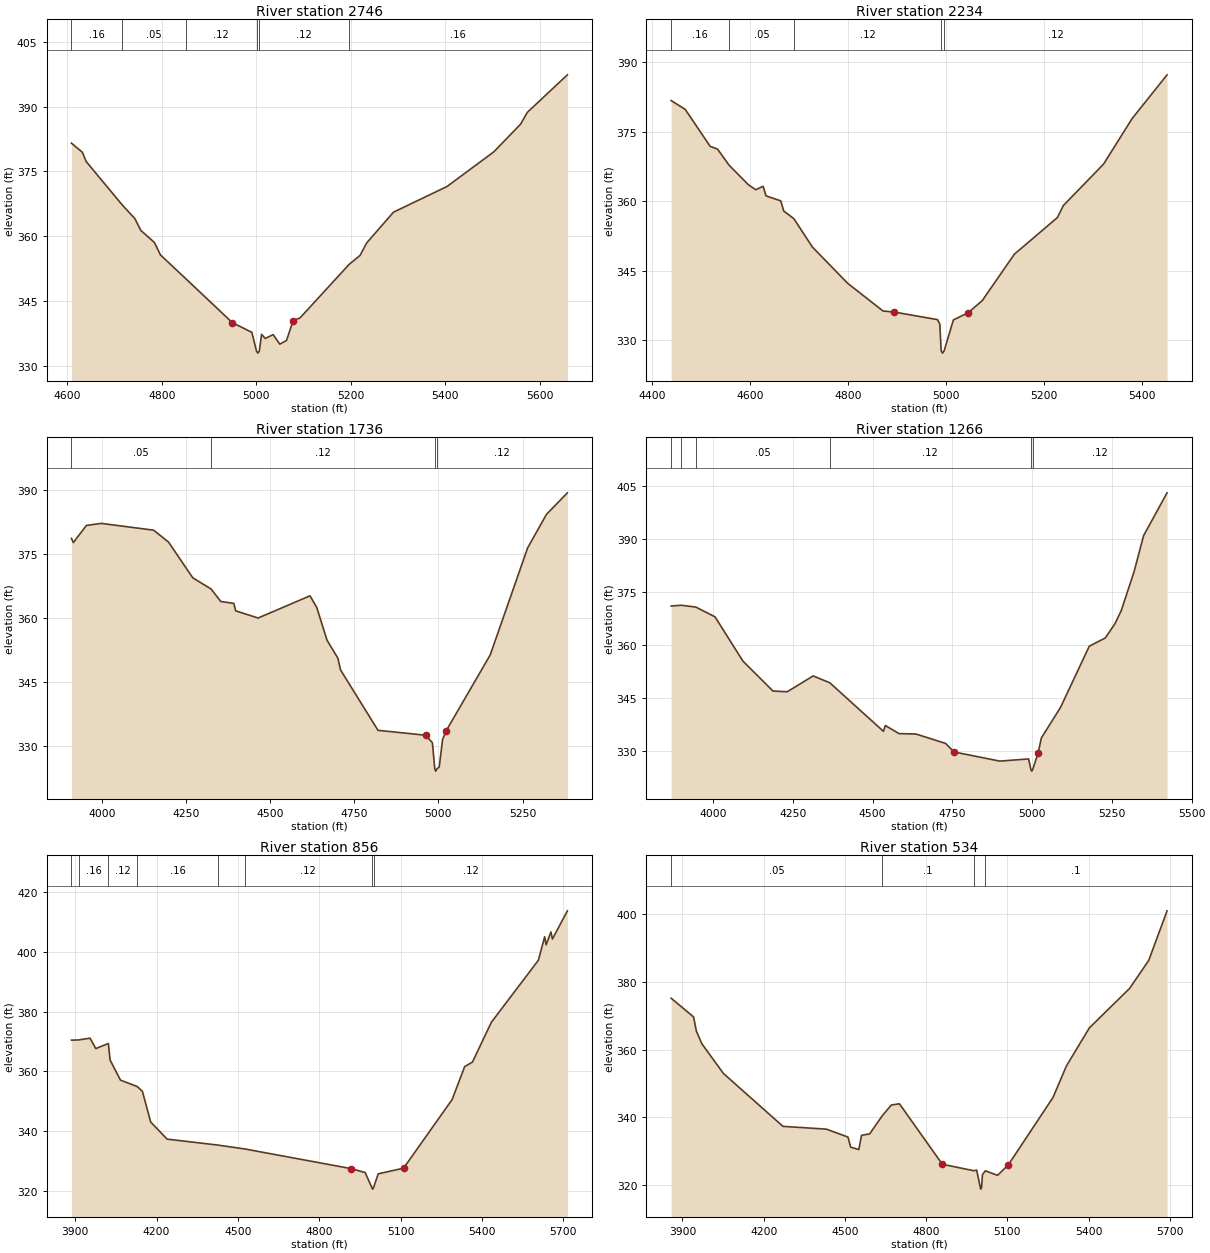
Type RM Length L Ch R = 1 ,2746    ,512,512,512
BEGIN DESCRIPTION:
UNT 111 IN UKCR 6.0
END DESCRIPTION:
XS GIS Cut Line= 3
      3647899.65      10589460.2      3647499.61     10589360.19
      3647049.64     10588910.22
#Sta/Elev= 30
  4609.2  381.57  4632.4  379.44  4640.2  377.33  4716.9   367.2  4743.2  364.08
  4756.1  361.31  4784.5  358.55  4797.4  355.65  4851.4  350.09  4949.4  339.94
  4990.6   337.7  5000.5  333.37  5003.3  332.87  5006.5  333.37  5011.2  337.22
    5019  336.28  5035.7  337.16  5049.8  334.95    5064  335.82  5078.1  340.43
  5092.3  341.01  5196.3  353.45  5219.5  355.53  5233.7  358.47  5290.3  365.57
  5403.4  371.52  5502.4  379.56    5559  385.98  5573.1   388.7  5657.9  397.42
#Mann= 6 ,-1 , 0
  4609.2     .16       0  4716.9     .05       0  4851.4     .12       0
  5000.5     .07       0  5006.5     .12       0  5196.3     .16       0
Bank Sta=4949.4,5078.1
XS Rating Curve= 0 ,0
Exp/Cntr=0.3,0.1

Type RM Length L Ch R = 1 ,2234    ,498,498,498
BEGIN DESCRIPTION:
UNT 111 IN UKCR 5.0
END DESCRIPTION:
XS GIS Cut Line= 3
      3647949.63     10589410.23      3647649.61     10588960.19
       3647399.6     10588560.17
#Sta/Elev= 30
  4438.9  381.71  4467.5  379.84  4518.6  371.83  4533.6  371.24  4557.1  367.77
  4596.7  363.53  4611.7  362.46  4626.7   363.2  4632.7  361.13  4662.8  360.05
  4668.8  357.86  4689.5   356.2  4727.4  350.07  4799.5  342.23  4871.6  336.26
  4894.1  336.04  4982.7   334.4  4987.4  333.48  4990.3  327.66  4993.1  327.16
  4996.3  327.66  5015.2  334.34  5045.2  335.87  5074.1   338.5  5139.6  348.52
  5227.4  356.43  5239.8  359.05  5321.8  367.99  5380.1  377.82  5451.5  387.28
#Mann= 5 ,-1 , 0
  4438.9     .16       0  4557.1     .05       0  4689.5     .12       0
  4990.3     .07       0  4996.3     .12       0
Bank Sta=4894.1,5045.2
XS Rating Curve= 0 ,0
Exp/Cntr=0.3,0.1

Type RM Length L Ch R = 1 ,1736    ,470,470,470
BEGIN DESCRIPTION:
UNT 111 IN UKCR 4.0
END DESCRIPTION:
XS GIS Cut Line= 3
      3648517.09     10589190.37      3648221.97     10588615.75
      3647402.71     10588496.24
#Sta/Elev= 30
  3909.4  378.61    3915  377.64  3953.8  381.65  3998.1  382.13  4153.4  380.55
  4197.8  377.77    4270   369.4  4324.5  366.78  4353.1  363.87  4391.9  363.42
  4397.5  361.68  4464.1     360  4618.4  365.19  4638.6  362.44  4668.9  354.83
  4701.1  350.62  4709.3  347.84  4820.5  333.73    4962  332.59  4982.2  330.83
  4989.3  324.69  4992.1  324.19  4995.3  324.69  5002.4  325.16  5012.5  331.62
  5022.6  333.56    5154  351.37  5265.2   376.4    5321  384.22  5383.3  389.28
#Mann= 4 ,-1 , 0
  3909.4     .05       0  4324.5     .12       0  4989.3     .07       0
  4995.3     .12       0
Bank Sta=4962,5022.6
XS Rating Curve= 0 ,0
Exp/Cntr=0.3,0.1

Type RM Length L Ch R = 1 ,1266    ,410,410,410
BEGIN DESCRIPTION:
UNT 111 IN UKCR 3.0
END DESCRIPTION:
XS GIS Cut Line= 3
      3648973.72     10588584.51      3648244.54     10588157.42
      3647536.23     10588120.96
#Sta/Elev= 30
  3868.6  370.92    3900  371.14  3946.2  370.62  4006.2  367.85  4093.6  355.34
  4187.9  346.87  4232.6  346.68  4313.7  351.15  4365.8  349.22  4533.9  335.49
  4539.9  337.13  4582.8  334.84  4635.7  334.73  4728.6  332.07  4755.3  329.65
  4898.8  327.06  4988.9  327.68    4996  324.73  4998.7  324.23    5002  324.73
    5019  329.47    5029  333.62  5089.1  342.27  5179.2  359.56  5229.3  361.89
  5259.3  365.89  5279.3  369.62  5319.4   380.6  5349.4  390.83  5422.9  402.93
#Mann= 6 ,-1 , 0
  3868.6     .05       0    3900     .08       0  3946.2     .05       0
  4365.8     .12       0    4996     .07       0    5002     .12       0
Bank Sta=4755.3,5019
XS Rating Curve= 0 ,0
Exp/Cntr=0.3,0.1

Type RM Length L Ch R = 1 ,856     ,322,322,322
BEGIN DESCRIPTION:
UNT 111 IN UKCR 2.0
END DESCRIPTION:
XS GIS Cut Line= 3
      3649278.43     10587995.97      3648101.31     10587818.88
      3647517.97      10588079.3
#Sta/Elev= 30
  3886.2  370.45  3912.3  370.51  3954.7  371.11    3976  367.63  4022.3  369.33
  4028.7  363.79    4067  357.05  4127.9  354.95  4147.9  353.31  4178.3  343.04
  4238.9  337.29  4426.2  335.29  4525.6  333.99  4916.5  327.42  4969.5  326.09
  4994.4  321.03  4997.1  320.53  5000.4  321.03  5017.6  325.65  5111.2  327.55
  5290.1  350.51  5336.6  361.59  5365.3   363.1  5434.9  376.42  5608.4  397.22
  5631.6  405.09  5637.1   402.4  5654.8  406.72  5660.3  404.33  5715.4  413.78
#Mann= 8 ,-1 , 0
  3886.2     .05       0  3912.3     .16       0  4022.3     .12       0
  4127.9     .16       0  4426.2     .05       0  4525.6     .12       0
  4994.4     .07       0  5000.4     .12       0
Bank Sta=4916.5,5111.2
XS Rating Curve= 0 ,0
Exp/Cntr=0.3,0.1

Type RM Length L Ch R = 1 ,534     ,0,0,0
BEGIN DESCRIPTION:
UNT 111 IN UKCR 1.0
END DESCRIPTION:
XS GIS Cut Line= 4
      3649192.45     10587488.15      3648340.89      10587459.5
      3647885.16     10587618.36      3647536.18     10587972.55
#Sta/Elev= 30
  3858.2  375.15  3941.1  369.61  3951.2  365.47  3971.1  361.77  4051.2  352.93
  4271.3  337.31  4431.4  336.49  4511.4  334.15  4521.4  331.16  4551.4  330.47
  4561.4  334.66  4591.5   335.1  4638.6   340.5  4671.5  343.61  4701.5  343.98
  4859.9  326.13  4976.4  324.21  4986.9  324.38  5001.6  318.78  5004.9  319.28
  5008.1  323.04  5018.7  324.19    5064  322.86  5103.4  325.91  5268.8  345.85
  5318.3  355.14  5403.2   366.4  5551.6  378.02  5622.4   386.3  5690.1  400.94
#Mann= 4 ,-1 , 0
  3858.2     .05       0  4638.6      .1       0  4976.4     .05       0
  5018.7      .1       0
Bank Sta=4859.9,5103.4
XS Rating Curve= 0 ,0
Exp/Cntr=0.3,0.1

Chan Stop Cuts=-1
Use User Specified Reach Order=0
Composite Channel Slope=5