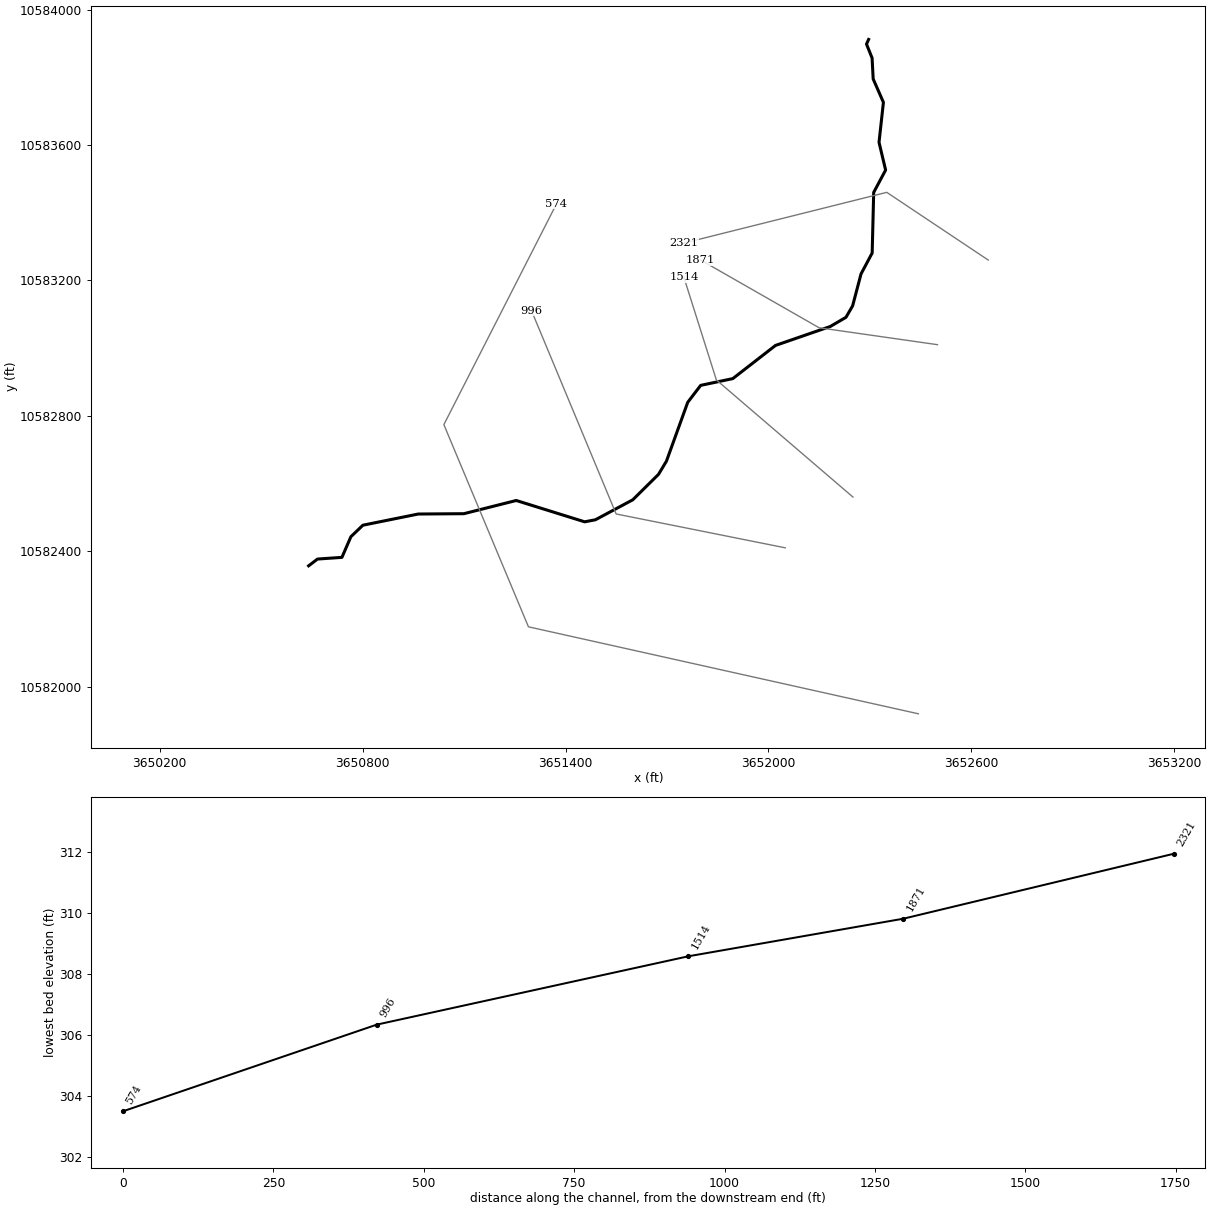
--- UNT 114 IN UKCR.prj (project) ---

Proj Title=UNT 114 IN UKCR Base Level Engineering
Current Plan=p01
Default Exp/Contr=0.3,0.1
English Units
Geom File=g01
Flow File=f01
Plan File=p01
BEGIN DESCRIPTION:
UNT 114 IN UKCR
END DESCRIPTION:

--- UNT 114 IN UKCR.p01 (plan) ---

Plan Title=Multiple Run
Short Identifier=Multiple
Geom File=g01
Flow File=f01
Subcritical Flow
K Sum by GR= 0
Std Step Tol= 0.01
Critical Tol= 0.01
Num of Std Step Trials= 20
Max Error Tol= 0.3
Flow Tol Ratio= 0.001
Split Flow NTrial= 30
Split Flow Tol= 0.02
Split Flow Ratio= 0.02
Log Output Level= 0
Friction Slope Method= 1
Unsteady Friction Slope Method= 2
Unsteady Bridges Friction Slope Method= 1
Parabolic Critical Depth
Global Vel Dist=  1 , 1 , 1
Global Log Level= 0
CheckData=True
Encroach Param= -1, 0, 0, 0
BEGIN DESCRIPTION:
Multiple Run
END DESCRIPTION:

--- UNT 114 IN UKCR.f01 (steady flow) ---

Flow Title=Multiple
Number of Profiles=7
Profile Names=10-year,25-year,50-year,1pct_min,100-year,1pct_plu,500-year
River Rch & RM= UNT 114 IN UKCR,Reach-1,2321
     475     636     768     681     921    1246    1330
Boundary for River Rch & Prof#=UNT 114 IN UKCR,Reach-1,1
Up Type=0
Dn Type=3
Dn Slope=0.005
Boundary for River Rch & Prof#=UNT 114 IN UKCR,Reach-1,2
Up Type=0
Dn Type=3
Dn Slope=0.005
Boundary for River Rch & Prof#=UNT 114 IN UKCR,Reach-1,3
Up Type=0
Dn Type=3
Dn Slope=0.005
Boundary for River Rch & Prof#=UNT 114 IN UKCR,Reach-1,4
Up Type=0
Dn Type=3
Dn Slope=0.005
Boundary for River Rch & Prof#=UNT 114 IN UKCR,Reach-1,5
Up Type=0
Dn Type=3
Dn Slope=0.005
Boundary for River Rch & Prof#=UNT 114 IN UKCR,Reach-1,6
Up Type=0
Dn Type=3
Dn Slope=0.005
Boundary for River Rch & Prof#=UNT 114 IN UKCR,Reach-1,7
Up Type=0
Dn Type=3
Dn Slope=0.005

--- UNT 114 IN UKCR.g01 (geometry) ---

Geom Title=Existing Conditions

River Reach=UNT 114 IN UKCR,Reach-1
Reach XY= 30
      3652295.97     10583911.83      3652289.75     10583898.00
      3652306.25     10583857.00      3652309.50     10583795.00
      3652339.75     10583726.00      3652326.75     10583608.00
      3652346.25     10583526.00      3652311.00     10583460.00
      3652306.50     10583281.00      3652273.50     10583219.00
      3652248.75     10583125.00      3652229.00     10583091.00
      3652182.75     10583064.00      3652020.75     10583008.00
      3651894.50     10582910.00      3651799.50     10582890.00
      3651761.25     10582840.00      3651698.25     10582666.00
      3651674.75     10582627.00      3651598.75     10582552.00
      3651488.25     10582493.00      3651456.50     10582487.00
      3651254.25     10582550.00      3651099.50     10582511.00
      3650964.50     10582510.00      3650801.00     10582477.00
      3650765.50     10582443.00      3650739.00     10582382.00
      3650666.75     10582377.00      3650640.50     10582357.00

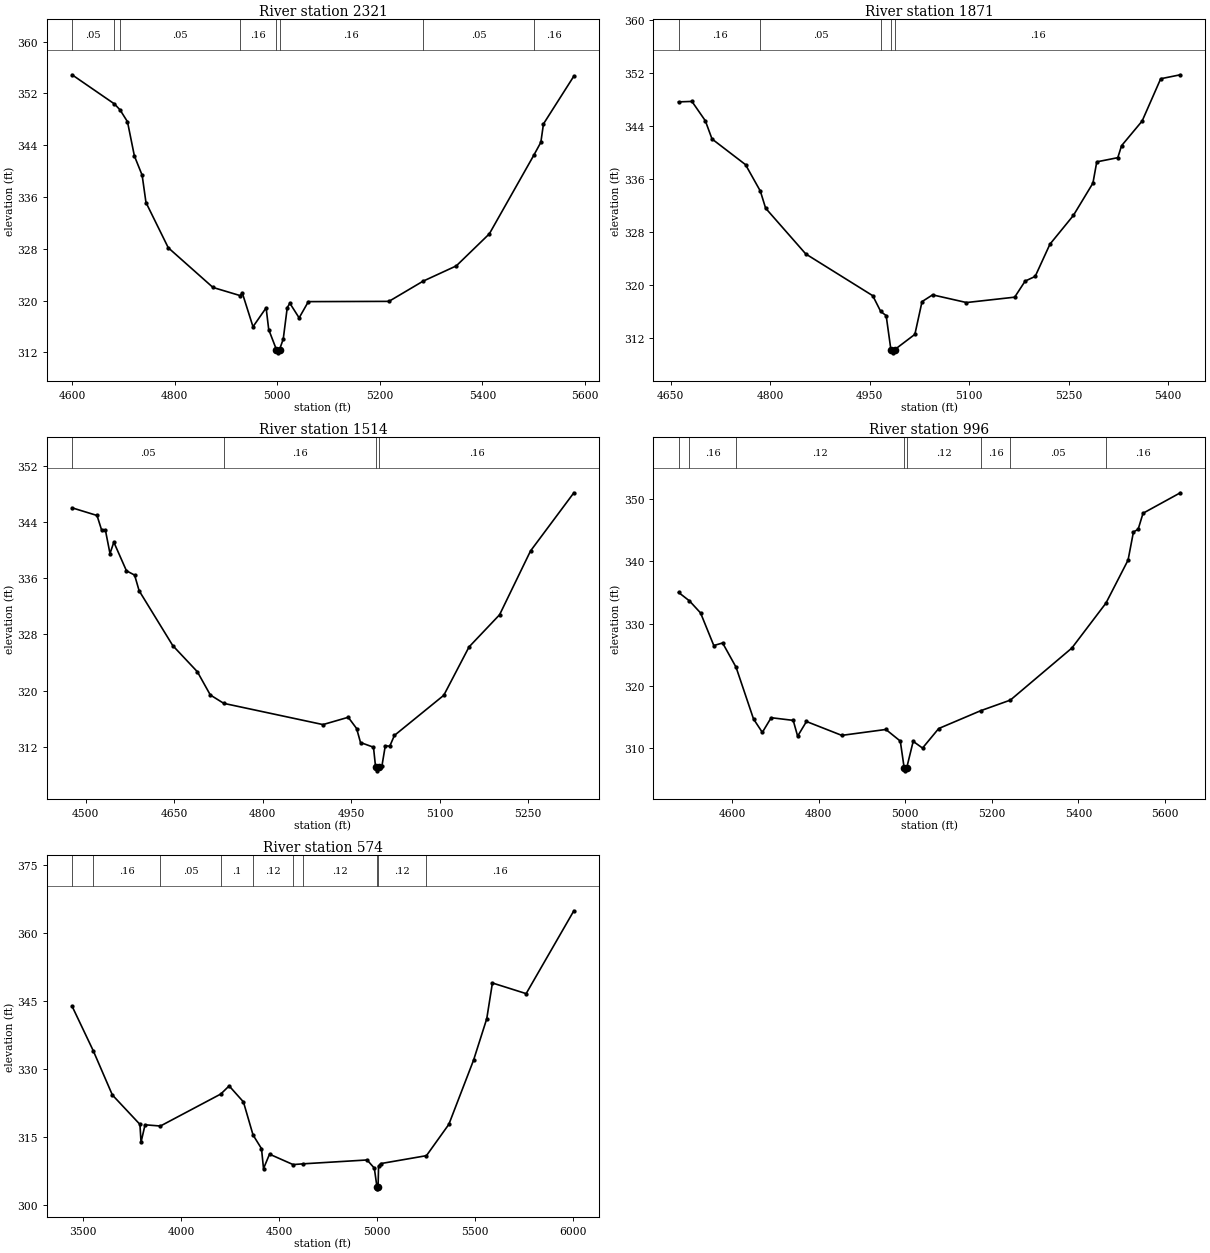
Type RM Length L Ch R = 1,2321,450,450,450
BEGIN DESCRIPTION:
UNT 114 IN UKCR 5.0
END DESCRIPTION:
XS GIS Cut Line= 3
      3652649.57     10583260.21      3652349.61     10583460.19
      3651749.59     10583310.18
#Sta/Elev= 30
  4599.6  354.89  4682.2  350.39  4693.1  349.48  4707.7  347.64  4721.2  342.35
  4736.3  339.38  4743.8  335.16  4787.3  328.17  4874.5  322.04  4927.6  320.78
  4931.6  321.22  4952.6  315.97  4978.2  318.89  4983.3  315.52  4998.3  312.44
  5001.1  311.94  5004.3  312.44  5011.6  314.06  5019.4  318.92  5024.5  319.60
  5042.6  317.34  5060.6  319.85  5217.8  319.89  5284.2  323.00  5349.2  325.37
  5413.7  330.32  5500.5  342.47  5514.2  344.46  5519.3  347.30  5578.6  354.68
#Mann=8,-1,0
  4599.6    0.05       0  4682.2    0.16       0  4693.1    0.05       0
  4927.6    0.16       0  4998.3    0.07       0  5004.3    0.16       0
  5284.2    0.05       0  5500.5    0.16       0
Bank Sta=4998.3,5004.3
Exp/Cntr=0.3,0.1

Type RM Length L Ch R = 1,1871,357,357,357
BEGIN DESCRIPTION:
UNT 114 IN UKCR 4.0
END DESCRIPTION:
XS GIS Cut Line= 3
      3652499.60     10583010.19      3652149.61     10583060.19
      3651799.57     10583260.21
#Sta/Elev= 30
  4661.6  347.68  4681.8  347.75  4702.0  344.83  4712.1  342.08  4762.6  338.21
  4785.0  334.21  4792.9  331.64  4853.5  324.73  4954.5  318.43  4966.5  316.05
  4974.7  315.43  4981.8  310.31  4984.6  309.81  4987.8  310.31  5018.0  312.60
  5028.8  317.54  5044.7  318.56  5095.8  317.40  5168.5  318.21  5184.3  320.64
  5199.4  321.34  5221.7  326.21  5257.0  330.54  5286.5  335.42  5292.3  338.63
  5324.0  339.26  5329.7  341.07  5360.7  344.79  5388.7  351.17  5418.3  351.77
#Mann=5,-1,0
  4661.6    0.16       0  4785.0    0.05       0  4966.5    0.16       0
  4981.8    0.07       0  4987.8    0.16       0
Bank Sta=4981.8,4987.8
Exp/Cntr=0.3,0.1

Type RM Length L Ch R = 1,1514,518,518,518
BEGIN DESCRIPTION:
UNT 114 IN UKCR 3.0
END DESCRIPTION:
XS GIS Cut Line= 3
      3652249.65     10582560.16      3651845.90     10582906.06
      3651749.60     10583210.22
#Sta/Elev= 30
  4476.7  346.00  4519.0  344.91  4526.7  342.86  4533.3  342.79  4541.0  339.49
  4547.5  341.11  4568.9  337.04  4582.7  336.43  4590.4  334.20  4647.4  326.40
  4689.1  322.68  4711.1  319.37  4733.9  318.18  4902.1  315.16  4944.9  316.20
  4959.1  314.60  4965.7  312.61  4987.7  311.94  4991.3  309.08  4994.0  308.58
  4997.3  309.08  5002.0  309.26  5007.7  312.14  5015.3  312.09  5023.2  313.62
  5106.9  319.33  5149.7  326.21  5201.5  330.79  5253.9  339.86  5327.4  348.14
#Mann=4,-1,0
  4476.7    0.05       0  4733.9    0.16       0  4991.3    0.07       0
  4997.3    0.16       0
Bank Sta=4991.3,4997.3
Exp/Cntr=0.3,0.1

Type RM Length L Ch R = 1,996,422,422,422
BEGIN DESCRIPTION:
UNT 114 IN UKCR 2.0
END DESCRIPTION:
XS GIS Cut Line= 3
      3652049.57     10582410.20      3651549.61     10582510.19
      3651299.59     10583110.23
#Sta/Elev= 30
  4475.7  335.02  4501.0  333.65  4526.6  331.72  4557.2  326.48  4577.6  326.89
  4608.7  322.99  4649.0  314.68  4669.4  312.52  4689.8  314.88  4740.8  314.45
  4751.0  311.91  4771.4  314.27  4853.0  312.04  4955.0  312.99  4988.3  311.12
  4997.2  306.84  4999.9  306.34  5003.2  306.84  5018.1  311.08  5039.7  310.00
  5077.1  313.14  5174.0  316.00  5242.7  317.71  5384.8  326.07  5463.7  333.30
  5514.8  340.21  5527.2  344.73  5538.1  345.16  5549.4  347.74  5635.6  351.03
#Mann=8,-1,0
  4475.7    0.05       0  4501.0    0.16       0  4608.7    0.12       0
  4997.2    0.07       0  5003.2    0.12       0  5174.0    0.16       0
  5242.7    0.05       0  5463.7    0.16       0
Bank Sta=4997.2,5003.2
Exp/Cntr=0.3,0.1

Type RM Length L Ch R = 1,574,0,0,0
BEGIN DESCRIPTION:
UNT 114 IN UKCR 1.0
END DESCRIPTION:
XS GIS Cut Line= 4
      3652443.08     10581919.96      3651290.35     10582176.89
      3651040.35     10582774.11      3651373.26     10583426.07
#Sta/Elev= 30
  3444.5  343.80  3552.4  333.99  3650.1  324.21  3790.8  317.72  3796.4  313.78
  3816.9  317.63  3895.3  317.36  4203.4  324.42  4246.0  326.21  4318.9  322.68
  4368.0  315.38  4411.1  312.37  4421.4  307.97  4452.1  311.15  4572.4  308.85
  4623.9  309.02  4950.0  309.87  4986.8  308.07  5000.0  304.00  5002.8  303.50
  5006.0  304.00  5008.5  308.51  5019.4  309.07  5252.8  310.82  5367.1  317.73
  5493.1  331.88  5560.5  341.03  5589.4  348.92  5761.5  346.57  6005.0  364.85
#Mann=10,-1,0
  3444.5    0.12       0  3552.4    0.16       0  3895.3    0.05       0
  4203.4     0.1       0  4368.0    0.12       0  4572.4    0.16       0
  4623.9    0.12       0  5000.0    0.07       0  5006.0    0.12       0
  5252.8    0.16       0
Bank Sta=5000,5006
Exp/Cntr=0.3,0.1

Chan Stop Cuts=-1