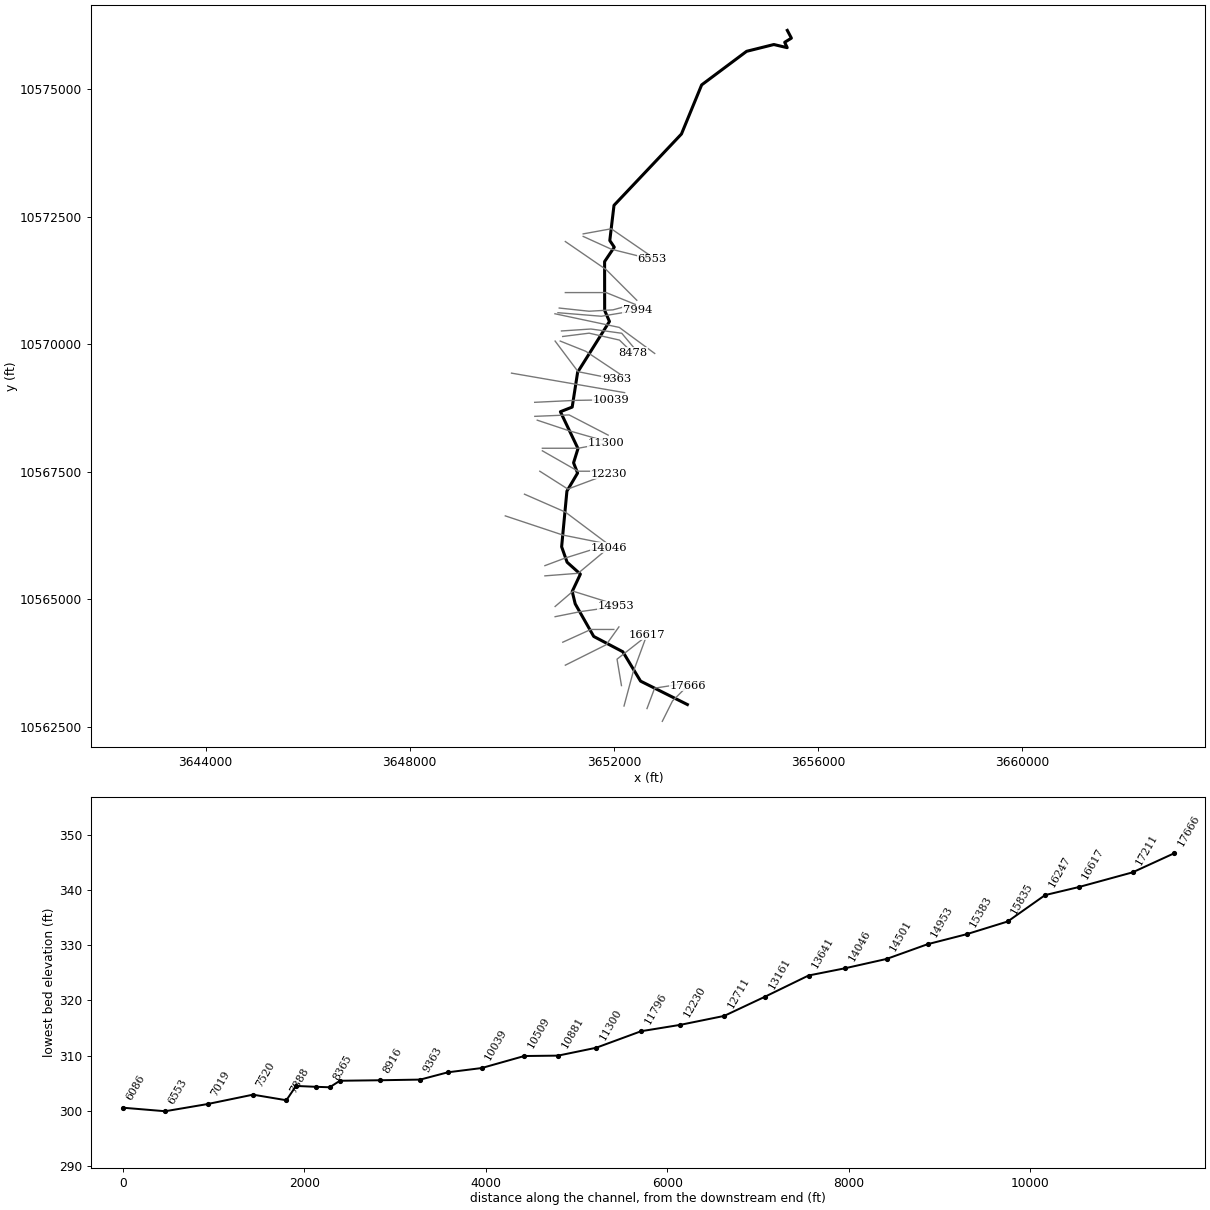
--- UNT 116 IN UKCR.prj (project) ---

Proj Title=UNT 116 IN UKCR Base Level Engineering
Current Plan=p01
Default Exp/Contr=0.3,0.1
English Units
Geom File=g01
Flow File=f01
Plan File=p01
Y Axis Title=Elevation
X Axis Title(PF)=Main Channel Distance
X Axis Title(XS)=Station
BEGIN DESCRIPTION:
UNT 116 IN UKCR
END DESCRIPTION:
DSS Export Rating Curves= 0
DSS Export Rating Curve Sorted= 0
DSS Export Volume Flow Curves= 0
DXF OffsetX= 0
DXF OffsetY= 0
DXF ScaleX= 1
DXF ScaleY= 10

--- UNT 116 IN UKCR.p01 (plan) ---

Plan Title=Multiple Run
Short Identifier=Multiple
Geom File=g01
Flow File=f01
Subcritical Flow
K Sum by GR= 0
Std Step Tol= 0.01
Critical Tol= 0.01
Num of Std Step Trials= 20
Max Error Tol= 0.3
Flow Tol Ratio= 0.001
Split Flow NTrial= 30
Split Flow Tol= 0.02
Split Flow Ratio= 0.02
Log Output Level= 0
Friction Slope Method= 1
Unsteady Friction Slope Method= 2
Unsteady Bridges Friction Slope Method= 1
Parabolic Critical Depth
Global Vel Dist=  1 , 1 , 1
Global Log Level= 0
CheckData=True
Encroach Param= -1, 0, 0, 0
BEGIN DESCRIPTION:
Multiple Run
END DESCRIPTION:

--- UNT 116 IN UKCR.f01 (steady flow) ---

Flow Title=Multiple
Program Version=4.10
Number of Profiles= 7
Profile Names=10-year,25-year,50-year,1pct_min,100-year,1pct_plu,500-year
River Rch & RM=UNT 116 IN UKCR,Reach-1         ,17666
     875    1225    1522    1389    1879    2541    2877
River Rch & RM=UNT 116 IN UKCR,Reach-1         ,13161
    1444    2056    2584    2379    3217    4351    5013
River Rch & RM=UNT 116 IN UKCR,Reach-1         ,11796
    1444    2056    2584    2379    3217    4351    5013
River Rch & RM=UNT 116 IN UKCR,Reach-1         ,3466
    1538    2193    2759    2542    3438    4649    5365
Boundary for River Rch & Prof#=UNT 116 IN UKCR,Reach-1         , 1
Up Type= 0
Dn Type= 3
Dn Slope=0.005
Boundary for River Rch & Prof#=UNT 116 IN UKCR,Reach-1         , 2
Up Type= 0
Dn Type= 3
Dn Slope=0.005
Boundary for River Rch & Prof#=UNT 116 IN UKCR,Reach-1         , 3
Up Type= 0
Dn Type= 3
Dn Slope=0.005
Boundary for River Rch & Prof#=UNT 116 IN UKCR,Reach-1         , 4
Up Type= 0
Dn Type= 3
Dn Slope=0.005
Boundary for River Rch & Prof#=UNT 116 IN UKCR,Reach-1         , 5
Up Type= 0
Dn Type= 3
Dn Slope=0.005
Boundary for River Rch & Prof#=UNT 116 IN UKCR,Reach-1         , 6
Up Type= 0
Dn Type= 3
Dn Slope=0.005
Boundary for River Rch & Prof#=UNT 116 IN UKCR,Reach-1         , 7
Up Type= 0
Dn Type= 3
Dn Slope=0.005
DSS Import GetInterval= 0
DSS Import GetPeak= 0
DSS Import FillOption= 0

--- UNT 116 IN UKCR.g01 (geometry) ---

Geom Title=Existing Conditions
Program Version=4.10

River Reach=UNT 116 IN UKCR ,Reach-1
Reach XY= 30
        3653441.       10562939.       3652523.5       10563398.
      3652176.25       10563973.      3651606.25       10564273.
      3651243.25       10564912.       3651184.5       10565154.
       3651344.5       10565494.       3651084.5       10565727.
      3650977.25       10566030.      3651080.75       10567120.
      3651289.75       10567474.        3651211.       10567675.
      3651297.75       10567954.      3650953.25       10568676.
      3651184.25       10568767.      3651290.75       10569450.
      3651914.25       10570444.      3651820.25       10570660.
        3651819.       10571617.      3652008.75       10571900.
      3651920.75       10572030.      3652003.25       10572719.
      3653324.75       10574117.       3653720.5       10575079.
      3654601.25       10575737.      3655135.25       10575870.
      3655396.75       10575808.      3655347.25       10575914.
        3655479.       10575995.      3655398.75       10576147.

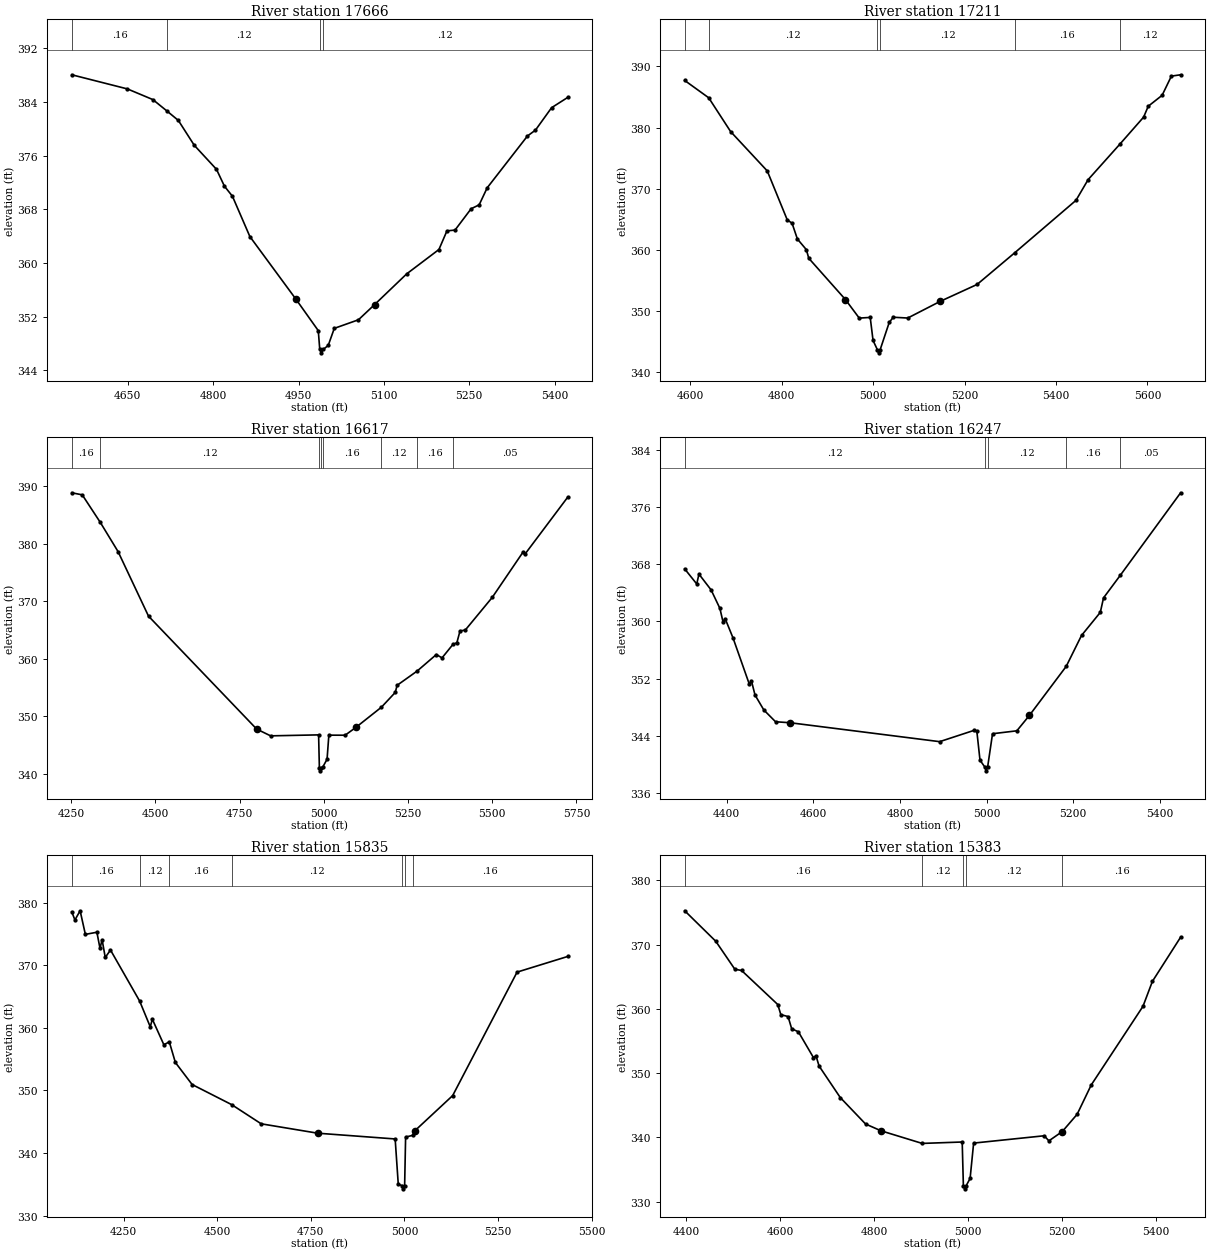
Type RM Length L Ch R = 1 ,17666   ,455,455,455
BEGIN DESCRIPTION:
UNT 116 IN UKCR 36.0
END DESCRIPTION:
XS GIS Cut Line= 3
      3652949.61      10562610.2      3653149.61     10563010.19
      3653449.63     10563310.21
#Sta/Elev= 30
  4551.5  388.08  4649.3  385.97    4694  384.38  4719.3  382.64  4738.8  381.27
  4766.7  377.57  4805.8  373.98  4819.8  371.46  4833.8  369.97  4864.5  363.95
  4945.6  354.59  4984.7  349.92  4987.3  347.11  4990.1  346.61  4993.3  347.11
  5002.2  347.72  5012.8  350.26  5055.3  351.54  5083.6   353.8  5140.1  358.39
  5196.7  362.02  5210.8   364.8    5225  364.92  5253.3   368.1  5267.4  368.68
  5281.5  371.22  5352.3  378.95  5366.4  379.83  5394.7  383.17    5423   384.7
#Mann= 4 ,-1 , 0
  4551.5     .16       0  4719.3     .12       0  4987.3     .07       0
  4993.3     .12       0
Bank Sta=4945.6,5083.6
XS Rating Curve= 0 ,0
Exp/Cntr=0.3,0.1

Type RM Length L Ch R = 1 ,17211   ,594,594,594
BEGIN DESCRIPTION:
UNT 116 IN UKCR 35.0
END DESCRIPTION:
XS GIS Cut Line= 3
      3652649.63     10562860.23      3652799.61     10563260.19
      3653449.61     10563360.19
#Sta/Elev= 30
  4587.9  387.71  4640.4  384.88  4688.4  379.35  4768.5  372.92  4812.1  364.94
  4822.8  364.36  4834.4  361.79    4854  360.05  4859.3  358.64  4939.4   351.9
  4969.7  348.86  4993.7  348.97  4999.9  345.21  5009.4  343.68  5012.1  343.18
  5015.4  343.68  5035.3  348.15  5044.1     349  5075.8  348.87  5146.6  351.59
  5227.5  354.36  5310.3  359.57  5443.8  368.11  5470.3  371.49  5539.5  377.27
  5591.8  381.72  5601.9   383.5  5632.2  385.28  5652.5  388.42  5672.7  388.64
#Mann= 6 ,-1 , 0
  4587.9     .16       0  4640.4     .12       0  5009.4     .07       0
  5015.4     .12       0  5310.3     .16       0  5539.5     .12       0
Bank Sta=4939.4,5146.6
XS Rating Curve= 0 ,0
Exp/Cntr=0.3,0.1

Type RM Length L Ch R = 1 ,16617   ,370,370,370
BEGIN DESCRIPTION:
UNT 116 IN UKCR 34.0
END DESCRIPTION:
XS GIS Cut Line= 3
       3652199.6     10562910.17       3652375.1     10563564.38
      3652649.62     10564310.22
#Sta/Elev= 30
    4252  388.83  4283.1  388.47  4336.6  383.69  4389.5   378.6  4479.8  367.39
  4800.8  347.77  4842.2  346.59  4984.7  346.76    4987  341.01  4989.7  340.51
    4993  341.01  4997.4  341.21  5009.8  342.52  5015.1  346.71  5063.4   346.7
  5095.4  348.06  5171.2  351.57  5212.3  354.14  5217.7  355.37  5277.2  357.85
  5334.2  360.72  5351.1  360.14  5383.3  362.47  5395.1  362.77  5404.4  364.81
  5420.2  364.98  5500.3  370.66  5592.3  378.59  5597.7   378.2  5724.1  388.06
#Mann= 8 ,-1 , 0
    4252     .16       0  4336.6     .12       0    4987     .07       0
    4993     .12       0  4997.4     .16       0  5171.2     .12       0
  5277.2     .16       0  5383.3     .05       0
Bank Sta=4800.8,5095.4
XS Rating Curve= 0 ,0
Exp/Cntr=0.3,0.1

Type RM Length L Ch R = 1 ,16247   ,412,412,412
BEGIN DESCRIPTION:
UNT 116 IN UKCR 33.0
END DESCRIPTION:
XS GIS Cut Line= 3
      3652149.61     10563310.16       3652062.6     10563828.27
      3652549.63     10564210.21
#Sta/Elev= 30
  4303.4  367.36  4331.2  365.25  4336.3  366.63  4364.3  364.42  4384.6  361.83
  4391.8  359.94  4396.9  360.37    4415  357.67  4452.4  351.22  4457.5  351.64
  4465.7  349.68    4486  347.59    4513  345.94  4546.8   345.8  4891.7  343.15
  4970.4  344.72  4977.5  344.61  4984.8  340.55  4996.3  339.56    4999  339.06
  5002.3  339.56  5013.7  344.26  5069.8  344.67  5098.7  346.82  5183.7   353.7
    5219  358.03  5262.4  361.27  5269.8   363.3  5308.7  366.48  5447.7  378.03
#Mann= 5 ,-1 , 0
  4303.4     .12       0  4996.3     .07       0  5002.3     .12       0
  5183.7     .16       0  5308.7     .05       0
Bank Sta=4546.8,5098.7
XS Rating Curve= 0 ,0
Exp/Cntr=0.3,0.1

Type RM Length L Ch R = 1 ,15835   ,452,452,452
BEGIN DESCRIPTION:
UNT 116 IN UKCR 32.0
END DESCRIPTION:
XS GIS Cut Line= 3
      3651049.63      10563710.2      3651849.61     10564110.19
       3652099.6     10564460.17
#Sta/Elev= 30
  4111.5  378.54  4119.9  377.24  4133.8  378.71  4147.8  374.94  4178.6  375.28
  4186.9   372.7  4192.5  374.09  4200.9  371.25  4214.9  372.44  4292.8  364.28
  4321.1  360.17  4326.7  361.38  4357.4  357.31    4372  357.76  4388.2  354.47
  4432.9  350.95  4538.7  347.73  4617.4  344.67  4768.3  343.17  4975.2  342.25
  4983.5     335  4994.5  334.78  4997.3  334.28  5000.5  334.78  5003.1  342.55
  5022.8  342.84    5028  343.57  5128.8  349.18  5300.8  368.91    5436  371.41
#Mann= 7 ,-1 , 0
  4111.5     .16       0  4292.8     .12       0    4372     .16       0
  4538.7     .12       0  4994.5     .07       0  5000.5     .12       0
  5022.8     .16       0
Bank Sta=4768.3,5028
XS Rating Curve= 0 ,0
Exp/Cntr=0.3,0.1

Type RM Length L Ch R = 1 ,15383   ,430,430,430
BEGIN DESCRIPTION:
UNT 116 IN UKCR 31.0
END DESCRIPTION:
XS GIS Cut Line= 3
      3650999.57     10564160.17      3651549.61     10564410.19
      3651999.61     10564410.19
#Sta/Elev= 30
  4397.6  375.26  4463.6  370.52  4504.2  366.16  4518.5  365.97  4595.4  360.67
    4602  359.09  4617.3   358.8    4625   356.9  4639.3  356.42  4671.2  352.42
  4676.7  352.69  4683.2   351.1  4728.3  346.19  4782.1  342.07  4815.1  341.01
  4902.4  339.05  4987.5  339.27    4990  332.48  4992.8  331.98    4996  332.48
  5004.3   333.6  5011.8   339.1  5161.8  340.24  5171.8  339.45  5200.3   340.9
  5231.8  343.58  5261.8  348.15  5371.8  360.39  5391.8  364.27  5451.8  371.15
#Mann= 5 ,-1 , 0
  4397.6     .16       0  4902.4     .12       0    4990     .07       0
    4996     .12       0  5200.3     .16       0
Bank Sta=4815.1,5200.3
XS Rating Curve= 0 ,0
Exp/Cntr=0.3,0.1

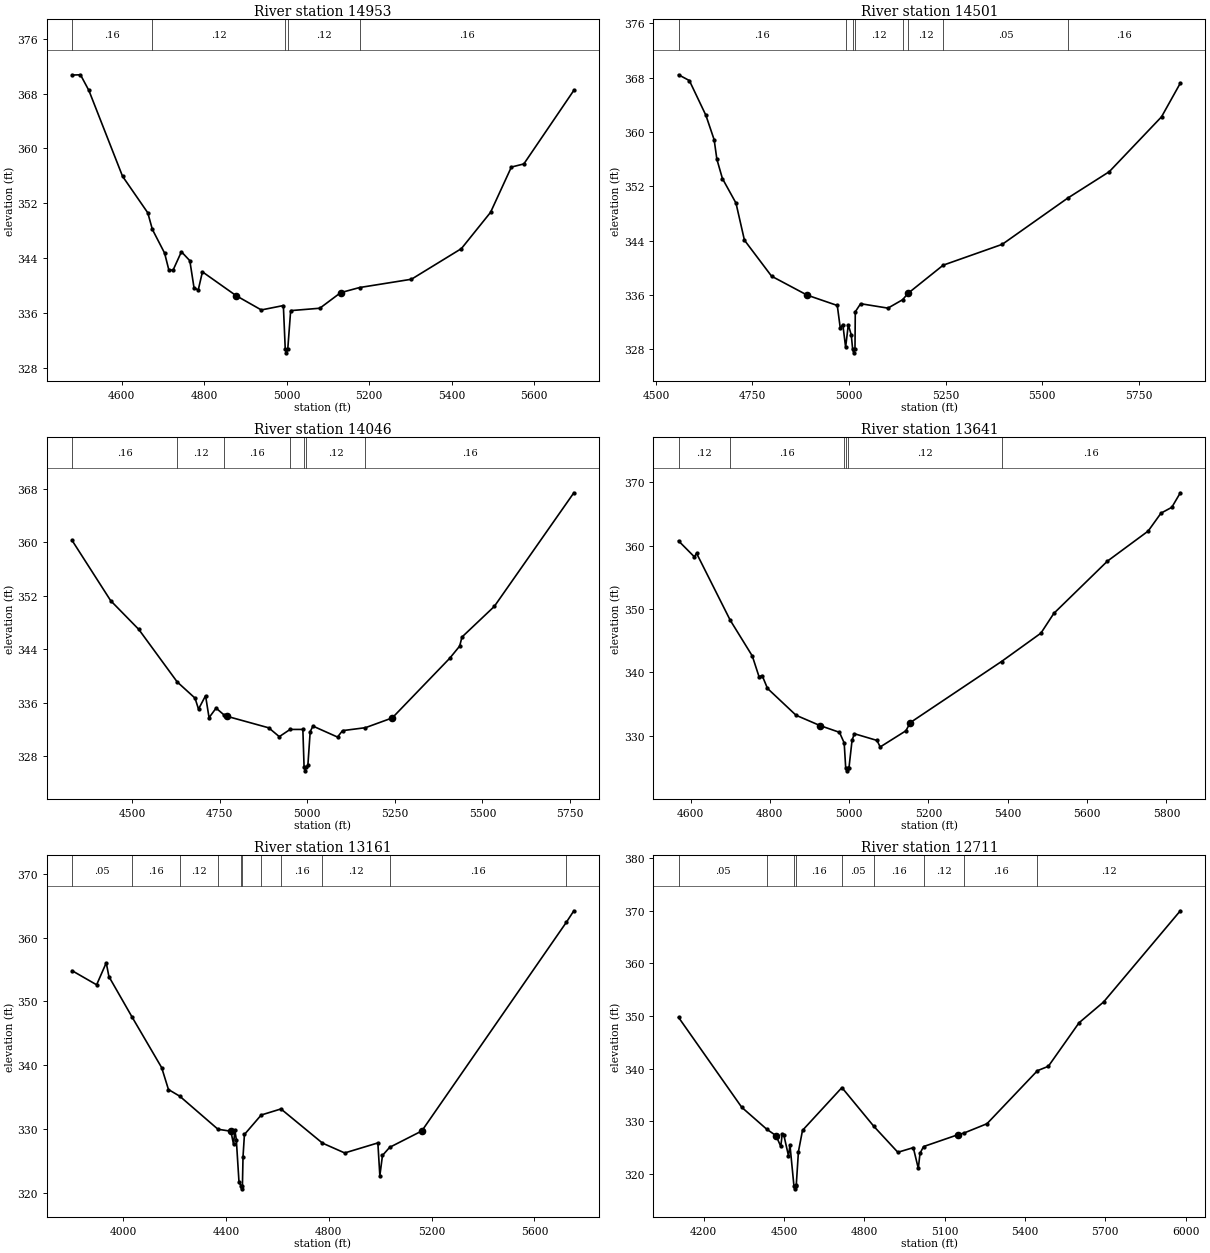
Type RM Length L Ch R = 1 ,14953   ,452,452,452
BEGIN DESCRIPTION:
UNT 116 IN UKCR 30.0
END DESCRIPTION:
XS GIS Cut Line= 3
      3650849.56     10564660.18      3651349.61     10564760.19
      3652049.65     10564860.19
#Sta/Elev= 30
  4479.3  370.71  4499.7  370.75  4520.1  368.46  4601.7  355.94  4662.9  350.61
  4674.1  348.18  4703.7  344.73  4713.9   342.3  4724.1  342.22  4744.5  344.92
  4764.9  343.62  4775.1  339.67  4785.3  339.33  4795.5  341.99  4877.1  338.52
  4938.3  336.43  4991.8  337.07  4996.4  330.67  4999.1  330.17  5002.4  330.67
  5009.5  336.33  5080.2  336.68  5130.7  338.95  5176.7   339.7  5302.4  340.91
  5423.6  345.38  5494.3  350.67  5544.8  357.28  5575.1  357.74  5696.4  368.48
#Mann= 5 ,-1 , 0
  4479.3     .16       0  4674.1     .12       0  4996.4     .07       0
  5002.4     .12       0  5176.7     .16       0
Bank Sta=4877.1,5130.7
XS Rating Curve= 0 ,0
Exp/Cntr=0.3,0.1

Type RM Length L Ch R = 1 ,14501   ,455,455,455
BEGIN DESCRIPTION:
UNT 116 IN UKCR 29.0
END DESCRIPTION:
XS GIS Cut Line= 3
      3650849.64     10564860.21      3651199.61     10565160.19
      3651999.61     10564910.19
#Sta/Elev= 30
  4558.6  368.42  4586.6  367.57  4629.4  362.46  4650.8  358.86  4657.9  355.98
  4672.2  353.15  4707.3  349.54  4729.2  344.08  4799.5  338.78  4891.7  335.99
  4969.6  334.47  4977.3  331.15  4983.9  331.67  4991.2  328.32  4998.1  331.62
  5005.8  330.14  5009.4     328  5012.2   327.5  5015.4     328  5016.2  333.54
    5030  334.73  5100.7  334.08  5138.8  335.32  5152.6  336.25  5243.7   340.4
  5396.7  343.47  5565.9  350.26  5673.8  354.16    5809  362.23  5857.7  367.19
#Mann= 8 ,-1 , 0
  4558.6     .16       0  4991.2     .12       0  5009.4     .07       0
  5015.4     .12       0  5138.8     .16       0  5152.6     .12       0
  5243.7     .05       0  5565.9     .16       0
Bank Sta=4891.7,5152.6
XS Rating Curve= 0 ,0
Exp/Cntr=0.3,0.1

Type RM Length L Ch R = 1 ,14046   ,405,405,405
BEGIN DESCRIPTION:
UNT 116 IN UKCR 28.0
END DESCRIPTION:
XS GIS Cut Line= 3
      3650649.56     10565460.18      3651299.61     10565510.19
      3651899.62     10566010.19
#Sta/Elev= 30
  4328.2  360.27  4438.6  351.25  4518.8  346.96  4628.3  339.12  4679.3  336.69
  4689.3  335.05  4709.4  337.05  4719.4  333.77  4739.5   335.2  4762.1  334.18
  4769.5  333.99  4889.9  332.25    4920  330.93  4950.8  332.01  4987.3  332.01
  4990.8  326.32  4993.6  325.82  4996.8  326.32  5001.6  326.64  5008.2  331.67
    5016  332.51  5086.3  330.87  5100.6  331.83  5165.9  332.27  5242.5  333.73
  5406.5  342.64  5435.1  344.47  5441.6  345.82    5534   350.4  5761.2  367.39
#Mann= 7 ,-1 , 0
  4328.2     .16       0  4628.3     .12       0  4762.1     .16       0
  4950.8     .12       0  4990.8     .07       0  4996.8     .12       0
  5165.9     .16       0
Bank Sta=4769.5,5242.5
XS Rating Curve= 0 ,0
Exp/Cntr=0.3,0.1

Type RM Length L Ch R = 1 ,13641   ,480,480,480
BEGIN DESCRIPTION:
UNT 116 IN UKCR 27.0
END DESCRIPTION:
XS GIS Cut Line= 3
      3650649.64      10565660.2      3651049.61     10565810.19
      3651849.59     10566060.18
#Sta/Elev= 30
  4569.7  360.74  4609.7  358.22  4615.1  358.79    4700  348.24  4755.7   342.6
  4772.6  339.35  4780.6  339.51    4794  337.49    4866  333.26  4926.6  331.63
  4975.5  330.57  4987.4   328.9  4991.2     325    4994   324.5  4997.2     325
  4999.5     325  5007.3  329.33  5013.1  330.35  5070.2  329.29  5078.1  328.26
    5143  330.81    5154   332.1  5384.1  341.73  5483.5   346.2    5516  349.31
  5651.2  357.55  5753.8  362.28  5786.3  365.11  5813.5  366.03    5835  368.32
#Mann= 6 ,-1 , 0
  4569.7     .12       0    4700     .16       0  4987.4     .12       0
  4991.2     .07       0  4997.2     .12       0  5384.1     .16       0
Bank Sta=4926.6,5154
XS Rating Curve= 0 ,0
Exp/Cntr=0.3,0.1

Type RM Length L Ch R = 1 ,13161   ,450,450,450
BEGIN DESCRIPTION:
UNT 116 IN UKCR 26.0
END DESCRIPTION:
XS GIS Cut Line= 3
      3649873.56     10566635.21      3650999.61     10566260.19
       3651749.6     10566110.19
#Sta/Elev= 30
  3801.6  354.82  3897.1  352.61  3934.5  356.05    3945  353.89  4035.3  347.54
  4150.2  339.63  4176.5  336.21  4220.3  335.17  4369.1  329.99  4419.3  329.68
  4429.6  327.64  4434.9  329.82  4440.4  328.38  4450.9   321.7  4458.2  321.16
    4461  320.66  4464.2  321.16  4466.5  325.68    4472  329.17  4537.2  332.22
  4614.1  333.17  4775.5  327.82    4862  326.28    4991  327.85  4998.7  322.71
  5008.9  325.89  5036.9  327.16  5161.8  329.72  5724.4  362.42  5753.3   364.2
#Mann= 11 ,-1 , 0
  3801.6     .05       0  4035.3     .16       0  4220.3     .12       0
  4369.1     .16       0  4458.2     .07       0  4464.2     .16       0
  4537.2     .05       0  4614.1     .16       0  4775.5     .12       0
  5036.9     .16       0  5724.4     .12       0
Bank Sta=4419.3,5161.8
XS Rating Curve= 0 ,0
Exp/Cntr=0.3,0.1

Type RM Length L Ch R = 1 ,12711   ,481,481,481
BEGIN DESCRIPTION:
UNT 116 IN UKCR 25.0
END DESCRIPTION:
XS GIS Cut Line= 3
      3650249.58      10567060.2      3651049.61     10566710.19
      3651849.57     10566110.21
#Sta/Elev= 30
  4106.6  349.73  4342.5  332.66  4435.6  328.51  4470.3  327.28  4488.3  325.23
  4493.7  327.59  4499.6   327.4  4517.1  323.44  4522.6  325.47  4537.5  317.68
  4540.3  317.18  4543.5  317.68    4546  317.82  4554.2  324.25  4569.4  328.28
  4716.5   336.4  4835.8  329.04  4925.3  324.12    4983     325  5001.7  321.05
    5008  323.91  5021.1   325.2  5151.7  327.49  5171.6  327.76    5258  329.54
  5446.4  339.61  5487.1  340.44  5601.7   348.7  5693.4  352.65  5979.8  369.96
#Mann= 9 ,-1 , 0
  4106.6     .05       0  4435.6     .16       0  4537.5     .07       0
  4543.5     .16       0  4716.5     .05       0  4835.8     .16       0
  5021.1     .12       0  5171.6     .16       0  5446.4     .12       0
Bank Sta=4470.3,5151.7
XS Rating Curve= 0 ,0
Exp/Cntr=0.3,0.1

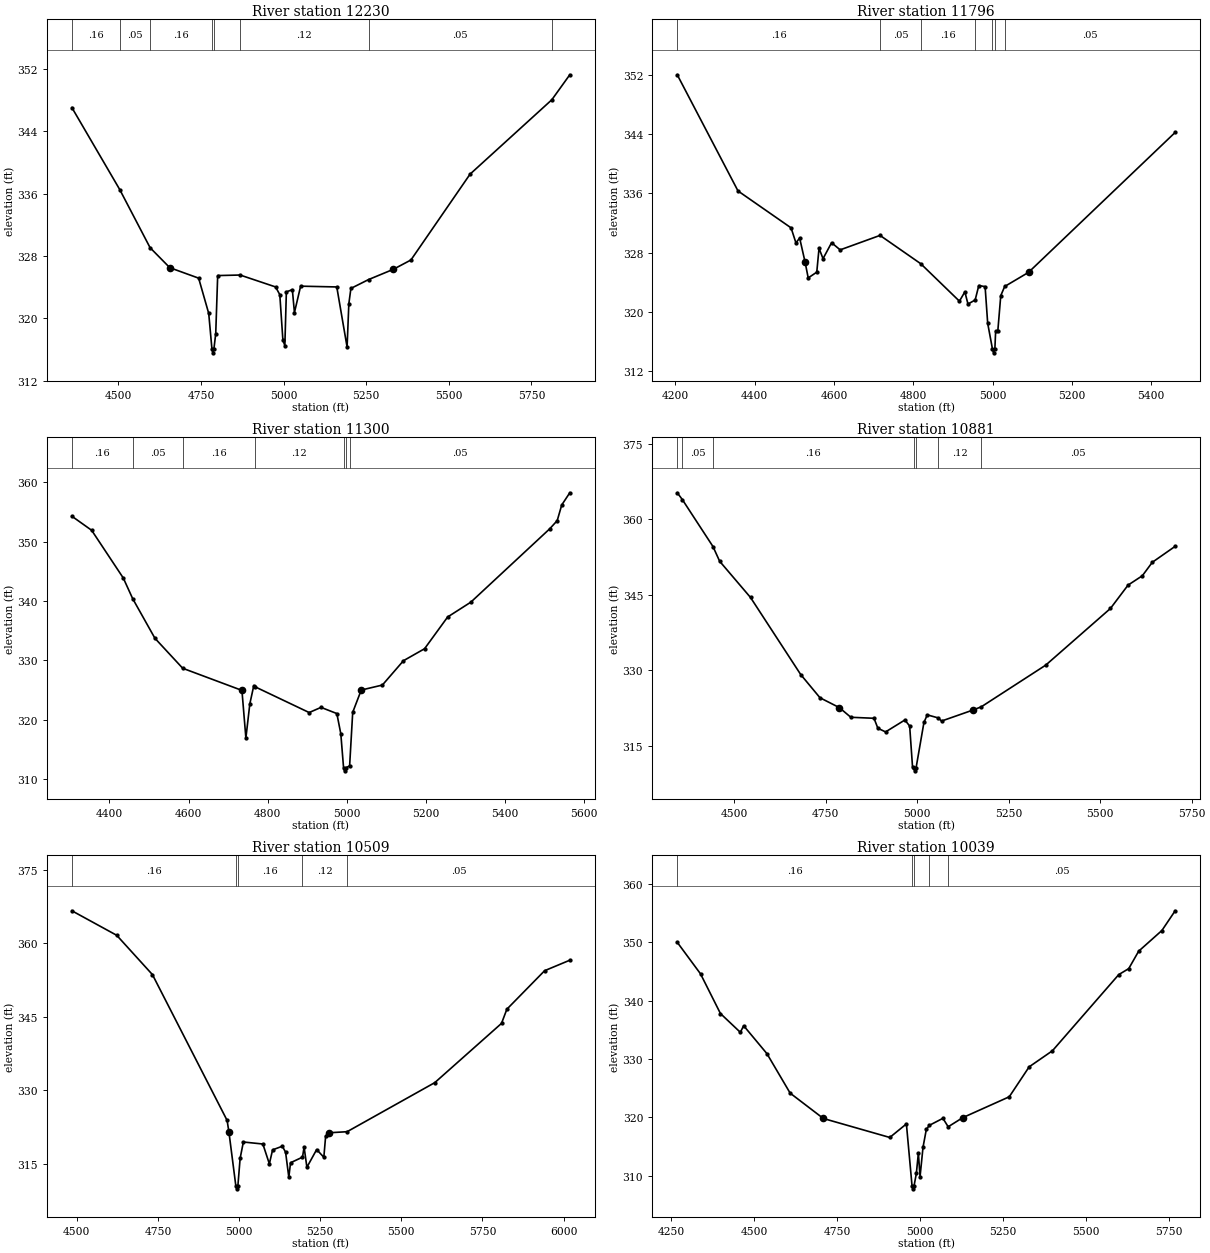
Type RM Length L Ch R = 1 ,12230   ,434,434,434
BEGIN DESCRIPTION:
UNT 116 IN UKCR 24.0
END DESCRIPTION:
XS GIS Cut Line= 3
      3650549.63     10567510.18      3651099.61     10567160.19
      3651899.61     10567460.19
#Sta/Elev= 30
  4359.7  347.06  4504.4  336.54  4596.3  329.07    4656   326.5  4743.2  325.16
  4773.7  320.63  4783.4  316.07  4786.1  315.57  4789.4  316.07  4794.9  318.04
  4800.8  325.49  4868.6  325.56    4976  324.03  4988.7  323.04  4998.1   317.2
    5004   316.5  5008.6   323.4  5026.7  323.68    5033  320.74  5051.7  324.13
  5161.1  324.03  5192.3  316.31  5197.6  321.88  5203.8  323.84  5257.4  324.98
    5332  326.29  5385.4  327.49  5564.3  338.51  5811.6  348.06    5866  351.27
#Mann= 8 ,-1 , 0
  4359.7     .16       0  4504.4     .05       0  4596.3     .16       0
  4783.4     .07       0  4789.4     .16       0  4868.6     .12       0
  5257.4     .05       0  5811.6     .16       0
Bank Sta=4656,5332
XS Rating Curve= 0 ,0
Exp/Cntr=0.3,0.1

Type RM Length L Ch R = 1 ,11796   ,496,496,496
BEGIN DESCRIPTION:
UNT 116 IN UKCR 23.0
END DESCRIPTION:
XS GIS Cut Line= 3
      3650599.63     10567910.18      3651299.61     10567510.19
      3651749.61     10567510.19
#Sta/Elev= 30
  4204.6  352.08  4357.9  336.34  4491.8  331.34    4504  329.31  4513.4  329.96
  4527.1  326.71    4535  324.56  4556.6  325.34  4562.3  328.57  4572.4  327.17
    4594  329.33  4615.6  328.36  4716.2  330.32    4819  326.48  4916.5  321.41
  4930.2  322.67  4938.1  321.02  4956.2  321.57  4965.4  323.53  4981.3  323.38
  4987.8  318.42  4999.9  314.91  5002.6  314.41  5005.9  314.91  5007.9  317.33
  5013.3  317.33  5020.8  322.16  5030.7   323.4  5090.8  325.31  5460.8  344.27
#Mann= 7 ,-1 , 0
  4204.6     .16       0  4716.2     .05       0    4819     .16       0
  4956.2     .12       0  4999.9     .07       0  5005.9     .12       0
  5030.7     .05       0
Bank Sta=4527.1,5090.8
XS Rating Curve= 0 ,0
Exp/Cntr=0.3,0.1

Type RM Length L Ch R = 1 ,11300   ,419,419,419
BEGIN DESCRIPTION:
UNT 116 IN UKCR 22.0
END DESCRIPTION:
XS GIS Cut Line= 3
      3650599.66     10567960.19      3651299.61     10567960.19
      3651849.64     10568060.19
#Sta/Elev= 30
  4304.9   354.3  4354.9  351.93  4434.9  343.89  4458.6  340.42  4514.9  333.74
  4585.1  328.69  4734.9  324.96  4744.9  316.94  4754.9  322.71  4764.9  325.77
    4768  325.57  4904.9  321.23  4934.9   322.1  4974.9  321.06  4984.9  317.66
  4991.9  311.91  4994.6  311.41  4997.9  311.91  5007.2  312.26    5015  321.27
  5036.6  325.02    5090  325.86  5143.3  329.96  5196.7  331.98  5255.1  337.33
  5313.6  339.82    5513  352.17  5532.1  353.56  5543.5  356.19  5563.9  358.25
#Mann= 7 ,-1 , 0
  4304.9     .16       0  4458.6     .05       0  4585.1     .16       0
    4768     .12       0  4991.9     .07       0  4997.9     .12       0
  5007.2     .05       0
Bank Sta=4734.9,5036.6
XS Rating Curve= 0 ,0
Exp/Cntr=0.3,0.1

Type RM Length L Ch R = 1 ,10881   ,372,372,372
BEGIN DESCRIPTION:
UNT 116 IN UKCR 21.0
END DESCRIPTION:
XS GIS Cut Line= 3
      3650499.64     10568510.18      3651099.61     10568310.19
      3651799.58      10568110.2
#Sta/Elev= 30
  4344.6  365.28  4358.4  363.94  4442.2  354.59  4460.5  351.66  4544.8  344.46
  4681.9  329.14  4734.6  324.52  4787.3  322.57  4818.9  320.64  4882.2  320.44
  4892.7  318.46  4913.8  317.73  4966.5   320.1  4979.6   318.9  4987.4   310.8
  4990.9  310.49  4993.7  309.99  4996.9  310.49  5018.6  319.61  5027.7  321.12
  5057.9  320.51  5066.7  319.89  5153.8  322.11  5175.5  322.73  5351.4  331.01
  5528.2  342.28  5576.3  346.92  5615.3  348.78  5642.6  351.46    5705  354.63
#Mann= 7 ,-1 , 0
  4344.6     .16       0  4358.4     .05       0  4442.2     .16       0
  4990.9     .07       0  4996.9     .16       0  5057.9     .12       0
  5175.5     .05       0
Bank Sta=4787.3,5153.8
XS Rating Curve= 0 ,0
Exp/Cntr=0.3,0.1

Type RM Length L Ch R = 1 ,10509   ,470,470,470
BEGIN DESCRIPTION:
UNT 116 IN UKCR 20.0
END DESCRIPTION:
XS GIS Cut Line= 3
      3650451.54     10568585.22       3651125.1       10568613.
        3651889.     10568217.16
#Sta/Elev= 30
  4484.7  366.62  4622.9  361.62    4733   353.6  4963.2  323.86  4968.8  321.45
  4990.2  310.42    4993  309.92  4996.2  310.42  5003.2  316.13  5013.2  319.47
  5073.3  319.06  5093.3  315.02  5103.3  317.87  5133.3  318.61  5143.3   317.4
  5153.3  312.28  5158.6  315.24  5195.4  316.38  5200.4  318.42    5209  314.32
  5239.1  317.93  5261.2  316.36  5266.8  320.68  5276.5  321.35  5332.9  321.57
  5603.2  331.58  5808.8  343.66  5825.3  346.55  5941.6   354.4  6019.2  356.54
#Mann= 5 ,-1 , 0
  4484.7     .16       0  4990.2     .07       0  4996.2     .16       0
  5195.4     .12       0  5332.9     .05       0
Bank Sta=4968.8,5276.5
XS Rating Curve= 0 ,0
Exp/Cntr=0.3,0.1

Type RM Length L Ch R = 1 ,10039   ,372,372,372
BEGIN DESCRIPTION:
UNT 116 IN UKCR 19.0
END DESCRIPTION:
XS GIS Cut Line= 3
       3650449.6     10568860.19      3651229.27     10568897.72
      3651949.59     10568910.19
#Sta/Elev= 30
  4268.7  349.97  4338.8  344.57  4398.9  337.77  4458.9  334.55  4468.9  335.68
    4539   330.9  4609.1  324.13  4709.2  319.79  4909.4  316.54  4959.5  318.86
  4976.5  308.24  4979.3  307.74  4982.5  308.24  4989.5  310.37  4995.6  313.88
  5000.6  309.79  5009.6  314.87  5019.6  317.93  5029.1  318.63  5069.6  319.82
  5085.4  318.37  5129.6  319.94  5269.6  323.51  5329.6  328.64  5399.7  331.39
  5599.7  344.44  5629.7  345.46  5659.7  348.45  5729.7  351.99  5769.7  355.37
#Mann= 5 ,-1 , 0
  4268.7     .16       0  4976.5     .07       0  4982.5     .16       0
  5029.1     .12       0  5085.4     .05       0
Bank Sta=4709.2,5129.6
XS Rating Curve= 0 ,0
Exp/Cntr=0.3,0.1

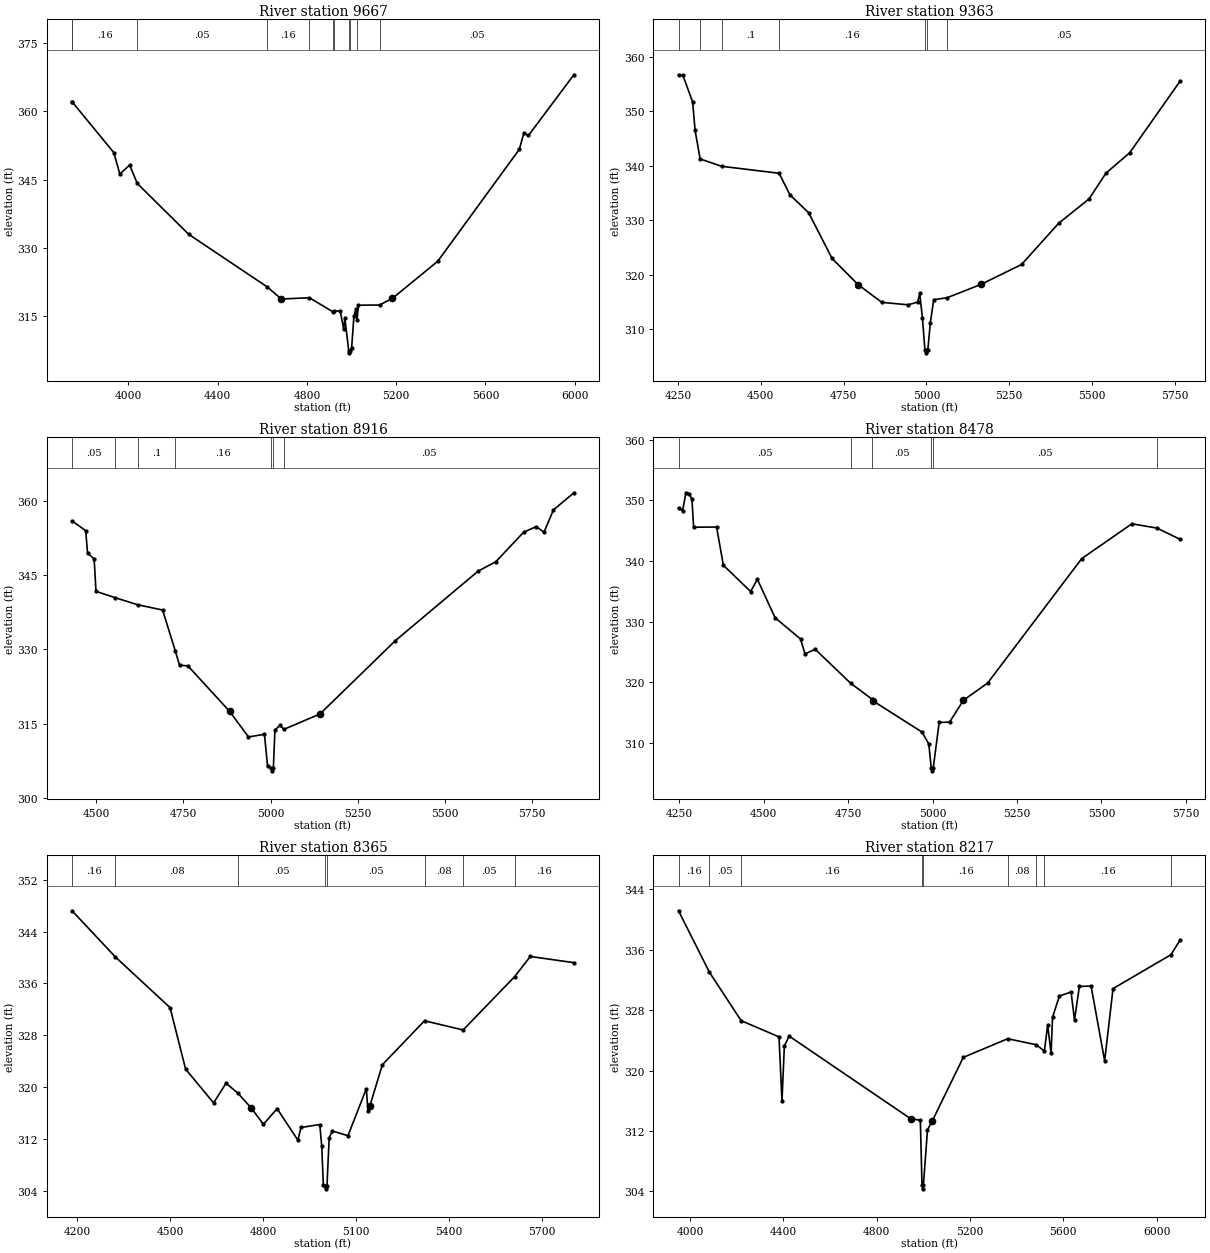
Type RM Length L Ch R = 1 ,9667    ,304,304,304
BEGIN DESCRIPTION:
Mapping XS 216b282f
END DESCRIPTION:
XS GIS Cut Line= 2
      3649995.34     10569431.81      3652210.56     10569049.88
#Sta/Elev= 30
    3748  362.07  3748.6  362.07    3935  350.94    3962  346.23    4006  348.21
    4040  344.17  4269.9  333.02  4620.2  321.51  4685.9  318.79    4811  319.07
  4916.3  315.99  4923.3  316.22  4949.7   316.1  4964.5  312.18    4970  314.56
  4987.3  307.47  4990.1  306.97  4993.3  307.47  5000.5  308.08  5010.6  315.02
  5019.3  316.52  5024.3  314.12  5030.9  317.43  5125.3  317.47  5183.1  318.93
  5386.1  327.08  5751.4  351.64  5771.7  355.19  5792.6   354.7  5995.9  368.03
#Mann= 11 ,-1 , 0
    3748     .05       0  3748.6     .16       0    4040     .05       0
  4620.2     .16       0    4811     .12       0  4916.3     .16       0
  4923.3     .12       0  4987.3     .07       0  4993.3     .12       0
  5024.3     .16       0  5125.3     .05       0
Bank Sta=4685.9,5183.1
XS Rating Curve= 0 ,0
Exp/Cntr=0.3,0.1

Type RM Length L Ch R = 1 ,9363    ,447,447,447
BEGIN DESCRIPTION:
UNT 116 IN UKCR 18.0
END DESCRIPTION:
XS GIS Cut Line= 3
      3650849.64     10570060.15      3651299.61     10569460.19
      3652049.61     10569310.19
#Sta/Elev= 30
  4251.6   356.7  4265.1  356.57  4294.3  351.67  4301.6  346.48  4316.8  341.25
  4381.4   339.9  4555.3  338.62    4588  334.65  4644.3  331.38  4715.1  322.98
  4794.3  318.14  4865.1  314.92  4944.3  314.47  4973.4  314.95  4979.7  316.55
    4988  311.99  4995.4  306.15  4998.2  305.65  5001.4  306.15  5004.1  306.15
  5011.7  311.15  5021.9   315.4    5063  315.78  5164.7  318.22  5287.1  321.87
  5399.3  329.45  5491.1  333.92    5542  338.65  5613.4  342.37  5766.4  355.59
#Mann= 7 ,-1 , 0
  4251.6     .05       0  4316.8     .08       0  4381.4      .1       0
  4555.3     .16       0  4995.4     .07       0  5001.4     .16       0
    5063     .05       0
Bank Sta=4794.3,5164.7
XS Rating Curve= 0 ,0
Exp/Cntr=0.3,0.1

Type RM Length L Ch R = 1 ,8916    ,438,438,438
BEGIN DESCRIPTION:
UNT 116 IN UKCR 17.0
END DESCRIPTION:
XS GIS Cut Line= 3
       3650949.6     10570060.19      3651449.61     10569860.19
       3652199.6      10569360.2
#Sta/Elev= 30
  4430.3   355.9  4469.4  353.93  4474.7  349.43  4493.6  348.23    4499   341.7
  4552.6  340.46  4618.1  339.01  4690.1  337.94  4726.3  329.75  4738.6  326.84
  4762.8  326.68  4882.7  317.49  4936.5  312.36  4982.3  312.89  4991.4  306.43
  5001.9  306.03  5004.6  305.53  5007.9  306.03  5012.4  313.73  5027.4  314.76
  5037.5  313.87  5141.6  316.99  5357.9  331.76  5595.3  345.77  5646.4  347.68
    5726  353.62    5762  354.75  5784.6  353.64  5811.6  358.11  5870.2  361.57
#Mann= 7 ,-1 , 0
  4430.3     .05       0  4552.6     .15       0  4618.1      .1       0
  4726.3     .16       0  5001.9     .07       0  5007.9     .16       0
  5037.5     .05       0
Bank Sta=4882.7,5141.6
XS Rating Curve= 0 ,0
Exp/Cntr=0.3,0.1

Type RM Length L Ch R = 1 ,8478    ,113,113,113
BEGIN DESCRIPTION:
UNT 116 IN UKCR 16.0
END DESCRIPTION:
XS GIS Cut Line= 4
      3650997.82     10570149.91      3651516.08     10570215.02
      3652109.83      10570079.6      3652364.85     10569832.39
#Sta/Elev= 30
  4247.3  348.74  4259.2  348.27  4269.3  351.23  4279.3  351.11    4287  350.13
  4292.1  345.56    4360  345.59  4380.1   339.3  4460.8  334.97  4480.9  336.98
  4533.3  330.65  4608.7  327.15    4622   324.7  4652.2  325.45  4756.9  319.88
  4820.5  317.24  4824.5  316.92  4968.1  311.84  4988.6  309.87  4995.9  305.94
  4998.7  305.44  5001.9  305.94  5019.4  313.41  5050.2  313.46  5091.2  317.06
    5163   319.9  5441.7  340.39  5590.2  346.12  5664.4  345.42  5733.8  343.55
#Mann= 6 ,-1 , 0
  4247.3     .05       0  4756.9     .16       0  4820.5     .05       0
  4995.9     .04       0  5001.9     .05       0  5664.4     .16       0
Bank Sta=4824.5,5091.2
XS Rating Curve= 0 ,0
Exp/Cntr=0.3,0.1

Type RM Length L Ch R = 1 ,8365    ,148,148,148
BEGIN DESCRIPTION:
Mapping XS cce55ab3
END DESCRIPTION:
XS GIS Cut Line= 4
      3650974.44     10570258.21      3651550.85      10570296.4
      3652155.02     10570213.07      3652431.96     10569884.21
#Sta/Elev= 30
  4184.2  347.23  4323.3  340.12  4500.1  332.26  4550.2  322.76  4640.4  317.54
  4680.5  320.58  4718.7  319.05  4761.9  316.75    4801  314.23  4845.2  316.65
    4912  311.78  4922.2  313.74  4982.7   314.2    4989  310.83  4994.1  304.91
  4999.9  304.76  5002.6  304.26  5005.9  304.76    5013  312.15  5023.1   313.2
  5073.6  312.47  5132.9  319.74  5137.9  316.25  5144.2   317.1  5184.6  323.45
  5320.3  330.23  5444.8  328.81  5611.2  337.07  5661.3  340.17  5801.7  339.21
#Mann= 8 ,-1 , 0
  4184.2     .16       0  4323.3     .08       0  4718.7     .05       0
  4999.9     .04       0  5005.9     .05       0  5320.3     .08       0
  5444.8     .05       0  5611.2     .16       0
Bank Sta=4761.9,5144.2
XS Rating Curve= 0 ,0
Exp/Cntr=0.3,0.1

Type RM Length L Ch R = 1 ,8217    ,223,223,223
BEGIN DESCRIPTION:
Mapping XS da996da6
END DESCRIPTION:
XS GIS Cut Line= 3
      3650845.95     10570595.03      3652106.41     10570327.65
      3652800.89     10569817.21
#Sta/Elev= 30
    3951  341.15    4083  333.03  4219.4   326.6  4381.5  324.46  4394.3  315.99
  4404.5  323.25    4425  324.56  4946.3  313.61  4987.2  313.43  4994.4  304.84
  4997.2  304.34  5000.4  304.84  5017.9  312.16  5038.3  313.32  5171.2  321.74
  5361.5  324.21  5483.8  323.42  5518.8  322.57  5532.9  326.01  5547.6  322.27
  5553.8  327.06  5583.1  329.86  5633.2   330.4  5647.9  326.68  5668.7  331.13
  5718.9  331.19  5777.1  321.29    5813  330.85  6061.2  335.33  6101.4  337.33
#Mann= 9 ,-1 , 0
    3951     .16       0    4083     .05       0  4219.4     .16       0
  4994.4     .07       0  5000.4     .16       0  5361.5     .08       0
  5483.8     .05       0  5518.8     .16       0  6061.2     .05       0
Bank Sta=4946.3,5038.3
XS Rating Curve= 0 ,0
Exp/Cntr=0.3,0.1

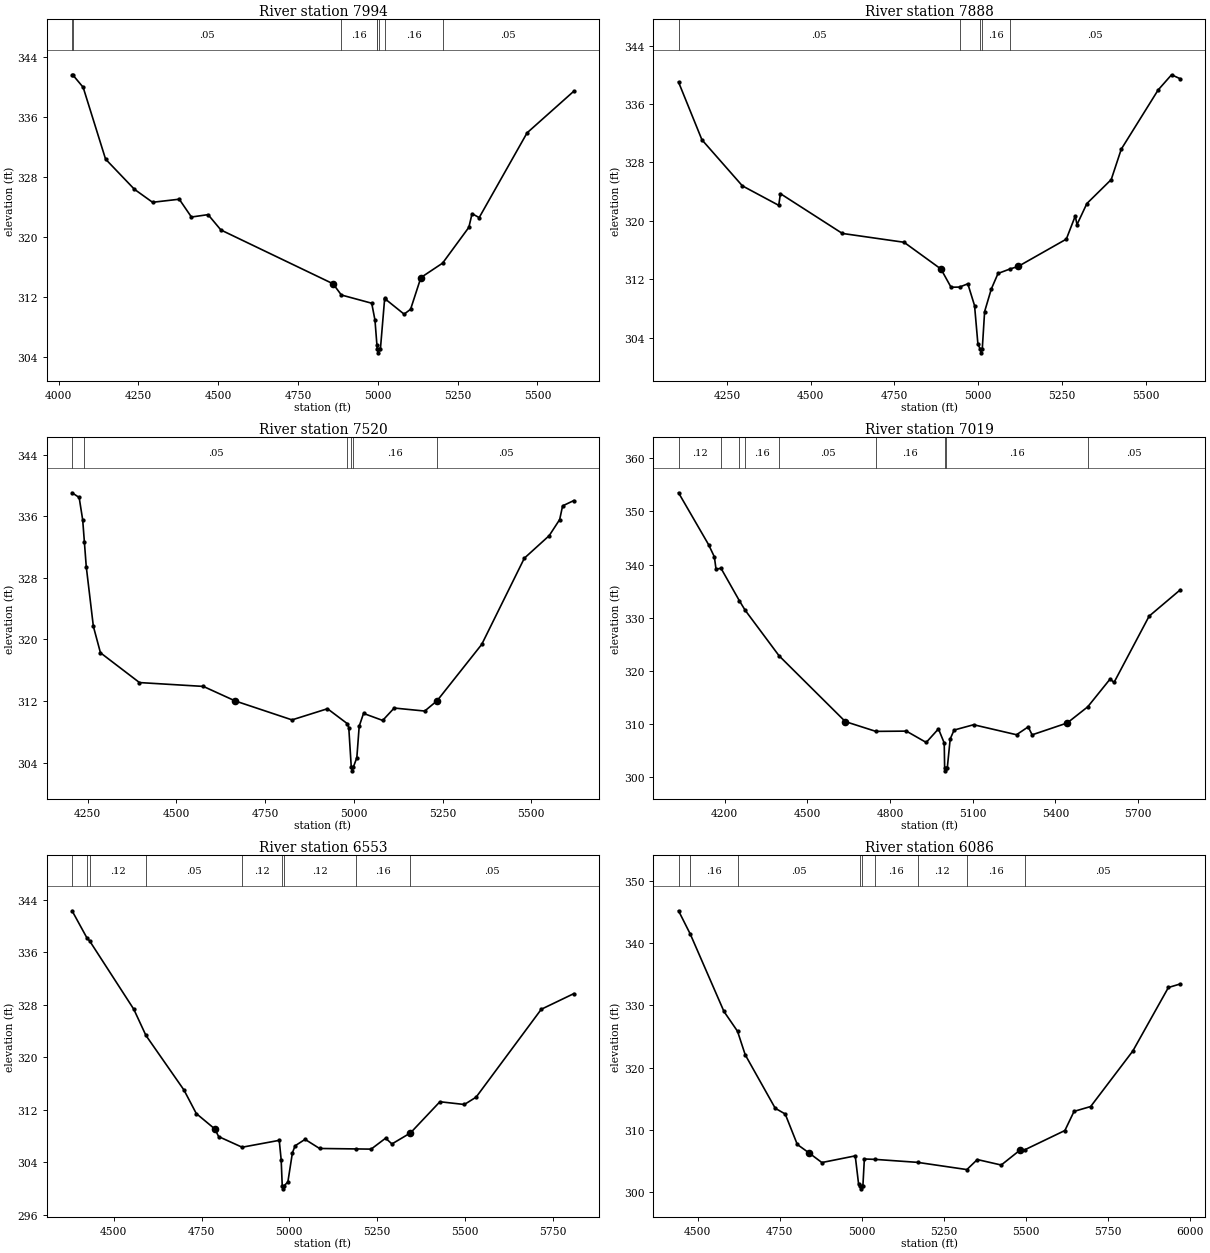
Type RM Length L Ch R = 1 ,7994    ,106,106,106
BEGIN DESCRIPTION:
Mapping XS 85a4ac86
END DESCRIPTION:
XS GIS Cut Line= 3
      3650905.07     10570615.84      3651755.71      10570546.4
      3652464.07     10570664.46
#Sta/Elev= 30
  4042.4  341.66  4044.3  341.66  4077.1  339.99  4147.3  330.39  4237.6  326.36
  4294.5  324.62  4378.1  325.03  4416.2  322.65  4468.4  322.97  4508.5  320.92
  4859.7  313.73  4885.8  312.23  4980.9  311.13  4991.1  308.87  4997.1   305.6
  4998.2     305    5001   304.5  5004.2     305  5008.2  305.05  5021.5   311.8
  5023.8  311.68  5082.3  309.67  5102.6  310.32  5134.9  314.56  5202.9  316.49
  5285.1  321.27  5295.2   323.1  5317.4  322.57  5467.5   333.9    5614  339.47
#Mann= 8 ,-1 , 0
  4042.4     .16       0  4044.3     .05       0  4885.8     .16       0
  4997.1     .05       0  4998.2     .03       0  5004.2     .05       0
  5023.8     .16       0  5202.9     .05       0
Bank Sta=4859.7,5134.9
XS Rating Curve= 0 ,0
Exp/Cntr=0.3,0.1

Type RM Length L Ch R = 1 ,7888    ,368,368,368
BEGIN DESCRIPTION:
UNT 116 IN UKCR 15.0
END DESCRIPTION:
XS GIS Cut Line= 5
      3650930.15      10570707.2      3651516.08     10570644.71
      3651981.41      10570671.4      3652190.56     10570728.04
      3652415.83     10570728.04
#Sta/Elev= 30
  4105.8  339.01  4175.6   331.1  4296.3  324.79  4404.8  322.12  4409.8  323.72
  4594.6  318.27  4778.7  317.06  4888.9  313.39  4918.9   310.9  4944.3  310.92
    4969  311.37  4989.1  308.38  4999.1  303.12  5006.1  302.41  5008.8  301.91
  5012.1  302.41  5019.1  307.56  5039.1  310.66  5059.2  312.79  5094.9   313.4
  5119.3  313.75  5262.9  317.49  5289.6  320.66  5294.8  319.48  5324.3  322.37
  5396.9  325.65  5426.9  329.82  5536.9  337.93  5576.9  340.01  5603.1  339.46
#Mann= 5 ,-1 , 0
  4105.8     .05       0  4944.3     .16       0  5006.1     .07       0
  5012.1     .16       0  5094.9     .05       0
Bank Sta=4888.9,5119.3
XS Rating Curve= 0 ,0
Exp/Cntr=0.3,0.1

Type RM Length L Ch R = 1 ,7520    ,501,501,501
BEGIN DESCRIPTION:
UNT 116 IN UKCR 14.0
END DESCRIPTION:
XS GIS Cut Line= 3
      3651049.58     10571010.19      3651849.61     10571010.19
      3652418.94     10570779.03
#Sta/Elev= 30
  4205.7  339.05  4225.7  338.44  4235.7  335.51  4240.4  332.66  4245.7  329.45
  4265.7   321.7  4285.7  318.26  4395.7  314.39  4575.7  313.89  4665.7     312
  4825.7  309.54  4925.7  310.99  4981.6  309.05  4985.7  308.54  4992.7  303.42
  4995.5  302.92  4998.7  303.42  5008.4  304.62  5015.1  308.72  5027.3  310.38
  5081.3  309.47  5113.7  311.08  5199.8  310.69  5234.7  312.03  5360.5  319.35
  5480.6  330.55  5550.7  333.48  5580.2  335.57  5588.5  337.35  5620.2  338.04
#Mann= 6 ,-1 , 0
  4205.7     .15       0  4240.4     .05       0  4981.6     .16       0
  4992.7     .07       0  4998.7     .16       0  5234.7     .05       0
Bank Sta=4665.7,5234.7
XS Rating Curve= 0 ,0
Exp/Cntr=0.3,0.1

Type RM Length L Ch R = 1 ,7019    ,466,466,466
BEGIN DESCRIPTION:
UNT 116 IN UKCR 13.0
END DESCRIPTION:
XS GIS Cut Line= 3
      3651049.63     10572010.17      3651849.61     10571460.19
      3652449.59      10570860.2
#Sta/Elev= 30
  4033.3  353.51  4142.2  343.76  4163.2  341.46  4169.2  339.15  4187.3  339.31
  4254.2  333.18  4274.6  331.44  4397.9  322.85  4638.1  310.48  4748.7  308.64
  4859.3  308.69  4931.3  306.56  4975.7  309.11  4996.6  306.45  4998.1  301.72
  5000.8  301.22  5004.1  301.72  5007.6  301.72  5018.2  307.21  5032.4  308.89
  5103.1  309.89  5258.7  308.01  5301.1  309.49  5315.2  307.99  5442.5  310.22
  5516.9  313.26  5598.1  318.49  5612.2  317.84  5739.5  330.31  5852.6  335.27
#Mann= 9 ,-1 , 0
  4033.3     .12       0  4187.3     .16       0  4254.2     .12       0
  4274.6     .16       0  4397.9     .05       0  4748.7     .16       0
  4998.1     .07       0  5004.1     .16       0  5516.9     .05       0
Bank Sta=4638.1,5442.5
XS Rating Curve= 0 ,0
Exp/Cntr=0.3,0.1

Type RM Length L Ch R = 1 ,6553    ,467,467,467
BEGIN DESCRIPTION:
UNT 116 IN UKCR 12.0
END DESCRIPTION:
XS GIS Cut Line= 3
      3651399.59      10572110.2      3651949.61     10571860.19
      3652749.62     10571660.19
#Sta/Elev= 30
  4381.3  342.35  4423.2  338.25  4431.2  337.76  4557.1  327.32  4591.6  323.33
  4699.9     315    4735  311.41  4787.7  309.06  4798.7  307.89  4865.5  306.27
  4971.2  307.32  4976.7  304.35  4979.7  300.42  4982.5  299.92  4985.7  300.42
  4995.8  300.97  5008.7  305.42  5016.4  306.49  5044.7  307.47    5086  306.08
  5190.8  306.01  5232.9  305.98  5274.1  307.65  5292.1  306.77  5344.8  308.45
  5428.7  313.21  5498.3  312.79  5531.8  313.91  5717.3  327.32  5810.1  329.71
#Mann= 9 ,-1 , 0
  4381.3     .12       0  4423.2     .16       0  4431.2     .12       0
  4591.6     .05       0  4865.5     .12       0  4979.7     .07       0
  4985.7     .12       0  5190.8     .16       0  5344.8     .05       0
Bank Sta=4787.7,5344.8
XS Rating Curve= 0 ,0
Exp/Cntr=0.3,0.1

Type RM Length L Ch R = 1 ,6086    ,118,118,118
BEGIN DESCRIPTION:
UNT 116 IN UKCR 11.0
END DESCRIPTION:
XS GIS Cut Line= 3
      3651399.61     10572160.19      3651949.61     10572260.19
      3652749.57     10571710.21
#Sta/Elev= 30
  4441.2  345.18    4477  341.44  4579.7  329.02    4621  325.85  4644.5  322.07
    4736  313.49  4766.4  312.57  4803.3  307.68  4837.6  306.38  4878.2  304.78
  4979.9  305.85  4990.1  301.34  4994.7  301.06  4997.4  300.56  5000.7  301.06
  5003.3  301.06  5007.7  305.35    5040  305.29  5169.8  304.81  5320.3  303.65
  5352.1  305.26    5425  304.38  5482.6  306.79  5496.6  306.82  5619.1  309.92
    5647  312.99  5697.7  313.77  5826.2  322.68  5934.6  332.87    5971  333.44
#Mann= 9 ,-1 , 0
  4441.2     .12       0    4477     .16       0    4621     .05       0
  4994.7     .03       0  5000.7     .05       0    5040     .16       0
  5169.8     .12       0  5320.3     .16       0  5496.6     .05       0
Bank Sta=4837.6,5482.6
XS Rating Curve= 0 ,0
Exp/Cntr=0.3,0.1