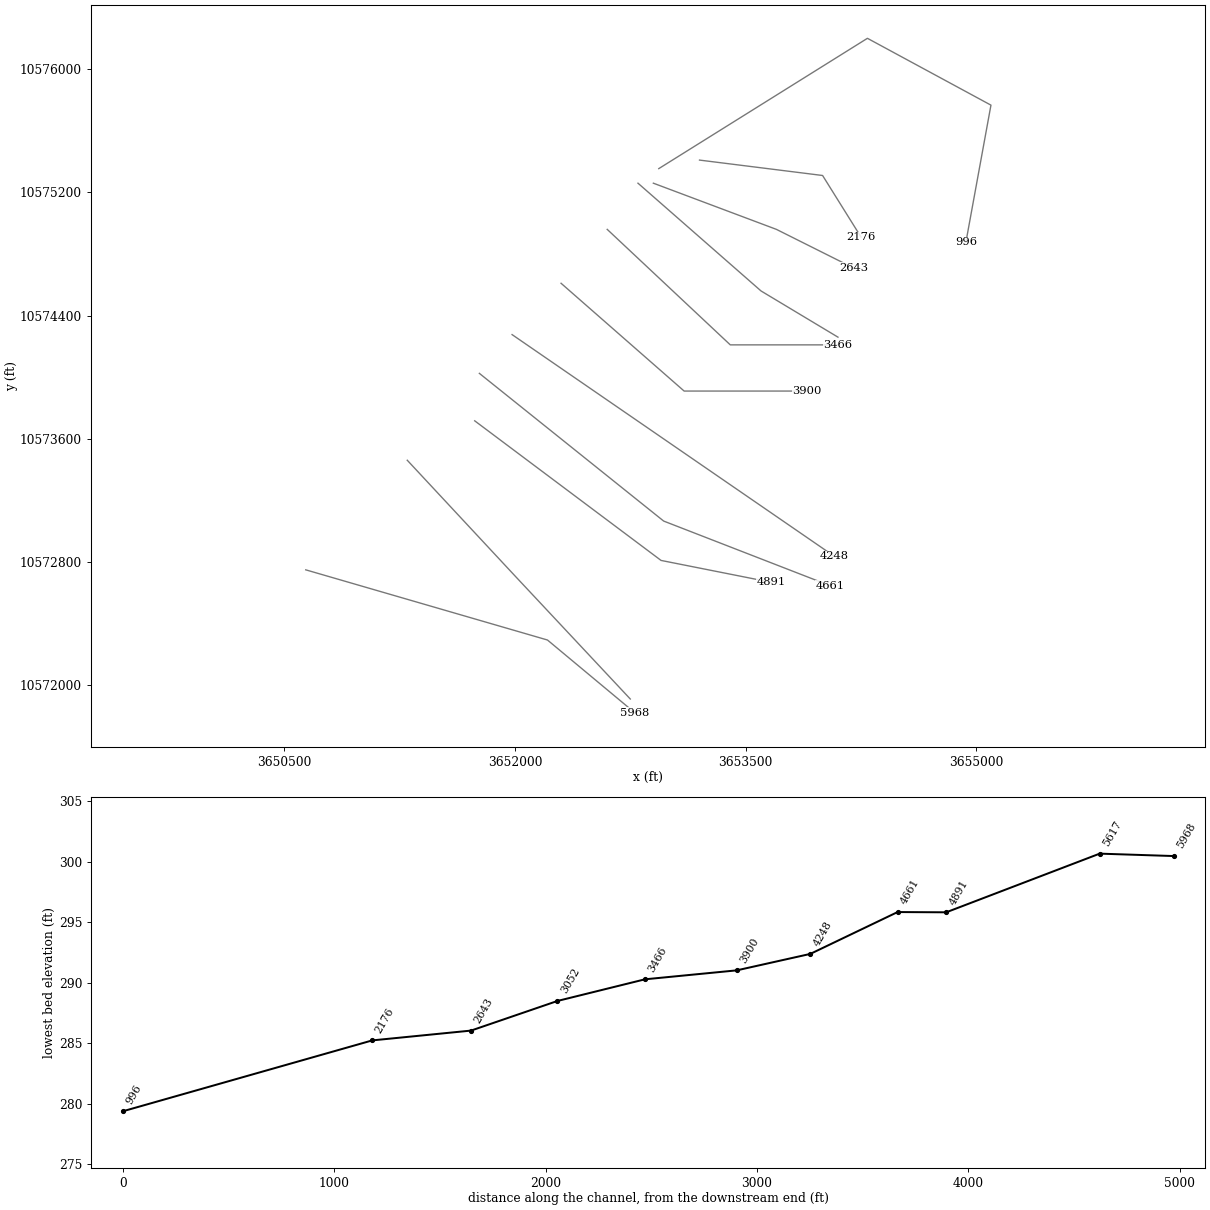
HEC-RAS study UNT 116 IN UKCR.prj: UNT 116 IN UKCR Base Level Engineering

--- UNT 116 IN UKCR.g01 (geometry) --- (continued)

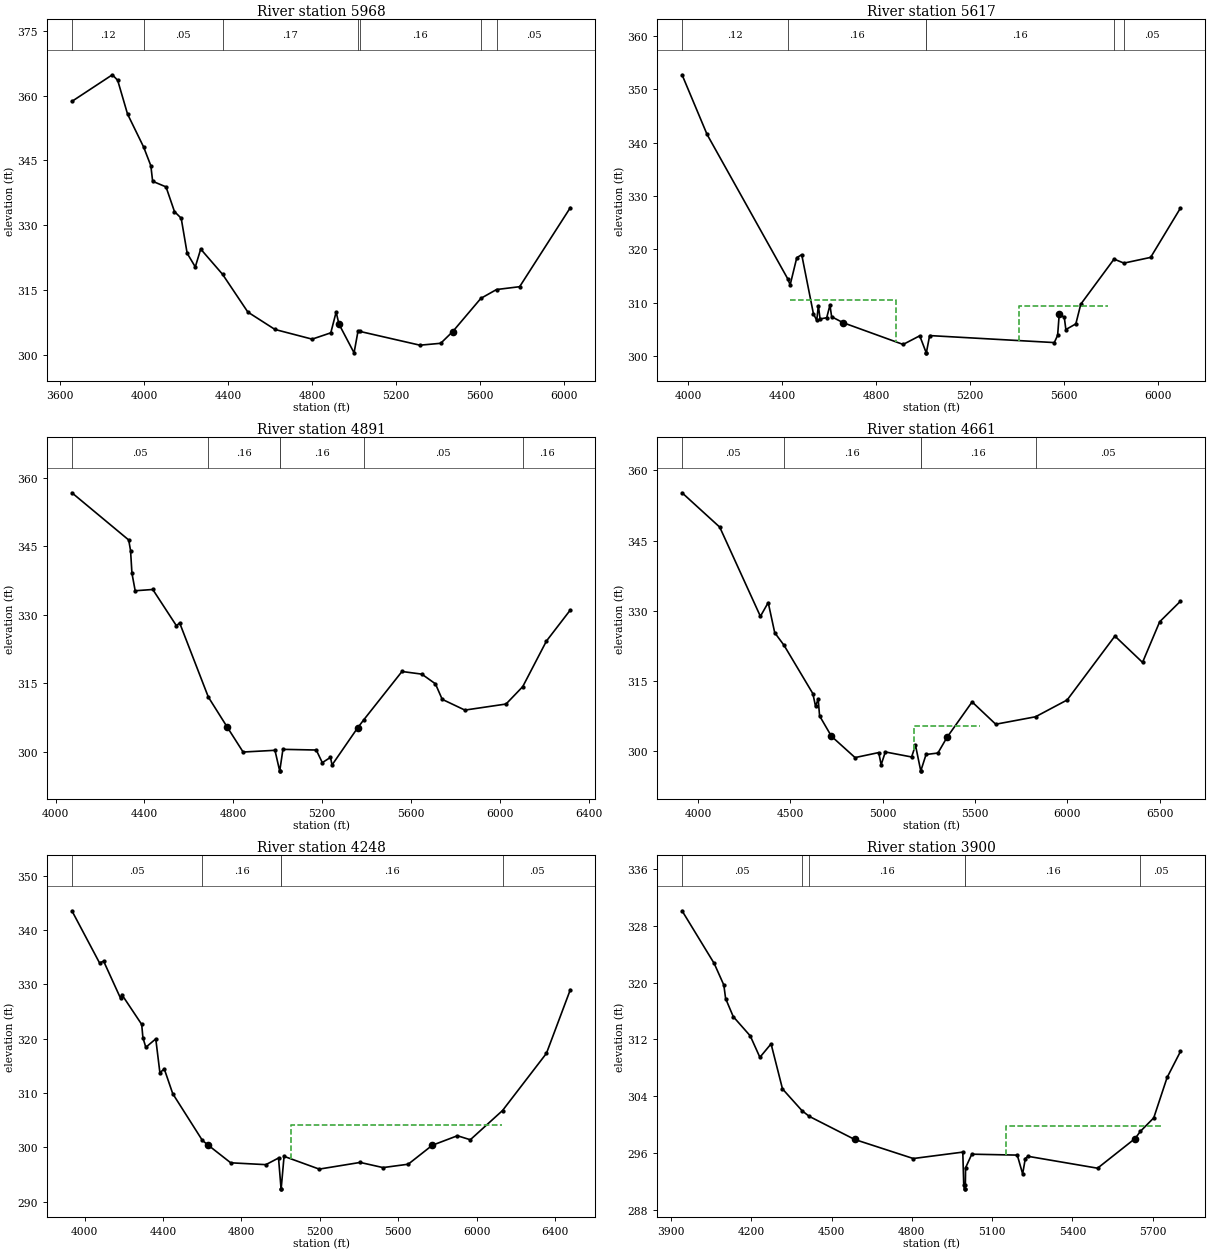
Type RM Length L Ch R = 1 ,5968    ,351,351,351
BEGIN DESCRIPTION:
Mapping XS a2881d37
END DESCRIPTION:
XS GIS Cut Line= 3
      3650640.03     10572749.07      3652211.25     10572293.33
       3652779.8     10571820.27
#Sta/Elev= 30
  3655.8  358.66  3848.6  364.82    3874  363.54  3920.9  355.74  3997.8  348.08
  4032.1  343.76  4040.6  340.17  4104.4  338.87  4144.7  333.15  4176.7  331.62
  4205.1  323.51  4243.9  320.34  4269.7  324.48  4373.8  318.64  4494.5  309.89
  4623.7  305.87  4800.7  303.63  4889.7  305.09  4915.2   309.9  4928.5  307.13
  5000.6  300.46  5019.4  305.48  5027.2  305.43  5314.7  302.23  5413.6  302.67
  5470.9  305.38    5605  313.07  5679.6  315.11  5789.8  315.77  6031.4  334.07
#Mann= 7 ,-1 , 0
  3655.8     .12       0  3997.8     .05       0  4373.8     .17       0
  5019.4     .05       0  5027.2     .16       0    5605     .16       0
  5679.6     .05       0
Bank Sta=4928.5,5470.9
XS Rating Curve= 0 ,0
Exp/Cntr=0.3,0.1

Type RM Length L Ch R = 1 ,5617    ,726,726,726
BEGIN DESCRIPTION:
UNT 116 IN UKCR 10.0
END DESCRIPTION:
XS GIS Cut Line= 3
      3651299.81     10573460.85      3651999.61     10572710.19
      3652749.58     10571910.22
#Sta/Elev= 30
  3972.7  352.69  4079.3  341.52  4422.3  314.55    4433  313.36  4461.3  318.47
  4482.3  319.03  4532.2  307.97  4546.3  306.73  4553.2   309.5  4560.5     307
  4588.8  307.23  4602.5   309.6  4609.8  307.41  4659.2  306.29  4914.2  302.23
    4985  303.85  5012.6  300.66  5013.1  300.66  5027.1  303.89    5558  302.58
  5572.2  303.93    5579  307.87  5600.5  307.34  5607.3  305.02  5649.8  306.08
  5670.9  309.77  5812.5   318.2  5854.6  317.45  5968.3  318.52  6095.5  327.76
#Mann= 6 ,-1 , 0
  3972.7     .12       0  4422.3     .16       0  5012.6     .07       0
  5013.1     .16       0  5812.5     .16       0  5854.6     .05       0
#XS Ineff= 2 ,-1
 4432.39 4882.39  310.51 5405.68  5785.8  309.46
Permanent Ineff=
       F       F
Bank Sta=4659.2,5579
XS Rating Curve= 0 ,0
Exp/Cntr=0.3,0.1

Type RM Length L Ch R = 1 ,4891    ,230,230,230
BEGIN DESCRIPTION:
UNT 116 IN UKCR 8.0
END DESCRIPTION:
XS GIS Cut Line= 3
      3651738.17     10573716.94      3652949.61     10572810.19
      3653665.07     10572668.24
#Sta/Elev= 30
  4073.7  356.74  4329.2   346.4  4337.6  344.09  4343.8  339.13  4358.4  335.27
  4437.6  335.55  4543.9  327.61  4558.5  328.22  4687.6  311.97  4773.1  305.35
    4844  299.93  4987.3  300.31  5008.4  295.81  5008.9  295.81  5023.2  300.52
  5173.2  300.37  5200.3  297.61  5237.2  298.76  5244.1  297.09  5358.7  305.19
    5387     307  5558.8  317.58  5648.1     317  5709.2  314.88  5739.8  311.48
  5841.8  309.12    6027  310.45  6102.1  314.26  6208.8  324.25  6316.3  331.06
#Mann= 6 ,-1 , 0
  4073.7     .05       0  4687.6     .16       0  5008.4     .07       0
  5008.9     .16       0    5387     .05       0  6102.1     .16       0
Bank Sta=4773.1,5358.7
XS Rating Curve= 0 ,0
Exp/Cntr=0.3,0.1

Type RM Length L Ch R = 1 ,4661    ,413,413,413
BEGIN DESCRIPTION:
UNT 116 IN UKCR 7.0
END DESCRIPTION:
XS GIS Cut Line= 3
      3651768.57     10574025.08      3652966.46      10573065.9
      3654051.18     10572645.03
#Sta/Elev= 30
  3914.3  355.19  4118.2  347.86  4338.4  328.81  4380.7  331.75  4415.9  325.32
  4466.5  322.62  4622.4  312.31  4636.8  309.62  4651.2  311.15  4658.7  307.57
  4722.7  303.22  4850.8  298.66  4978.9  299.73  4992.1  297.13  5014.5  299.86
    5157  298.79  5177.8  301.31  5206.3  295.83  5206.8  295.83  5235.1  299.32
  5299.2  299.63    5349  303.01  5484.4  310.54  5612.3  305.78  5827.7  307.37
  5998.9  310.96  6257.3   324.6  6406.9  318.98  6499.7  327.65  6612.4  332.05
#Mann= 5 ,-1 , 0
  3914.3     .05       0  4466.5     .16       0  5206.3     .07       0
  5206.8     .16       0  5827.7     .05       0
#XS Ineff= 1 ,-1
 5168.47 5526.42305.3352
Permanent Ineff=
       F
Bank Sta=4722.7,5349
XS Rating Curve= 0 ,0
Exp/Cntr=0.3,0.1

Type RM Length L Ch R = 1 ,4248    ,348,348,348
BEGIN DESCRIPTION:
Mapping XS 53f40cd6
END DESCRIPTION:
XS GIS Cut Line= 2
      3651981.19     10574276.86      3654076.11     10572836.87
#Sta/Elev= 30
  3935.2  343.53  4076.1  333.94  4097.1  334.25  4183.7   327.4  4189.7  328.12
  4291.2  322.62  4297.3  320.19  4312.2  318.41  4362.9  319.96  4383.9  313.76
  4406.5  314.41  4449.6  309.87  4600.7  301.28  4628.8  300.45  4745.2  297.16
  4924.5  296.82    4989  298.04    5002  292.37  5002.5  292.37  5017.2  298.35
  5196.5     296  5405.5  297.23  5521.9  296.28  5650.4   296.9  5772.9  300.38
  5901.4  302.14  5967.1   301.4  6131.5  306.78  6355.4   317.3  6477.3  329.02
#Mann= 5 ,-1 , 0
  3935.2     .05       0  4600.7     .16       0    5002     .07       0
  5002.5     .16       0  6131.5     .05       0
#XS Ineff= 1 ,-1
 5054.55  6126.7  304.12
Permanent Ineff=
       F
Bank Sta=4628.8,5772.9
XS Rating Curve= 0 ,0
Exp/Cntr=0.3,0.1

Type RM Length L Ch R = 1 ,3900    ,434,434,434
BEGIN DESCRIPTION:
UNT 116 IN UKCR 6.0
END DESCRIPTION:
XS GIS Cut Line= 3
      3652299.59      10574610.2      3653099.61     10573910.19
      3653899.57     10573910.19
#Sta/Elev= 30
  3941.1  330.08  4061.2  322.68  4097.3  319.64  4103.9  317.75  4132.4  315.21
    4196   312.5    4232  309.49  4273.8  311.38  4316.5  305.05  4389.3     302
  4416.2   301.2  4586.1  297.95  4805.3  295.27  4990.4  296.17    4994  291.51
  4996.8  291.01  4997.3  291.01    5000  291.51  5000.8  293.97  5024.1  295.88
  5194.1  295.75  5214.1  293.11  5224.1  295.27  5234.1  295.58  5494.1  293.91
  5634.1  298.07  5654.1  299.08  5704.1  300.98  5754.1  306.66  5804.1  310.32
#Mann= 6 ,-1 , 0
  3941.1     .05       0  4389.3     .12       0  4416.2     .16       0
  4996.8     .07       0  4997.3     .16       0  5654.1     .05       0
#XS Ineff= 1 ,-1
 5150.57 5731.53  299.82
Permanent Ineff=
       F
Bank Sta=4586.1,5634.1
XS Rating Curve= 0 ,0
Exp/Cntr=0.3,0.1

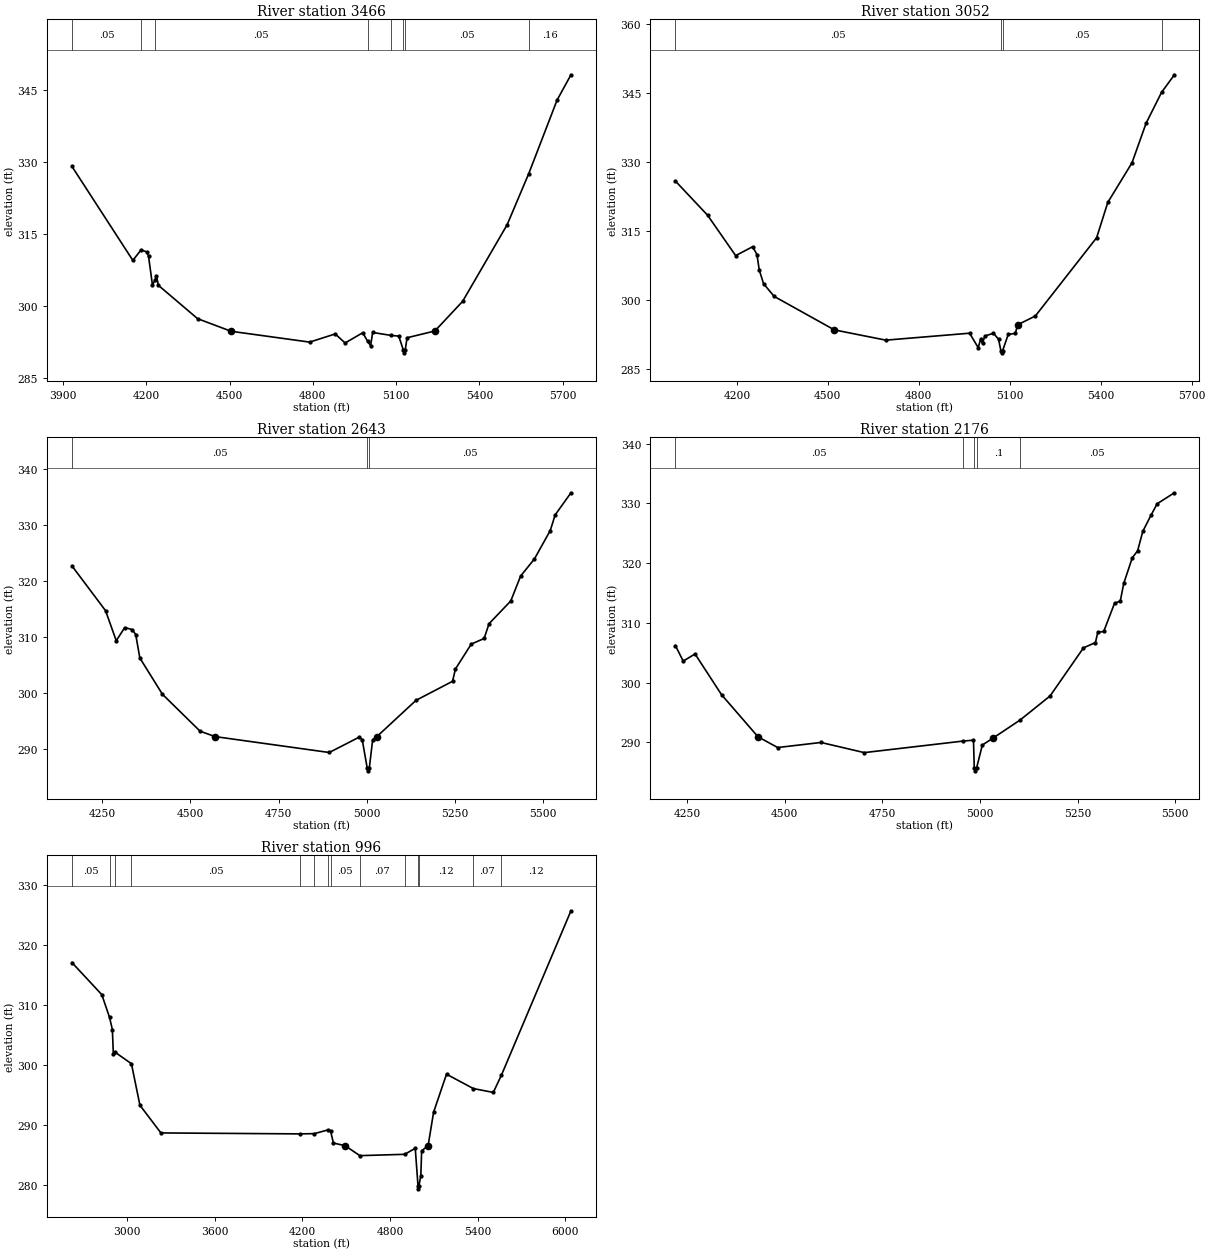
Type RM Length L Ch R = 1 ,3466    ,414,414,414
BEGIN DESCRIPTION:
UNT 116 IN UKCR 5.0
END DESCRIPTION:
XS GIS Cut Line= 3
      3652599.63     10574960.17      3653399.61     10574210.19
      3654099.65     10574210.19
#Sta/Elev= 30
  3932.7  329.03    4152  309.49  4181.6  311.68  4201.6  311.26  4208.4  310.38
  4222.6  304.39  4231.4  305.33  4236.7  306.34  4244.1   304.3  4385.2  297.37
  4505.9  294.75  4788.7   292.5  4880.5   294.2  4916.2  292.32  4979.7  294.45
  4997.2  292.67    5008  291.74  5015.3  294.51  5080.9   293.9  5109.3  293.75
  5126.3  290.77    5129  290.27  5132.3  290.77  5139.3  293.41  5239.3  294.81
  5339.3  300.98  5499.3  316.88  5577.4  327.54  5679.3  342.82  5729.3  348.08
#Mann= 8 ,-1 , 0
  3932.7     .05       0  4181.6     .08       0  4231.4     .05       0
  4997.2     .12       0  5080.9     .05       0  5126.3     .07       0
  5132.3     .05       0  5577.4     .16       0
Bank Sta=4505.9,5239.3
XS Rating Curve= 0 ,0
Exp/Cntr=0.3,0.1

Type RM Length L Ch R = 1 ,3052    ,409,409,409
BEGIN DESCRIPTION:
UNT 116 IN UKCR 4.0
END DESCRIPTION:
XS GIS Cut Line= 3
      3652799.59      10575260.2      3653599.61     10574560.19
      3654099.58     10574260.21
#Sta/Elev= 30
    3997  325.85  4103.3   318.4  4195.9  309.62  4251.9  311.56  4266.1  309.86
  4273.7  306.51  4287.9  303.51    4323  300.75  4521.4  293.47  4691.3  291.24
  4967.5  292.75    4996   289.6  5003.6   291.4  5010.2  290.54  5017.8  292.14
  5046.3  292.74    5063  291.44  5070.6  288.98  5073.4  288.48  5076.6  288.98
    5095  292.49  5118.3  292.71  5126.1  294.58  5184.4  296.49  5386.6  313.52
  5423.5  321.21  5503.2   329.8  5549.8  338.43  5600.7  345.12  5643.1  348.95
#Mann= 4 ,-1 , 0
    3997     .05       0  5070.6     .03       0  5076.6     .05       0
  5600.7     .16       0
Bank Sta=4521.4,5126.1
XS Rating Curve= 0 ,0
Exp/Cntr=0.3,0.1

Type RM Length L Ch R = 1 ,2643    ,467,467,467
BEGIN DESCRIPTION:
UNT 116 IN UKCR 3.0
END DESCRIPTION:
XS GIS Cut Line= 3
      3652899.58      10575260.2      3653699.61     10574960.19
      3654199.65     10574710.17
#Sta/Elev= 30
  4164.9  322.69  4260.2  314.67  4290.4   309.3  4314.5  311.66  4335.8  311.29
  4345.6   310.4  4357.2  306.22  4421.3  299.72  4528.1  293.11  4570.8  292.15
  4893.8  289.31  4979.3  292.08  4987.3  291.56  5001.2  286.53    5004  286.03
  5007.2  286.53  5016.7  291.58  5027.7   292.1  5139.5  298.64  5242.9  302.04
  5251.3  304.26    5296   308.7  5332.4   309.7  5346.4  312.35  5407.9  316.41
  5435.8  320.87  5474.9  323.93  5519.7     329  5533.6   331.8  5578.4  335.76
#Mann= 3 ,-1 , 0
  4164.9     .05       0  5001.2     .03       0  5007.2     .05       0
Bank Sta=4570.8,5027.7
XS Rating Curve= 0 ,0
Exp/Cntr=0.3,0.1

Type RM Length L Ch R = 1 ,2176    ,1180,1180,1180
BEGIN DESCRIPTION:
UNT 116 IN UKCR 2.0
END DESCRIPTION:
XS GIS Cut Line= 3
      3653199.63     10575410.19      3653999.61     10575310.19
      3654249.61     10574910.19
#Sta/Elev= 30
  4220.2  306.19  4240.3  303.59  4270.6  304.78  4338.6  297.95  4431.8  290.92
  4482.2  289.12  4593.1  289.97  4703.9  288.27  4956.6   290.2  4983.6  290.35
  4985.6  285.72  4988.4  285.22  4991.6  285.72  5006.3  289.54  5034.1  290.72
  5102.9  293.72  5179.7  297.75  5265.2   305.8  5295.9  306.69  5301.8  308.39
  5317.1  308.55  5344.8  313.26  5359.5  313.63  5368.4   316.6  5390.2  320.87
  5403.8  322.04  5417.3  325.32  5439.1  328.12  5453.9  329.92  5498.1  331.76
#Mann= 5 ,-1 , 0
  4220.2     .05       0  4956.6      .1       0  4985.6     .07       0
  4991.6      .1       0  5102.9     .05       0
Bank Sta=4431.8,5034.1
XS Rating Curve= 0 ,0
Exp/Cntr=0.3,0.1

Type RM Length L Ch R = 1 ,996     ,0,0,0
BEGIN DESCRIPTION:
UNT 116 IN UKCR 1.0
END DESCRIPTION:
XS GIS Cut Line= 4
      3652934.76     10575354.77      3654291.07     10576201.11
      3655094.02     10575767.08      3654931.26      10574877.3
#Sta/Elev= 30
  2622.6  317.12    2827  311.77    2880  307.97  2899.4  305.94    2906  301.92
  2916.1  302.19  3029.9  300.24    3088  293.31  3231.6  288.69    4182  288.53
  4282.4  288.57  4372.8  289.18  4392.6  289.03  4412.9     287  4492.5  286.56
  4593.5   284.9  4899.9  285.12  4972.7  286.12  4991.6  279.86  4994.3  279.36
  4997.6  279.86  5010.8  281.52  5016.5  285.71  5060.8  286.57  5098.3  292.15
  5186.6  298.49  5370.6  296.09    5507  295.45  5562.9  298.35  6038.6  325.76
#Mann= 14 ,-1 , 0
  2622.6     .05       0    2880     .07       0  2916.1     .08       0
  3029.9     .05       0    4182     .07       0  4282.4     .15       0
  4372.8     .07       0  4392.6     .05       0  4593.5     .07       0
  4899.9     .12       0  4991.6     .07       0  4997.6     .12       0
  5370.6     .07       0  5562.9     .12       0
Bank Sta=4492.5,5060.8
XS Rating Curve= 0 ,0
Exp/Cntr=0.3,0.1

Chan Stop Cuts=-1
Use User Specified Reach Order=0
Composite Channel Slope=5