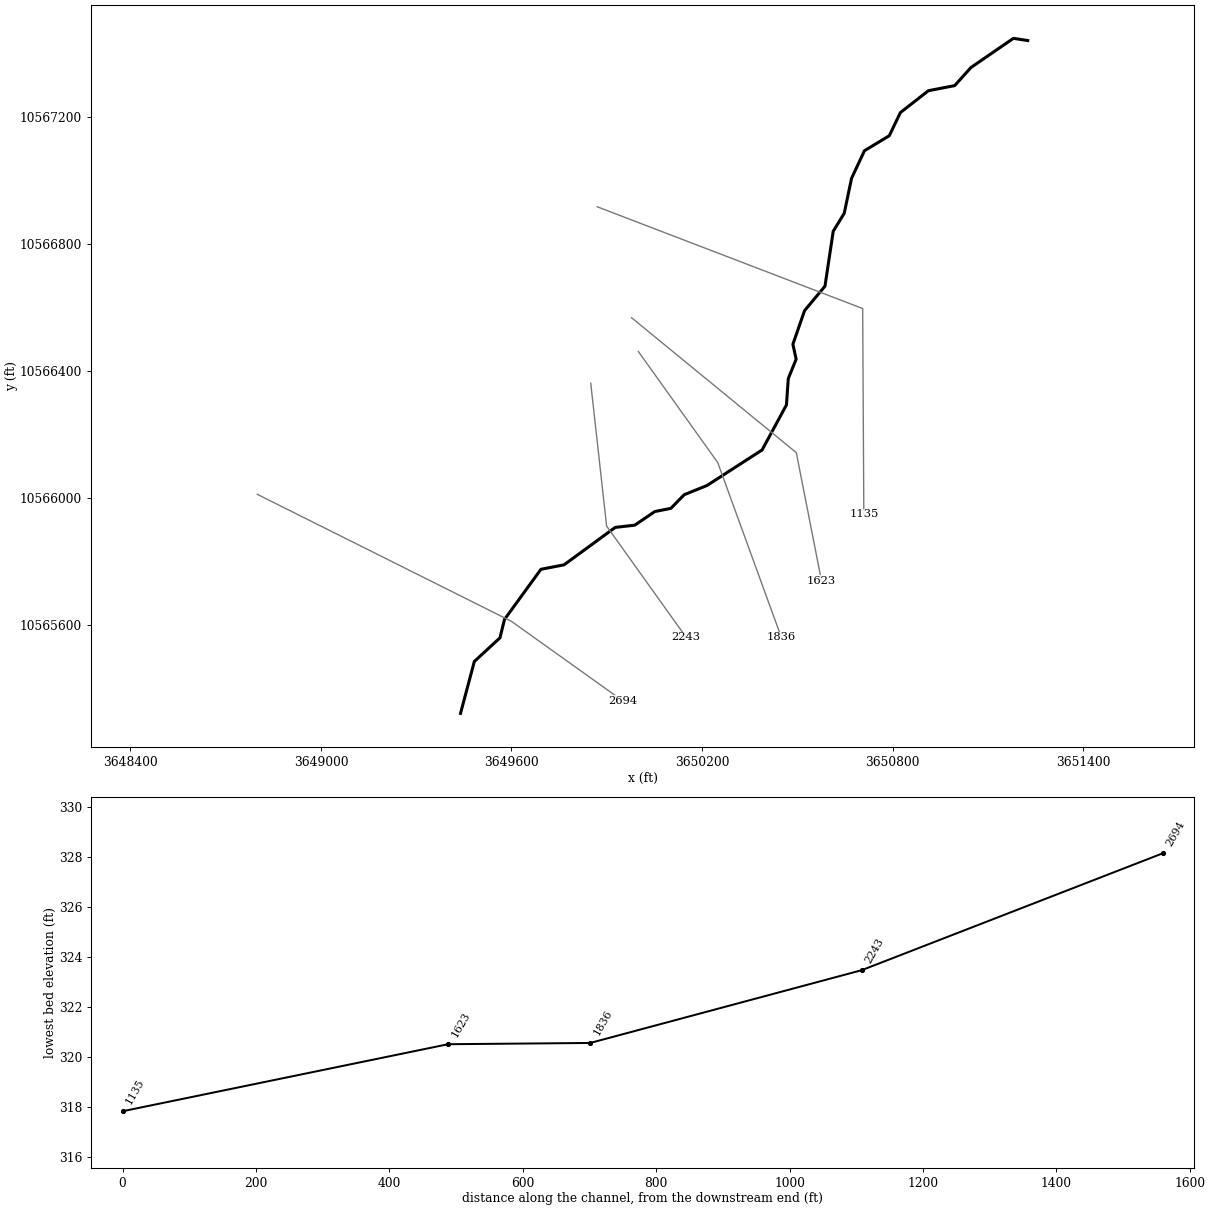
--- UNT 117 IN UKCR.prj (project) ---

Proj Title=UNT 117 IN UKCR Base Level Engineering
Current Plan=p01
Default Exp/Contr=0.3,0.1
English Units
Geom File=g01
Flow File=f01
Plan File=p01
BEGIN DESCRIPTION:
UNT 117 IN UKCR
END DESCRIPTION:

--- UNT 117 IN UKCR.p01 (plan) ---

Plan Title=Multiple Run
Short Identifier=Multiple
Geom File=g01
Flow File=f01
Subcritical Flow
K Sum by GR= 0
Std Step Tol= 0.01
Critical Tol= 0.01
Num of Std Step Trials= 20
Max Error Tol= 0.3
Flow Tol Ratio= 0.001
Split Flow NTrial= 30
Split Flow Tol= 0.02
Split Flow Ratio= 0.02
Log Output Level= 0
Friction Slope Method= 1
Unsteady Friction Slope Method= 2
Unsteady Bridges Friction Slope Method= 1
Parabolic Critical Depth
Global Vel Dist=  1 , 1 , 1
Global Log Level= 0
CheckData=True
Encroach Param= -1, 0, 0, 0
BEGIN DESCRIPTION:
Multiple Run
END DESCRIPTION:

--- UNT 117 IN UKCR.f01 (steady flow) ---

Flow Title=Multiple
Number of Profiles=7
Profile Names=10-year,25-year,50-year,1pct_min,100-year,1pct_plu,500-year
River Rch & RM= UNT 117 IN UKCR,Reach-1,2694
     842    1179    1466    1339    1810    2448    2773
Boundary for River Rch & Prof#=UNT 117 IN UKCR,Reach-1,1
Up Type=0
Dn Type=3
Dn Slope=0.005
Boundary for River Rch & Prof#=UNT 117 IN UKCR,Reach-1,2
Up Type=0
Dn Type=3
Dn Slope=0.005
Boundary for River Rch & Prof#=UNT 117 IN UKCR,Reach-1,3
Up Type=0
Dn Type=3
Dn Slope=0.005
Boundary for River Rch & Prof#=UNT 117 IN UKCR,Reach-1,4
Up Type=0
Dn Type=3
Dn Slope=0.005
Boundary for River Rch & Prof#=UNT 117 IN UKCR,Reach-1,5
Up Type=0
Dn Type=3
Dn Slope=0.005
Boundary for River Rch & Prof#=UNT 117 IN UKCR,Reach-1,6
Up Type=0
Dn Type=3
Dn Slope=0.005
Boundary for River Rch & Prof#=UNT 117 IN UKCR,Reach-1,7
Up Type=0
Dn Type=3
Dn Slope=0.005

--- UNT 117 IN UKCR.g01 (geometry) ---

Geom Title=Existing Conditions

River Reach=UNT 117 IN UKCR,Reach-1
Reach XY= 30
      3649439.50     10565320.00      3649483.06     10565483.63
      3649563.75     10565558.00      3649578.00     10565616.00
      3649692.75     10565774.00      3649765.50     10565788.00
      3649926.75     10565906.00      3649988.25     10565913.00
      3650051.50     10565956.00      3650102.00     10565966.00
      3650144.00     10566009.00      3650215.75     10566038.00
      3650389.25     10566150.00      3650466.00     10566292.00
      3650471.75     10566375.00      3650496.50     10566436.00
      3650486.25     10566483.00      3650523.00     10566589.00
      3650587.25     10566666.00      3650613.25     10566839.00
      3650648.00     10566896.00      3650671.00     10567006.00
      3650711.75     10567093.00      3650789.75     10567140.00
      3650824.75     10567213.00      3650913.00     10567282.00
      3650995.75     10567298.00      3651047.00     10567355.00
      3651180.75     10567447.00      3651226.00     10567440.00

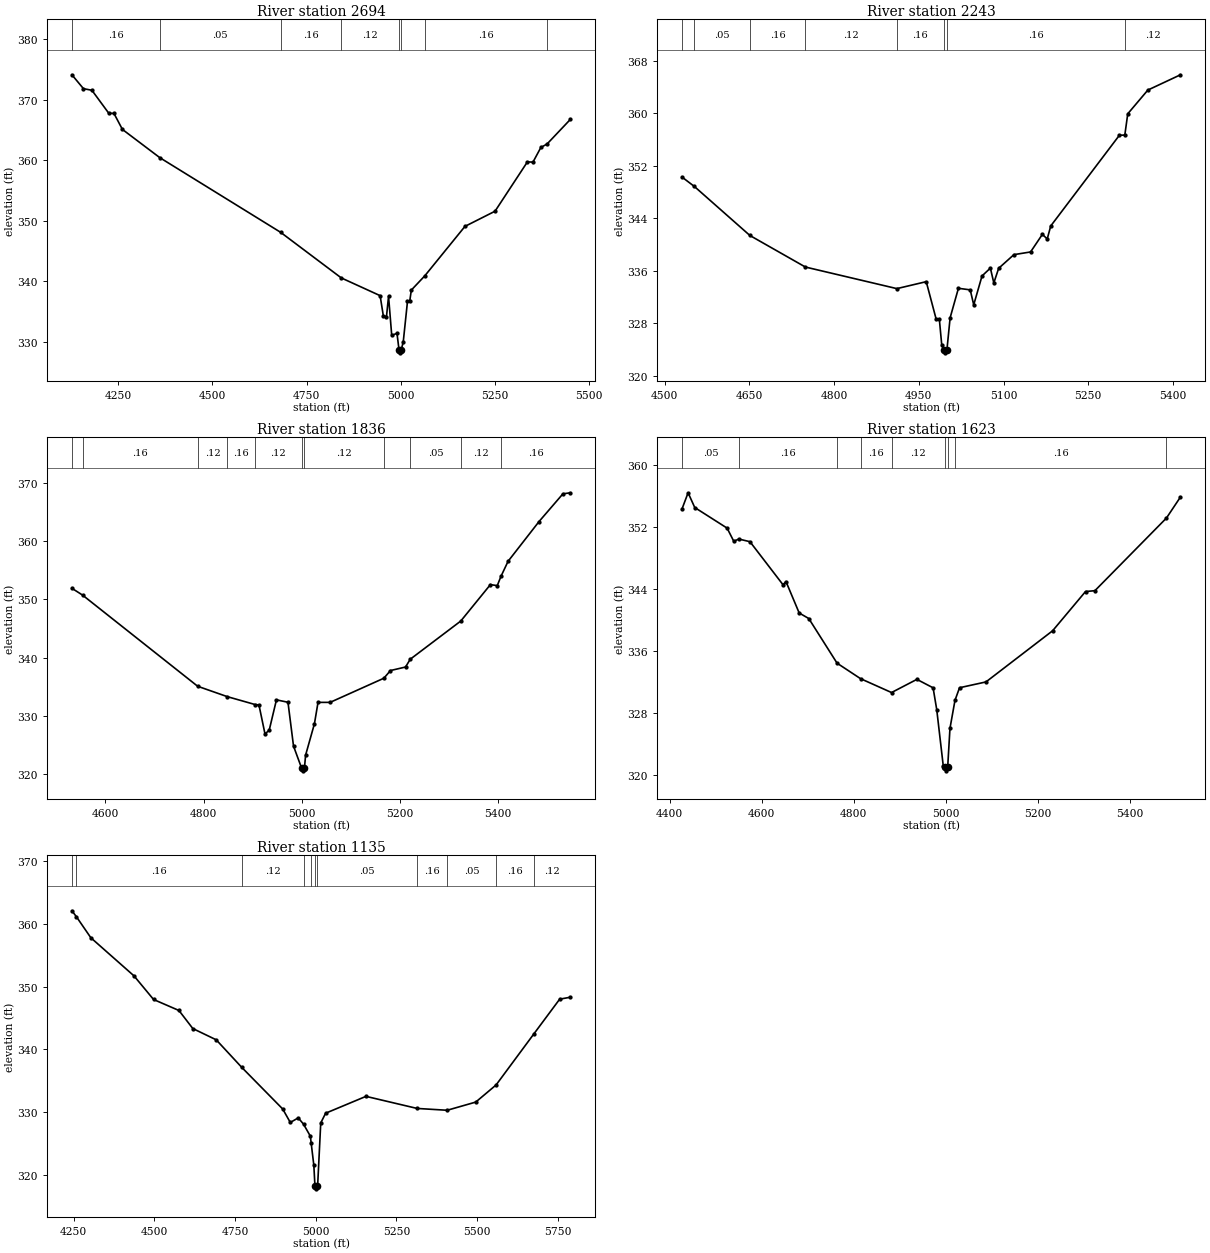
Type RM Length L Ch R = 1,2694,451,451,451
BEGIN DESCRIPTION:
UNT 117 IN UKCR 4.0
END DESCRIPTION:
XS GIS Cut Line= 3
      3648799.62     10566010.18      3649599.61     10565610.19
      3649949.58     10565360.21
#Sta/Elev= 30
  4126.7  374.16  4157.4  371.86  4179.8  371.60  4224.5  367.81  4238.5  367.76
  4260.9  365.12  4360.2  360.45  4681.2  348.10  4842.5  340.55  4945.6  337.62
  4954.0  334.32  4962.4  334.11  4968.0  337.50  4976.4  331.05  4990.4  331.39
  4995.8  328.66  4998.5  328.16  5001.8  328.66  5007.1  330.01  5018.3  336.67
  5024.2  336.67  5028.5  338.54  5064.3  340.90  5171.0  349.08  5250.9  351.59
  5336.9  359.75  5351.7  359.71  5372.6  362.13  5389.3  362.72  5451.2  366.79
#Mann=8,-1,0
  4126.7    0.16       0  4360.2    0.05       0  4681.2    0.16       0
  4842.5    0.12       0  4995.8    0.07       0  5001.8    0.12       0
  5064.3    0.16       0  5389.3    0.12       0
Bank Sta=4995.8,5001.8
Exp/Cntr=0.3,0.1

Type RM Length L Ch R = 1,2243,407,407,407
BEGIN DESCRIPTION:
UNT 117 IN UKCR 3.0
END DESCRIPTION:
XS GIS Cut Line= 3
      3649849.61     10566360.18      3649899.61     10565910.19
      3650149.62     10565560.17
#Sta/Elev= 30
  4530.5  350.29  4552.5  348.85  4650.8  341.38  4749.1  336.57  4911.1  333.28
  4963.1  334.34  4980.7  328.62  4986.3  328.62  4990.6  324.67  4993.8  323.99
  4996.5  323.49  4999.8  323.99  5005.4  328.83  5020.1  333.33  5041.0  333.09
  5047.2  330.81  5061.9  335.21  5076.7  336.41  5082.8  334.15  5091.4  336.38
  5118.4  338.46  5147.9  338.87  5168.8  341.55  5177.4  340.85  5183.6  342.83
  5305.2  356.66  5314.8  356.69  5320.0  359.93  5355.6  363.55  5413.4  365.88
#Mann=8,-1,0
  4530.5     0.1       0  4552.5    0.05       0  4650.8    0.16       0
  4749.1    0.12       0  4911.1    0.16       0  4993.8    0.07       0
  4999.8    0.16       0  5314.8    0.12       0
Bank Sta=4993.8,4999.8
Exp/Cntr=0.3,0.1

Type RM Length L Ch R = 1,1836,213,213,213
BEGIN DESCRIPTION:
UNT 117 IN UKCR 2.0
END DESCRIPTION:
XS GIS Cut Line= 3
      3649999.59     10566460.21      3650249.61     10566110.19
      3650449.62     10565560.17
#Sta/Elev= 30
  4531.7  351.88  4553.3  350.72  4787.9  335.08  4848.3  333.30  4905.2  331.94
  4912.7  331.88  4925.0  326.90  4933.6  327.56  4948.3  332.75  4971.8  332.34
  4983.1  324.82  4999.4  321.08  5002.2  320.58  5005.4  321.08  5007.7  323.27
  5025.7  328.66  5033.0  332.32  5057.6  332.32  5167.1  336.46  5180.6  337.78
  5211.2  338.38  5220.9  339.72  5323.8  346.27  5384.1  352.51  5398.1  352.34
  5405.6  353.92  5420.1  356.51  5483.2  363.33  5531.8  368.08  5547.1  368.26
#Mann=11,-1,0
  4531.7    0.05       0  4553.3    0.16       0  4787.9    0.12       0
  4848.3    0.16       0  4905.2    0.12       0  4999.4    0.07       0
  5005.4    0.12       0  5167.1    0.16       0  5220.9    0.05       0
  5323.8    0.12       0  5405.6    0.16       0
Bank Sta=4999.4,5005.4
Exp/Cntr=0.3,0.1

Type RM Length L Ch R = 1,1623,488,488,488
BEGIN DESCRIPTION:
Mapping XS 515d893b
END DESCRIPTION:
XS GIS Cut Line= 3
      3649978.06     10566566.73      3650497.01     10566141.48
      3650576.30     10565737.82
#Sta/Elev= 30
  4426.9  354.30  4440.2  356.40  4454.6  354.50  4524.9  351.84  4539.3  350.15
  4550.4  350.43  4574.5  350.09  4646.2  344.54  4652.7  344.95  4681.4  340.89
  4702.2  340.18  4763.6  334.42  4814.6  332.42  4881.9  330.63  4936.9  332.33
  4972.1  331.24  4980.0  328.43  4994.3  321.10  4997.8  321.03  5000.5  320.53
  5003.8  321.03  5008.7  326.00  5019.6  329.62  5029.5  331.25  5086.9  332.00
  5231.6  338.60  5303.0  343.66  5323.4  343.77  5478.7  353.14  5509.2  355.86
#Mann=9,-1,0
  4426.9    0.05       0  4550.4    0.16       0  4763.6    0.12       0
  4814.6    0.16       0  4881.9    0.12       0  4997.8    0.07       0
  5003.8    0.12       0  5019.6    0.16       0  5478.7    0.12       0
Bank Sta=4997.8,5003.8
Exp/Cntr=0.3,0.1

Type RM Length L Ch R = 1,1135,0,0,0
BEGIN DESCRIPTION:
UNT 117 IN UKCR 1.0
END DESCRIPTION:
XS GIS Cut Line= 3
      3649869.97     10566916.31      3650706.04     10566595.57
      3650709.64     10565946.86
#Sta/Elev= 30
  4244.8  362.05  4258.4  361.13  4303.5  357.76  4437.2  351.70  4497.7  347.95
  4576.4  346.20  4619.3  343.33  4691.8  341.54  4770.7  337.17  4897.8  330.54
  4921.3  328.40  4945.9  329.13  4962.3  328.13  4983.4  326.22  4985.8  325.19
  4994.2  321.59  4997.6  318.35  5000.4  317.85  5003.6  318.35  5006.0  318.36
  5015.6  328.32  5030.7  329.87  5155.7  332.55  5314.1  330.63  5407.2  330.34
  5495.7  331.64  5558.7  334.36  5676.2  342.51  5755.7  348.00  5789.0  348.31
#Mann=11,-1,0
  4244.8    0.05       0  4258.4    0.16       0  4770.7    0.12       0
  4962.3    0.16       0  4985.8    0.05       0  4997.6    0.03       0
  5003.6    0.05       0  5314.1    0.16       0  5407.2    0.05       0
  5558.7    0.16       0  5676.2    0.12       0
Bank Sta=4997.6,5003.6
Exp/Cntr=0.3,0.1

Chan Stop Cuts=-1