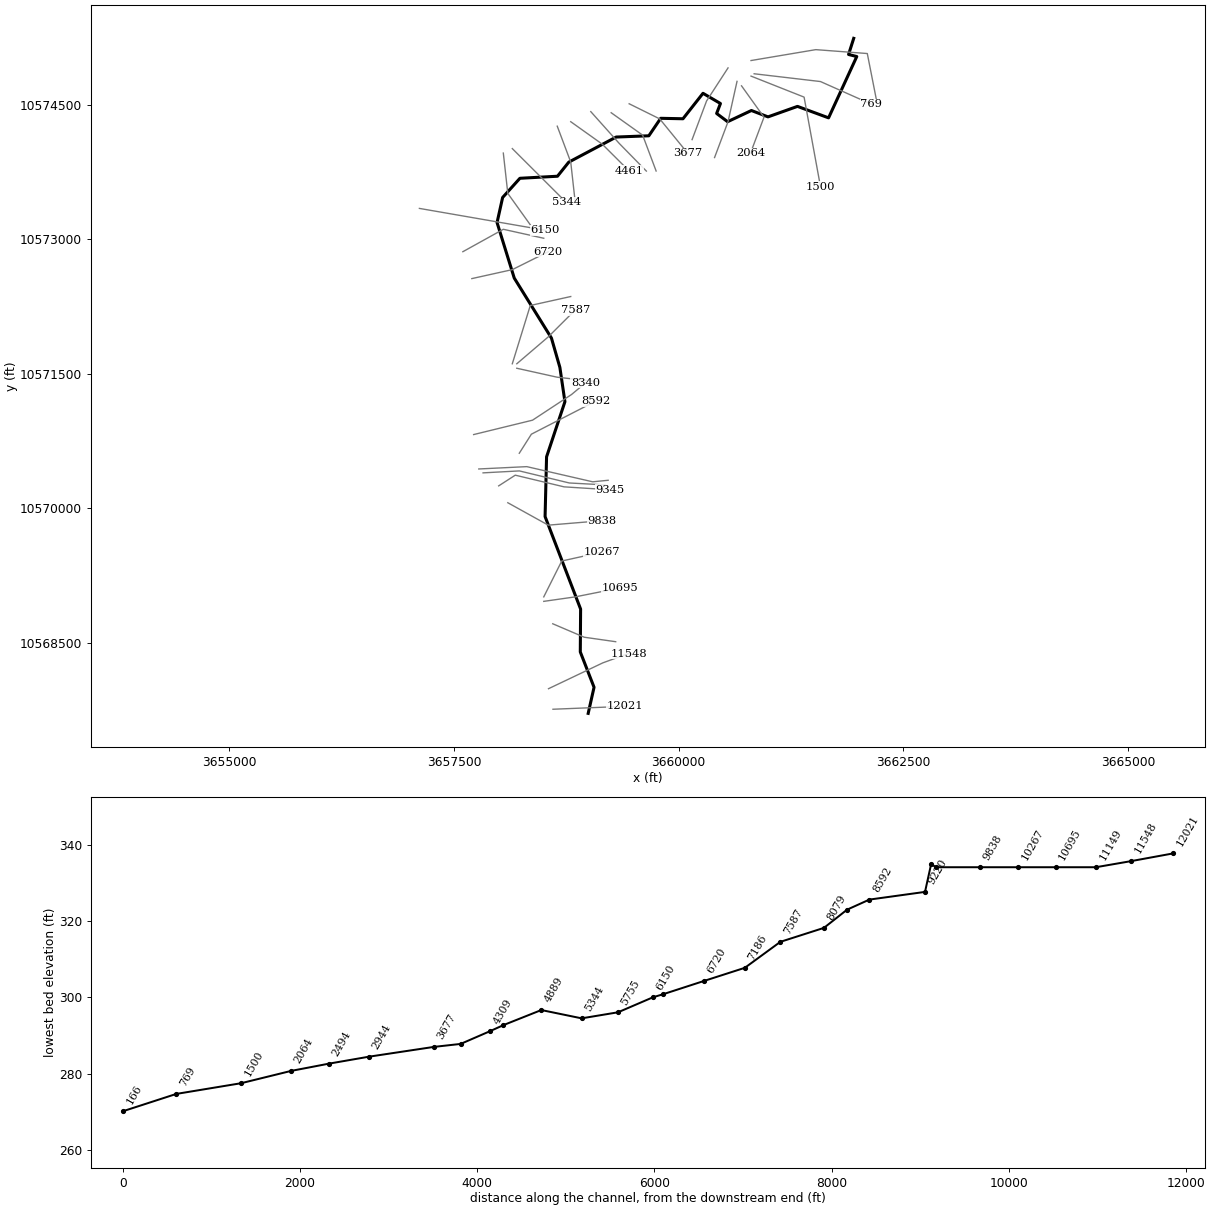
--- UNT 119 IN UKCR.prj (project) ---

Proj Title=UNT 119 IN UKCR Base Level Engineering
Current Plan=p01
Default Exp/Contr=0.3,0.1
English Units
Geom File=g01
Flow File=f01
Plan File=p01
Y Axis Title=Elevation
X Axis Title(PF)=Main Channel Distance
X Axis Title(XS)=Station
BEGIN DESCRIPTION:
UNT 119 IN UKCR
END DESCRIPTION:
DSS Export Rating Curves= 0
DSS Export Rating Curve Sorted= 0
DSS Export Volume Flow Curves= 0
DXF OffsetX= 0
DXF OffsetY= 0
DXF ScaleX= 1
DXF ScaleY= 10

--- UNT 119 IN UKCR.p01 (plan) ---

Plan Title=Multiple Run
Short Identifier=Multiple
Geom File=g01
Flow File=f01
Subcritical Flow
K Sum by GR= 0
Std Step Tol= 0.01
Critical Tol= 0.01
Num of Std Step Trials= 20
Max Error Tol= 0.3
Flow Tol Ratio= 0.001
Split Flow NTrial= 30
Split Flow Tol= 0.02
Split Flow Ratio= 0.02
Log Output Level= 0
Friction Slope Method= 1
Unsteady Friction Slope Method= 2
Unsteady Bridges Friction Slope Method= 1
Parabolic Critical Depth
Global Vel Dist=  1 , 1 , 1
Global Log Level= 0
CheckData=True
Encroach Param= -1, 0, 0, 0
BEGIN DESCRIPTION:
Multiple Run
END DESCRIPTION:

--- UNT 119 IN UKCR.f01 (steady flow) ---

Flow Title=Multiple
Program Version=4.10
Number of Profiles= 7
Profile Names=10-year,25-year,50-year,1pct_min,100-year,1pct_plu,500-year
River Rch & RM=UNT 119 IN UKCR,Reach-1         ,12021
     539     730     888     794    1073    1451    1576
River Rch & RM=UNT 119 IN UKCR,Reach-1         ,9838
     679     928    1136    1021    1381    1867    2049
Boundary for River Rch & Prof#=UNT 119 IN UKCR,Reach-1         , 1
Up Type= 0
Dn Type= 3
Dn Slope=0.005
Boundary for River Rch & Prof#=UNT 119 IN UKCR,Reach-1         , 2
Up Type= 0
Dn Type= 3
Dn Slope=0.005
Boundary for River Rch & Prof#=UNT 119 IN UKCR,Reach-1         , 3
Up Type= 0
Dn Type= 3
Dn Slope=0.005
Boundary for River Rch & Prof#=UNT 119 IN UKCR,Reach-1         , 4
Up Type= 0
Dn Type= 3
Dn Slope=0.005
Boundary for River Rch & Prof#=UNT 119 IN UKCR,Reach-1         , 5
Up Type= 0
Dn Type= 3
Dn Slope=0.005
Boundary for River Rch & Prof#=UNT 119 IN UKCR,Reach-1         , 6
Up Type= 0
Dn Type= 3
Dn Slope=0.005
Boundary for River Rch & Prof#=UNT 119 IN UKCR,Reach-1         , 7
Up Type= 0
Dn Type= 3
Dn Slope=0.005
DSS Import GetInterval= 0
DSS Import GetPeak= 0
DSS Import FillOption= 0

--- UNT 119 IN UKCR.g01 (geometry) ---

Geom Title=Existing Conditions
Program Version=4.10

River Reach=UNT 119 IN UKCR ,Reach-1
Reach XY= 30
      3658993.77     10567710.77        3659059.       10568002.
        3658906.       10568396.       3658909.5       10568874.
      3658514.25       10569906.      3658530.75       10570572.
        3658735.       10571187.      3658678.75       10571570.
        3658585.       10571897.      3658171.25       10572566.
        3657980.       10573185.        3658042.       10573465.
      3658234.25       10573679.      3658652.25       10573702.
      3658777.75       10573859.        3659305.       10574139.
       3659668.5       10574153.       3659800.5       10574348.
      3660048.25       10574343.        3660271.       10574627.
      3660465.25       10574513.      3660422.75       10574402.
      3660544.75       10574310.      3660809.75       10574435.
      3660994.25       10574364.      3661322.25       10574481.
        3661668.       10574353.      3661981.75       10575037.
       3661890.5       10575060.      3661947.75       10575240.

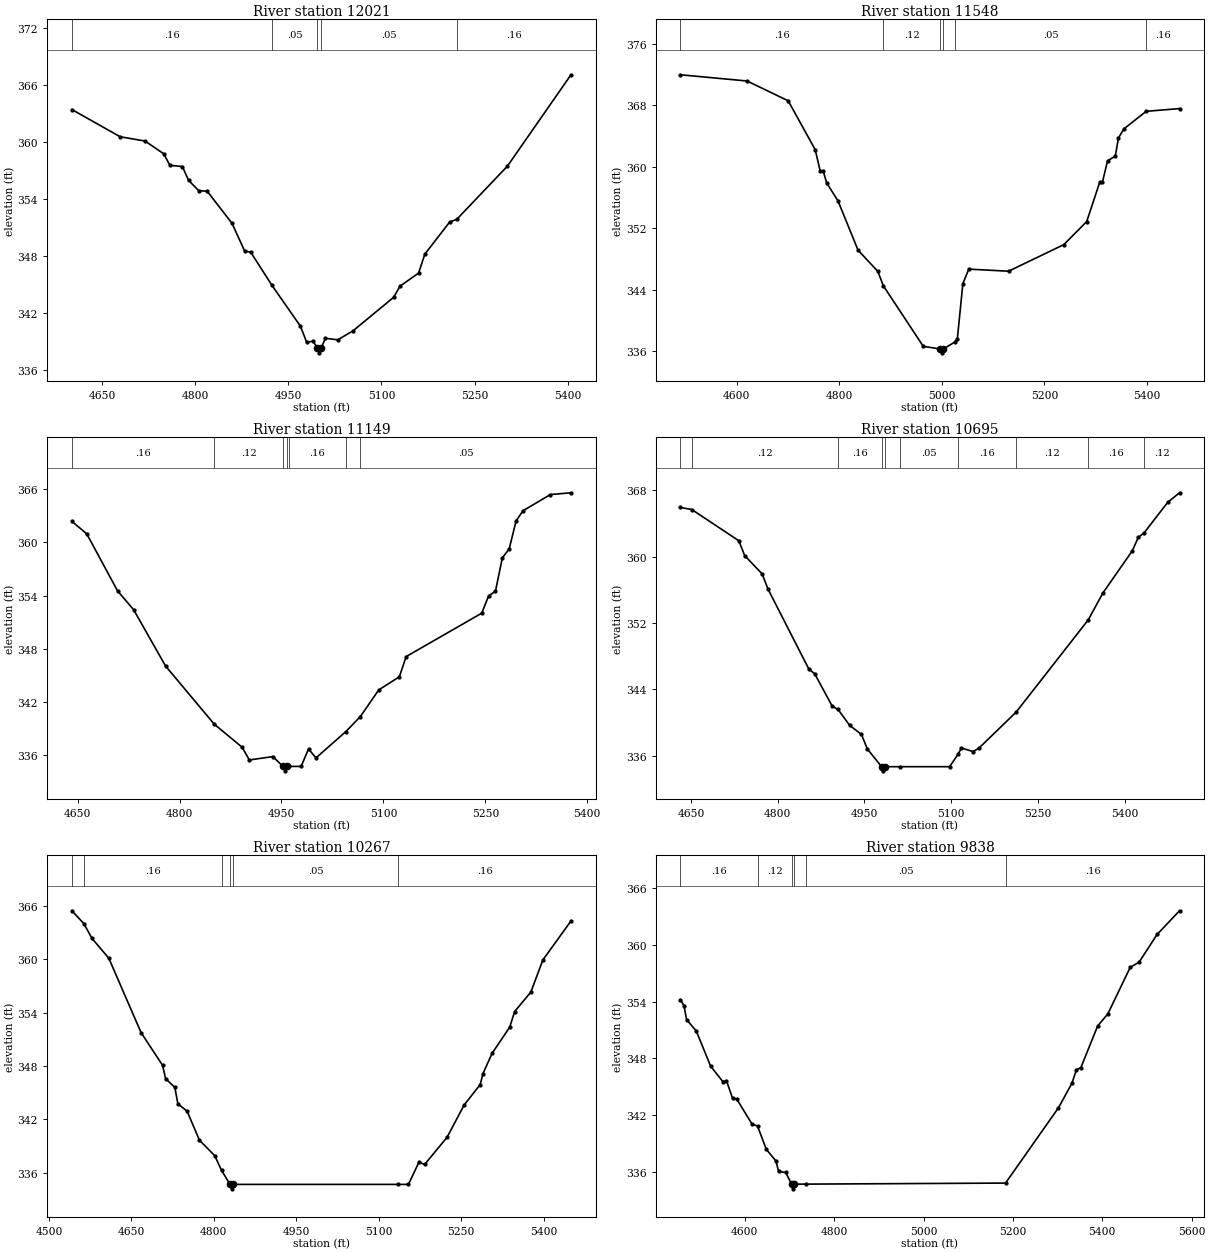
Type RM Length L Ch R = 1 ,12021   ,473,473,473
BEGIN DESCRIPTION:
UNT 119 IN UKCR 23.0
END DESCRIPTION:
XS GIS Cut Line= 2
      3658601.96     10567756.87       3659404.7     10567789.42
#Sta/Elev= 30
  4601.7   363.4  4679.4  360.54  4719.4  360.09  4749.5  358.75  4759.5  357.53
  4779.5  357.41  4789.5  355.95  4805.8  354.87  4819.5  354.81  4859.6  351.42
  4879.6  348.53  4889.6  348.39  4923.8   344.9  4969.6  340.61  4979.7   338.9
  4989.7  339.05    4997  338.31  4999.8  337.81    5003  338.31  5009.7  339.34
  5029.7  339.18  5054.3  340.13  5119.8  343.66  5129.8  344.82  5159.8   346.2
  5169.8  348.19  5209.8  351.57    5221  351.84  5302.8  357.45  5405.1  367.06
#Mann= 5 ,-1 , 0
  4601.7     .16       0  4923.8     .05       0    4997     .04       0
    5003     .05       0    5221     .16       0
Bank Sta=4997,5003
XS Rating Curve= 0 ,0
Exp/Cntr=0.3,0.1

Type RM Length L Ch R = 1 ,11548   ,399,399,399
BEGIN DESCRIPTION:
Mapping XS 60285626
END DESCRIPTION:
XS GIS Cut Line= 3
      3658552.47     10567986.04      3659156.63     10568274.23
       3659441.4     10568378.41
#Sta/Elev= 30
  4490.6     372  4620.4  371.19  4700.6  368.61  4753.3  362.23  4763.1  359.42
  4768.6  359.52  4775.5  357.93  4797.7  355.57  4836.7  349.16  4875.2   346.4
  4886.1  344.51  4963.8  336.64    4997  336.29  4999.8  335.79    5003  336.29
  5026.1  337.23  5030.3  337.65    5041   344.8  5052.5  346.69    5130  346.42
  5237.7  349.88  5282.4  352.89  5307.6  357.98  5312.9  357.98  5322.9  360.79
  5338.1  361.41  5344.2  363.78  5354.8  364.95  5398.2  367.24  5463.2   367.6
#Mann= 6 ,-1 , 0
  4490.6     .16       0  4886.1     .12       0    4997     .07       0
    5003     .12       0  5026.1     .05       0  5398.2     .16       0
Bank Sta=4997,5003
XS Rating Curve= 0 ,0
Exp/Cntr=0.3,0.1

Type RM Length L Ch R = 1 ,11149   ,454,454,454
BEGIN DESCRIPTION:
UNT 119 IN UKCR 22.0
END DESCRIPTION:
XS GIS Cut Line= 3
      3658599.58      10568710.2      3658949.61     10568560.19
      3659299.63     10568510.19
#Sta/Elev= 30
  4641.6  362.38  4663.4  360.98  4708.7  354.53  4732.3  352.41  4779.4  346.03
  4851.1  339.45  4891.9  336.86  4902.7  335.41  4937.2  335.79  4952.3  334.68
  4955.1  334.18  4958.3  334.68  4960.6  334.68  4978.9  334.68  4989.8  336.66
  5000.7  335.64  5044.7  338.62  5066.1  340.32  5093.1  343.33  5123.4  344.81
  5133.5   347.1  5244.7  352.01  5254.8  353.96  5264.9  354.49    5275  358.27
  5285.1  359.28  5295.2  362.43  5305.3  363.58  5345.7  365.42    5376  365.62
#Mann= 7 ,-1 , 0
  4641.6     .16       0  4851.1     .12       0  4952.3     .07       0
  4958.3     .12       0  4960.6     .16       0  5044.7     .12       0
  5066.1     .05       0
Bank Sta=4952.3,4958.3
XS Rating Curve= 0 ,0
Exp/Cntr=0.3,0.1

Type RM Length L Ch R = 1 ,10695   ,428,428,428
BEGIN DESCRIPTION:
UNT 119 IN UKCR 21.0
END DESCRIPTION:
XS GIS Cut Line= 3
      3658499.65     10568960.19      3658849.61     10569010.19
      3659349.59     10569110.18
#Sta/Elev= 30
  4631.6  365.94  4651.3  365.69  4732.6  361.92  4742.7  360.14    4773  357.92
  4783.1  356.09  4853.8  346.44  4863.9  345.88  4894.2  341.97  4904.1  341.59
  4924.5  339.65  4944.7  338.58  4954.8  336.83  4979.6  334.68  4982.3  334.18
  4985.6  334.68    5012  334.68  5097.3  334.68  5112.1  336.21  5117.7  336.93
  5138.1   336.5  5148.3  336.94  5212.2  341.25  5337.2  352.39  5362.4  355.62
  5413.4  360.72  5423.6  362.32  5433.8  362.88  5474.6  366.56    5495  367.71
#Mann= 10 ,-1 , 0
  4631.6     .16       0  4651.3     .12       0  4904.1     .16       0
  4979.6     .07       0  4985.6     .16       0    5012     .05       0
  5112.1     .16       0  5212.2     .12       0  5337.2     .16       0
  5433.8     .12       0
Bank Sta=4979.6,4985.6
XS Rating Curve= 0 ,0
Exp/Cntr=0.3,0.1

Type RM Length L Ch R = 1 ,10267   ,429,429,429
BEGIN DESCRIPTION:
UNT 119 IN UKCR 20.0
END DESCRIPTION:
XS GIS Cut Line= 3
      3658499.62      10569010.2      3658699.61     10569410.19
      3659149.63     10569510.19
#Sta/Elev= 30
  4541.7  365.48  4563.3  364.04    4578  362.39  4608.8  360.14  4667.5  351.77
  4706.6  348.09  4712.2  346.58    4729   345.6  4734.5  343.75  4751.3  342.92
  4773.7  339.66  4801.6  337.91  4813.9  336.27  4829.4  334.68  4832.1  334.18
  4835.4  334.68    5136  334.68  5154.1  334.68  5173.3  337.19  5183.5  336.92
  5224.5  339.99  5255.2  343.59  5284.7  345.92  5289.8  347.16  5306.5  349.45
  5338.5  352.39  5347.4  354.14  5376.9  356.33  5398.7  359.94  5449.9  364.33
#Mann= 6 ,-1 , 0
  4541.7     .12       0  4563.3     .16       0  4813.9     .05       0
  4829.4    .033       0  4835.4     .05       0    5136     .16       0
Bank Sta=4829.4,4835.4
XS Rating Curve= 0 ,0
Exp/Cntr=0.3,0.1

Type RM Length L Ch R = 1 ,9838    ,493,493,493
BEGIN DESCRIPTION:
UNT 119 IN UKCR 19.0
END DESCRIPTION:
XS GIS Cut Line= 3
      3658099.64     10570060.17      3658549.61     10569810.19
      3659149.59     10569860.19
#Sta/Elev= 30
  4456.1  354.21  4464.1  353.55  4469.8   352.1  4491.5  350.89  4523.6  347.17
    4551  345.53    4559  345.64  4572.7  343.76  4581.9   343.7  4616.2  341.04
  4628.6  340.82  4648.2  338.37    4670  337.11  4675.7  336.02  4691.7  335.91
  4704.7  334.68  4707.5  334.18  4710.7  334.68  4738.1  334.68  5183.6  334.79
    5302  342.76  5332.1  345.35  5342.1  346.77  5352.2  347.02  5389.8  351.43
  5412.4  352.69  5462.5  357.62  5482.6  358.19  5522.7  361.11  5572.9  363.62
#Mann= 6 ,-1 , 0
  4456.1     .16       0  4628.6     .12       0  4704.7    .033       0
  4710.7     .12       0  4738.1     .05       0  5183.6     .16       0
Bank Sta=4704.7,4710.7
XS Rating Curve= 0 ,0
Exp/Cntr=0.3,0.1

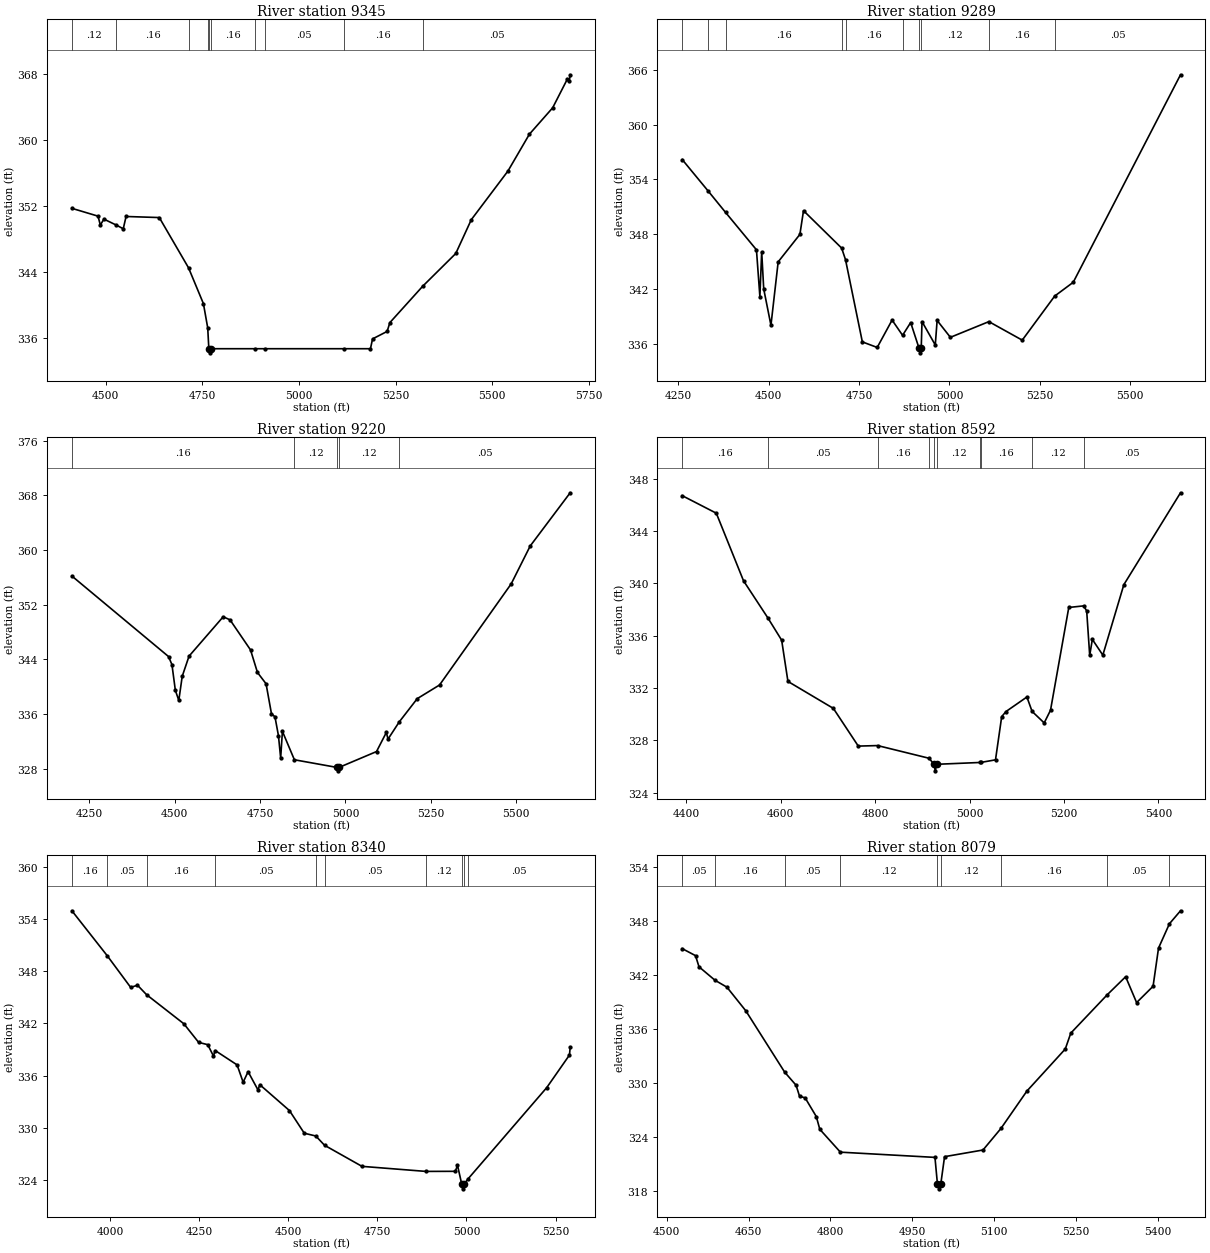
Type RM Length L Ch R = 1 ,9345    ,56,56,56
BEGIN DESCRIPTION:
UNT 119 IN UKCR 18.0
END DESCRIPTION:
XS GIS Cut Line= 4
      3657998.12      10570248.3      3658182.56     10570367.65
       3658725.1     10570237.44      3659234.83      10570204.9
#Sta/Elev= 30
  4412.8  351.72  4480.4  350.77  4486.3  349.69  4495.6  350.41  4527.9  349.68
  4545.6  349.24  4552.9  350.73  4638.8   350.6  4714.4   344.5  4752.9  340.15
    4764  337.21  4766.9  334.68  4769.7  334.18  4772.9  334.68    4887  334.68
  4911.6  334.68  5115.1  334.68  5184.8  334.68  5190.2  335.87  5227.9  336.78
    5235  337.85    5320  342.27  5405.4  346.24  5445.5  350.34  5540.2  356.24
  5595.8  360.72  5655.9  363.92  5693.8   367.4  5698.8  367.12  5701.2  367.93
#Mann= 10 ,-1 , 0
  4412.8     .12       0  4527.9     .16       0  4714.4     .12       0
    4764     .16       0  4766.9    .033       0  4772.9     .16       0
    4887     .12       0  4911.6     .05       0  5115.1     .16       0
    5320     .05       0
Bank Sta=4766.9,4772.9
XS Rating Curve= 0 ,0
Exp/Cntr=0.3,0.1

Type RM Length L Ch R = 1 ,9289    ,69,69,69
BEGIN DESCRIPTION:
UNT 119 IN UKCR 17.0
END DESCRIPTION:
XS GIS Cut Line= 4
      3657824.48     10570393.42      3658228.14     10570415.12
      3658783.69     10570280.57      3659185.96     10570258.94
#Sta/Elev= 30
  4260.5  356.17  4331.7  352.75  4380.6  350.37  4465.9  346.28  4475.4  341.15
  4480.4  346.07    4486  341.99    4506  338.01    4526  344.96  4586.1  347.97
  4596.1  350.57  4701.6  346.47  4712.3   345.2  4758.9  336.19    4800  335.58
  4841.2  338.58  4870.2  336.91  4892.6  338.31  4915.8  335.49  4918.6  334.99
  4921.8  335.49    4924  338.41  4960.7  335.85  4965.8  338.54  5002.5  336.69
    5109  338.41  5201.3  336.38  5291.1  341.21  5342.4  342.72  5639.2  365.46
#Mann= 10 ,-1 , 0
  4260.5     .16       0  4331.7     .12       0  4380.6     .16       0
  4701.6     .12       0  4712.3     .16       0  4870.2     .12       0
  4915.8     .07       0  4921.8     .12       0    5109     .16       0
  5291.1     .05       0
Bank Sta=4915.8,4921.8
XS Rating Curve= 0 ,0
Exp/Cntr=0.3,0.1

Type RM Length L Ch R = 1 ,9220    ,628,628,628
BEGIN DESCRIPTION:
Mapping XS e63083b5
END DESCRIPTION:
XS GIS Cut Line= 4
      3657776.72     10570436.82       3658310.6     10570462.86
      3659044.11     10570293.59      3659216.15     10570310.79
#Sta/Elev= 30
  4198.5   356.2  4481.7  344.42  4491.7  343.24  4501.7  339.47  4511.8     338
  4521.8  341.53  4541.8  344.48  4641.9  350.24  4661.9  349.79    4722  345.39
  4742.3  342.09  4767.5  340.44  4783.3  336.06  4793.6   335.6  4803.8  332.85
  4810.3  329.56  4815.4  333.48  4850.5  329.32  4975.3   328.2  4978.1   327.7
  4981.3   328.2  5091.2  330.52  5119.9  333.31    5125  332.35  5157.8  334.86
  5210.5  338.26  5275.9  340.26  5485.8  355.05  5541.6   360.6  5658.7  368.38
#Mann= 5 ,-1 , 0
  4198.5     .16       0  4850.5     .12       0  4975.3     .07       0
  4981.3     .12       0  5157.8     .05       0
Bank Sta=4975.3,4981.3
XS Rating Curve= 0 ,0
Exp/Cntr=0.3,0.1

Type RM Length L Ch R = 1 ,8592    ,252,252,252
BEGIN DESCRIPTION:
UNT 119 IN UKCR 16.0
END DESCRIPTION:
XS GIS Cut Line= 3
      3658227.28     10570612.19      3658361.82     10570824.84
      3659076.25     10571192.88
#Sta/Elev= 30
  4391.4   346.7  4463.6  345.36  4521.2   340.2    4573  337.35    4602  335.66
  4615.3  332.51  4711.5  330.45  4764.3  327.57  4805.2  327.61  4914.3  326.64
  4924.5  326.18  4927.3  325.68  4930.5  326.18  5022.7  326.32  5023.4  326.32
  5054.9  326.52    5068  329.82  5077.1  330.21  5121.4  331.32  5132.4  330.22
    5158  329.34  5171.4  330.31  5210.1  338.16  5241.5  338.28    5248   337.9
  5254.4   334.5    5260  335.72  5282.2  334.52  5326.7   339.9  5446.7  346.92
#Mann= 10 ,-1 , 0
  4391.4     .16       0    4573     .05       0  4805.2     .16       0
  4914.3     .12       0  4924.5     .07       0  4930.5     .12       0
  5022.7     .05       0  5023.4     .16       0  5132.4     .12       0
  5241.5     .05       0
Bank Sta=4924.5,4930.5
XS Rating Curve= 0 ,0
Exp/Cntr=0.3,0.1

Type RM Length L Ch R = 1 ,8340    ,261,261,261
BEGIN DESCRIPTION:
Mapping XS d4072851
END DESCRIPTION:
XS GIS Cut Line= 4
      3657719.49     10570820.51      3658374.84     10570981.09
      3658808.86     10571267.55      3658964.84     10571397.53
#Sta/Elev= 30
  3893.2  354.93  3992.4  349.77  4058.1  346.14  4077.2  346.39  4102.8   345.3
  4207.2  341.97  4248.8  339.83  4274.3  339.57  4290.4  338.26    4295   338.9
  4356.6  337.25  4373.6  335.26  4387.5  336.47  4415.2  334.38  4420.3  334.98
  4503.5  332.01  4545.1  329.41  4577.5  329.09  4601.9  328.03  4706.9  325.61
  4886.3  325.03  4968.9  325.04  4974.9  325.74    4987  323.53  4989.7  323.03
    4993  323.53  5004.9  324.19  5225.2  334.64    5289  338.38    5291  339.27
#Mann= 10 ,-1 , 0
  3893.2     .16       0  3992.4     .05       0  4102.8     .16       0
    4295     .05       0  4577.5     .16       0  4601.9     .05       0
  4886.3     .12       0    4987     .07       0    4993     .12       0
  5004.9     .05       0
Bank Sta=4987,4993
XS Rating Curve= 0 ,0
Exp/Cntr=0.3,0.1

Type RM Length L Ch R = 1 ,8079    ,492,492,492
BEGIN DESCRIPTION:
UNT 119 IN UKCR 15.0
END DESCRIPTION:
XS GIS Cut Line= 3
      3658199.58      10571560.2      3658649.61     10571460.19
      3659099.63     10571410.19
#Sta/Elev= 30
  4528.2  344.91  4552.6  344.13    4559  342.89  4588.3   341.4  4610.2  340.63
  4644.8  338.01  4716.1   331.2    4737  329.75  4743.4  328.52  4753.6  328.35
  4774.1  326.27  4780.5  324.86  4818.3  322.32  4991.7  321.74  4996.3  318.75
    4999  318.25  5002.3  318.75  5009.3  321.82  5079.8  322.56  5112.7  324.95
  5160.3   329.1  5230.7  333.77  5240.8  335.53  5307.8   339.8  5341.4  341.79
  5361.5  338.92  5391.7  340.73  5401.7  344.97  5421.7  347.67    5442  349.11
#Mann= 9 ,-1 , 0
  4528.2     .05       0  4588.3     .16       0  4716.1     .05       0
  4818.3     .12       0  4996.3     .07       0  5002.3     .12       0
  5112.7     .16       0  5307.8     .05       0  5421.7     .08       0
Bank Sta=4996.3,5002.3
XS Rating Curve= 0 ,0
Exp/Cntr=0.3,0.1

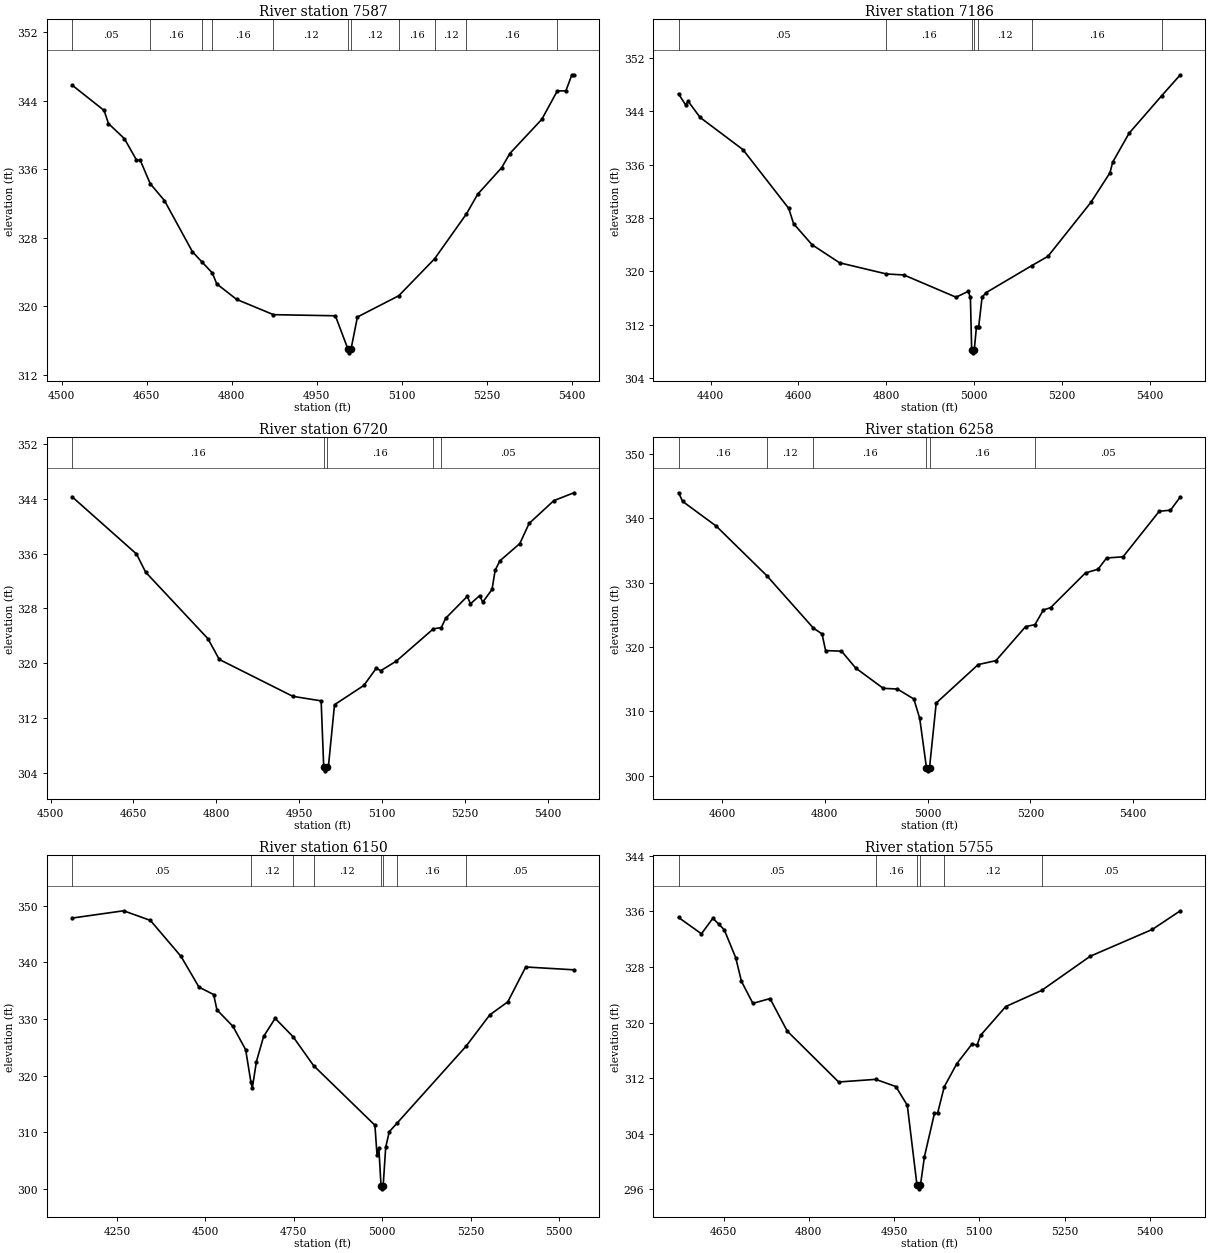
Type RM Length L Ch R = 1 ,7587    ,401,401,401
BEGIN DESCRIPTION:
UNT 119 IN UKCR 14.0
END DESCRIPTION:
XS GIS Cut Line= 3
       3658199.6     10571610.18      3658549.61     10571910.19
      3658849.58     10572210.16
#Sta/Elev= 30
  4518.3   345.8  4574.8  342.84  4582.5  341.31  4610.5  339.56  4631.9  337.07
  4638.5  337.05    4656  334.32  4681.3  332.33  4730.7  326.36  4747.5  325.17
  4765.8  323.89  4773.5  322.62  4808.6  320.81  4873.6  319.03  4982.8   318.9
  5004.6  315.08  5007.3  314.58  5010.6  315.08  5021.7  318.76  5094.7  321.24
  5157.9  325.55  5214.1  330.79  5233.8  333.07  5276.3  336.18  5290.4  337.81
    5347  341.81  5374.3  345.12  5389.4  345.12    5400     347  5403.5     347
#Mann= 11 ,-1 , 0
  4518.3     .05       0    4656     .16       0  4747.5     .05       0
  4765.8     .16       0  4873.6     .12       0  5004.6     .07       0
  5010.6     .12       0  5094.7     .16       0  5157.9     .12       0
  5214.1     .16       0  5374.3     .05       0
Bank Sta=5004.6,5010.6
XS Rating Curve= 0 ,0
Exp/Cntr=0.3,0.1

Type RM Length L Ch R = 1 ,7186    ,466,466,466
BEGIN DESCRIPTION:
UNT 119 IN UKCR 13.0
END DESCRIPTION:
XS GIS Cut Line= 3
      3658149.61     10571610.18      3658349.61     10572260.19
      3658799.65      10572360.2
#Sta/Elev= 30
  4327.3  346.61  4343.7  344.94  4348.9  345.53  4376.4  343.08  4473.8  338.25
  4577.8  329.44  4588.9  327.15  4630.7  323.99  4693.5  321.27  4799.7   319.6
    4840  319.44  4958.3  316.11  4985.8  316.97    4991  316.09  4993.9  308.26
  4996.7  307.76  4999.9  308.26  5004.8   311.7  5007.7   311.7  5009.9   311.7
  5017.6  316.11  5026.6  316.79  5130.7  320.85  5167.4  322.24  5264.8  330.32
  5308.3  334.76  5314.7  336.39  5351.8   340.7  5426.5  346.37  5468.4  349.48
#Mann= 7 ,-1 , 0
  4327.3     .05       0  4799.7     .16       0  4993.9     .07       0
  4999.9     .16       0  5007.7     .12       0  5130.7     .16       0
  5426.5     .05       0
Bank Sta=4993.9,4999.9
XS Rating Curve= 0 ,0
Exp/Cntr=0.3,0.1

Type RM Length L Ch R = 1 ,6720    ,462,462,462
BEGIN DESCRIPTION:
UNT 119 IN UKCR 12.0
END DESCRIPTION:
XS GIS Cut Line= 3
      3657699.57     10572560.18      3658149.61     10572660.19
      3658549.58     10572860.17
#Sta/Elev= 30
  4538.9   344.3  4655.5  335.94  4672.1  333.28  4784.8  323.57  4805.3  320.54
  4938.5  315.15  4989.7  314.49  4994.4  304.77  4997.1  304.27  5000.4  304.77
  5002.7  304.77  5013.9  313.93    5067  316.74  5089.4  319.25  5097.7   318.9
  5125.7  320.29  5192.7     325  5207.2   325.2  5215.1  326.55  5254.3  329.76
  5259.9  328.66  5276.6  329.86  5282.2  328.91    5299  330.76  5304.6  333.55
    5313  334.92  5349.3  337.47  5366.1   340.4  5410.8  343.73  5447.1  344.88
#Mann= 5 ,-1 , 0
  4538.9     .16       0  4994.4     .07       0  5000.4     .16       0
  5192.7     .12       0  5207.2     .05       0
Bank Sta=4994.4,5000.4
XS Rating Curve= 0 ,0
Exp/Cntr=0.3,0.1

Type RM Length L Ch R = 1 ,6258    ,108,108,108
BEGIN DESCRIPTION:
UNT 119 IN UKCR 11.0
END DESCRIPTION:
XS GIS Cut Line= 3
      3657599.59     10572860.18      3658049.61     10573110.19
      3658499.63     10573010.18
#Sta/Elev= 30
  4515.7  343.98  4523.7  342.64  4588.9  338.81  4687.1  331.12  4777.8  322.97
  4794.8  322.05  4801.7  319.46  4832.6  319.38  4860.1  316.76  4913.8   313.6
  4941.3  313.49  4973.3  311.94  4984.7  308.94  4997.8  301.28  5000.5  300.78
  5003.8  301.28  5016.8  311.32  5098.4  317.29  5132.9   317.9  5190.6  323.19
  5208.8  323.49  5225.1  325.77  5239.2  326.13  5307.1  331.53  5331.4   332.1
  5348.1  333.85  5380.1  334.03  5450.5  341.11  5472.3  341.27  5491.5  343.34
#Mann= 6 ,-1 , 0
  4515.7     .16       0  4687.1     .12       0  4777.8     .16       0
  4997.8     .07       0  5003.8     .16       0  5208.8     .05       0
Bank Sta=4997.8,5003.8
XS Rating Curve= 0 ,0
Exp/Cntr=0.3,0.1

Type RM Length L Ch R = 1 ,6150    ,395,395,395
BEGIN DESCRIPTION:
Mapping XS a6219cf8
END DESCRIPTION:
XS GIS Cut Line= 2
      3657116.17     10573343.07      3658513.69     10573100.02
#Sta/Elev= 30
  4123.2  347.82  4268.8  349.11  4344.6  347.41  4431.2  341.06  4481.9  335.64
  4523.5  334.32  4532.7  331.62    4578  328.71  4613.9  324.59  4628.6  318.93
  4632.6  317.78  4644.3  322.48  4664.6  326.92  4697.3  330.12    4748  326.88
  4805.8  321.79  4979.3  311.26  4985.3  305.97  4990.4  307.27  4996.6  300.53
  4999.4  300.03  5002.6  300.53  5009.8  307.37  5019.9  310.11  5042.1  311.64
  5236.8  325.19  5304.1  330.74  5354.9  333.03  5405.6  339.19  5541.7  338.69
#Mann= 8 ,-1 , 0
  4123.2     .05       0  4628.6     .12       0    4748     .16       0
  4805.8     .12       0  4996.6     .07       0  5002.6     .12       0
  5042.1     .16       0  5236.8     .05       0
Bank Sta=4996.6,5002.6
XS Rating Curve= 0 ,0
Exp/Cntr=0.3,0.1

Type RM Length L Ch R = 1 ,5755    ,411,411,411
BEGIN DESCRIPTION:
UNT 119 IN UKCR 10.0
END DESCRIPTION:
XS GIS Cut Line= 3
      3658049.61      10573960.2      3658099.61     10573510.19
      3658349.61     10573160.18
#Sta/Elev= 30
  4570.7  335.12    4611  332.77  4631.1     335  4641.1  334.19  4651.2  333.34
  4671.3  329.33  4681.4  325.93  4701.5  322.76  4731.7  323.45  4761.9  318.78
  4852.4  311.45  4917.5  311.83    4953   310.8  4973.2   308.1  4990.3  296.58
    4993  296.08  4996.3  296.58  5003.4  300.72    5021  306.95  5026.5  306.95
  5038.2  310.76  5060.3  314.08  5087.4  316.95    5096  316.74  5102.1  318.16
  5146.4   322.3  5209.5  324.62  5295.1  329.54  5404.4   333.4  5453.6  336.08
#Mann= 6 ,-1 , 0
  4570.7     .05       0  4917.5     .16       0  4990.3     .07       0
  4996.3     .16       0  5038.2     .12       0  5209.5     .05       0
Bank Sta=4990.3,4996.3
XS Rating Curve= 0 ,0
Exp/Cntr=0.3,0.1

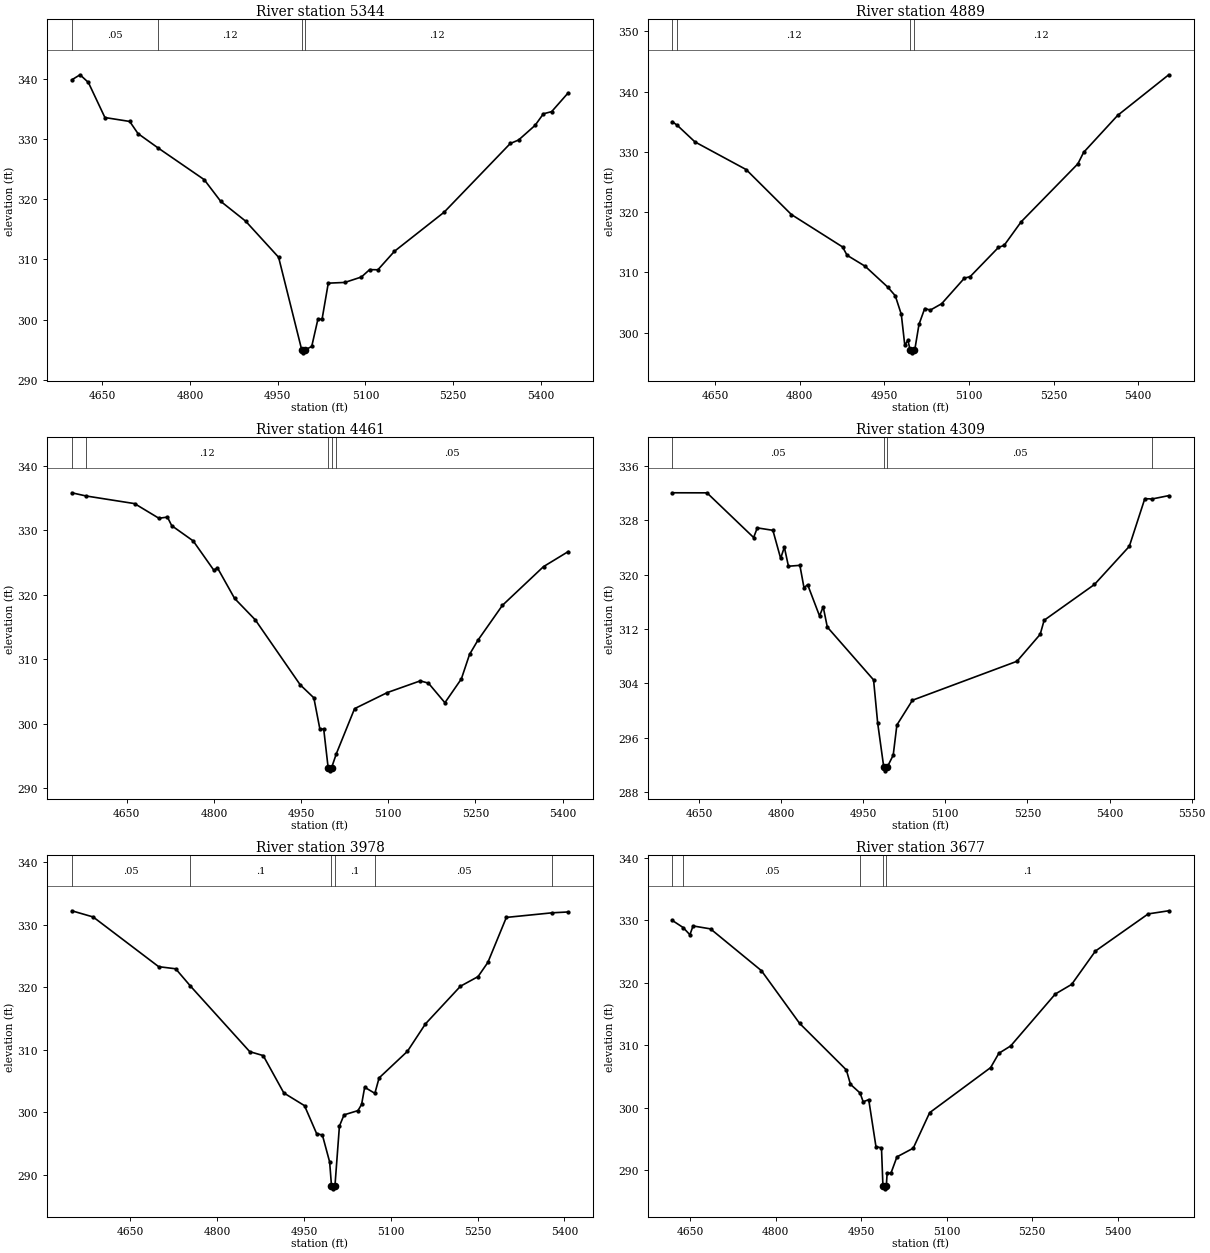
Type RM Length L Ch R = 1 ,5344    ,455,455,455
BEGIN DESCRIPTION:
UNT 119 IN UKCR 9.0
END DESCRIPTION:
XS GIS Cut Line= 3
      3658149.62     10574010.18      3658449.61     10573710.19
       3658749.6      10573410.2
#Sta/Elev= 30
  4598.1  339.82  4612.2  340.66  4626.4  339.39  4654.7  333.56  4697.1  332.91
  4711.2   330.9  4745.6  328.51  4824.4  323.25  4852.6  319.65  4895.1  316.37
  4951.6  310.36  4991.1  294.99  4993.8  294.49  4997.1  294.99  5008.2  295.55
  5018.8  300.08  5025.9  300.08  5036.5  306.06  5064.8  306.18  5093.1  307.08
  5107.2  308.31  5121.3  308.28  5149.6  311.35  5234.5  317.84  5347.6  329.25
  5361.8  329.83    5390  332.26  5404.2  334.18  5418.3  334.54  5446.6  337.66
#Mann= 4 ,-1 , 0
  4598.1     .05       0  4745.6     .12       0  4991.1     .07       0
  4997.1     .12       0
Bank Sta=4991.1,4997.1
XS Rating Curve= 0 ,0
Exp/Cntr=0.3,0.1

Type RM Length L Ch R = 1 ,4889    ,428,428,428
BEGIN DESCRIPTION:
UNT 119 IN UKCR 8.0
END DESCRIPTION:
XS GIS Cut Line= 3
      3658649.59     10574260.23      3658799.61     10573860.19
      3658849.61      10573410.2
#Sta/Elev= 30
  4574.2     335  4583.3  334.37  4614.3  331.65  4705.1  327.06  4785.2  319.61
    4876  314.23    4884  312.85    4916  311.03  4956.1  307.57  4969.4  306.14
  4980.1  303.06  4986.3  297.92  4991.7  298.76  4995.8  297.17  4998.5  296.67
  5001.8  297.17    5004  297.17  5011.5   301.4  5021.6  304.02  5031.6  303.76
  5051.7  304.82    5092  309.06  5102.1   309.3  5152.4  314.16  5162.4  314.49
  5192.6   318.4  5293.2  328.02  5303.3  329.91  5363.7  336.05  5454.2  342.78
#Mann= 4 ,-1 , 0
  4574.2     .05       0  4583.3     .12       0  4995.8     .07       0
  5001.8     .12       0
Bank Sta=4995.8,5001.8
XS Rating Curve= 0 ,0
Exp/Cntr=0.3,0.1

Type RM Length L Ch R = 1 ,4461    ,152,152,152
BEGIN DESCRIPTION:
UNT 119 IN UKCR 7.0
END DESCRIPTION:
XS GIS Cut Line= 3
      3658799.63     10574310.17      3659149.61     10574060.19
      3659449.64     10573760.16
#Sta/Elev= 30
  4555.3  335.82  4579.5  335.33  4663.4  334.14  4705.2  331.87  4719.9  332.05
  4727.3  330.72  4764.2  328.36  4799.8  323.81    4806  324.18  4835.5  319.44
  4871.1  316.12  4948.5  306.04  4971.9  304.03  4982.3  299.19  4988.9  299.19
  4996.5  293.21  4999.3  292.71  5002.5  293.21  5010.7  295.38    5042  302.35
  5098.5  304.85  5155.1  306.66  5169.2   306.3  5197.5  303.27  5225.8  306.96
  5239.9  310.76  5254.1  312.93  5296.5  318.37  5367.2  324.37  5409.7   326.7
#Mann= 5 ,-1 , 0
  4555.3     .05       0  4579.5     .12       0  4996.5     .07       0
  5002.5     .12       0  5010.7     .05       0
Bank Sta=4996.5,5002.5
XS Rating Curve= 0 ,0
Exp/Cntr=0.3,0.1

Type RM Length L Ch R = 1 ,4309    ,331,331,331
BEGIN DESCRIPTION:
Mapping XS ec4836e1
END DESCRIPTION:
XS GIS Cut Line= 3
      3659022.67     10574422.59      3659338.65     10574068.41
      3659640.74     10573759.38
#Sta/Elev= 30
  4601.3  332.07  4664.6  332.06  4749.8  325.48  4756.5   326.9    4785  326.54
  4799.2   322.4  4805.9  324.07  4813.4  321.25  4834.3  321.38  4841.8  318.09
  4848.5  318.53  4870.2  313.93  4876.9  315.27  4884.4  312.29  4968.9  304.51
  4976.4  298.16  4987.6  291.61  4990.4  291.11  4993.6  291.61  5004.8  293.42
  5011.5  297.86  5039.9  301.51  5230.9  307.25  5273.3  311.22  5280.5  313.29
  5372.4  318.56  5436.1  324.18  5464.4   331.2  5477.9  331.16  5508.1  331.65
#Mann= 4 ,-1 , 0
  4601.3     .05       0  4987.6     .03       0  4993.6     .05       0
  5477.9      .1       0
Bank Sta=4987.6,4993.6
XS Rating Curve= 0 ,0
Exp/Cntr=0.3,0.1

Type RM Length L Ch R = 1 ,3978    ,301,301,301
BEGIN DESCRIPTION:
UNT 119 IN UKCR 6.0
END DESCRIPTION:
XS GIS Cut Line= 3
      3659249.59      10574410.2      3659599.61     10574160.19
      3659749.59     10573760.23
#Sta/Elev= 30
  4549.1   332.2    4586  331.21  4699.1  323.27  4728.5  322.93  4754.1  320.16
  4856.4  309.69  4879.7  309.06  4915.3  303.09    4951  301.06  4971.9   296.6
  4981.9  296.36  4994.4  292.07  4997.6  288.27  5000.4  287.77  5003.6  288.27
  5011.3   297.8  5019.3  299.59  5043.3  300.27  5049.6  301.26  5054.9     304
  5072.5  303.03  5079.8  305.49  5128.8  309.75  5159.9  314.13  5220.4  320.15
  5250.7  321.68  5267.6  323.94  5299.6  331.14  5379.2  331.88  5406.4  332.01
#Mann= 6 ,-1 , 0
  4549.1     .05       0  4754.1      .1       0  4997.6     .07       0
  5003.6      .1       0  5072.5     .05       0  5379.2      .1       0
Bank Sta=4997.6,5003.6
XS Rating Curve= 0 ,0
Exp/Cntr=0.3,0.1

Type RM Length L Ch R = 1 ,3677    ,733,733,733
BEGIN DESCRIPTION:
UNT 119 IN UKCR 5.0
END DESCRIPTION:
XS GIS Cut Line= 3
      3659449.61     10574510.19      3659789.77     10574341.33
      3660099.63     10573960.16
#Sta/Elev= 30
  4618.6  329.98  4637.5  328.85  4649.4  327.69    4655   329.1  4685.6  328.63
  4774.9  321.94  4841.9   313.5  4923.9  306.04  4931.2  303.73    4948  302.34
  4953.5  300.93  4963.2  301.28  4975.9  293.75  4985.6  293.55  4988.1  287.49
  4990.9  286.99  4994.1  287.49  4995.5   289.5  5002.2   289.5  5012.7  292.11
  5041.3   293.5  5070.1  299.19  5177.1  306.41  5191.5   308.7  5212.3  309.88
  5290.6   318.2  5319.3  319.74    5361  325.08  5453.6  331.03  5489.6  331.53
#Mann= 5 ,-1 , 0
  4618.6      .1       0  4637.5     .05       0    4948      .1       0
  4988.1     .07       0  4994.1      .1       0
Bank Sta=4988.1,4994.1
XS Rating Curve= 0 ,0
Exp/Cntr=0.3,0.1

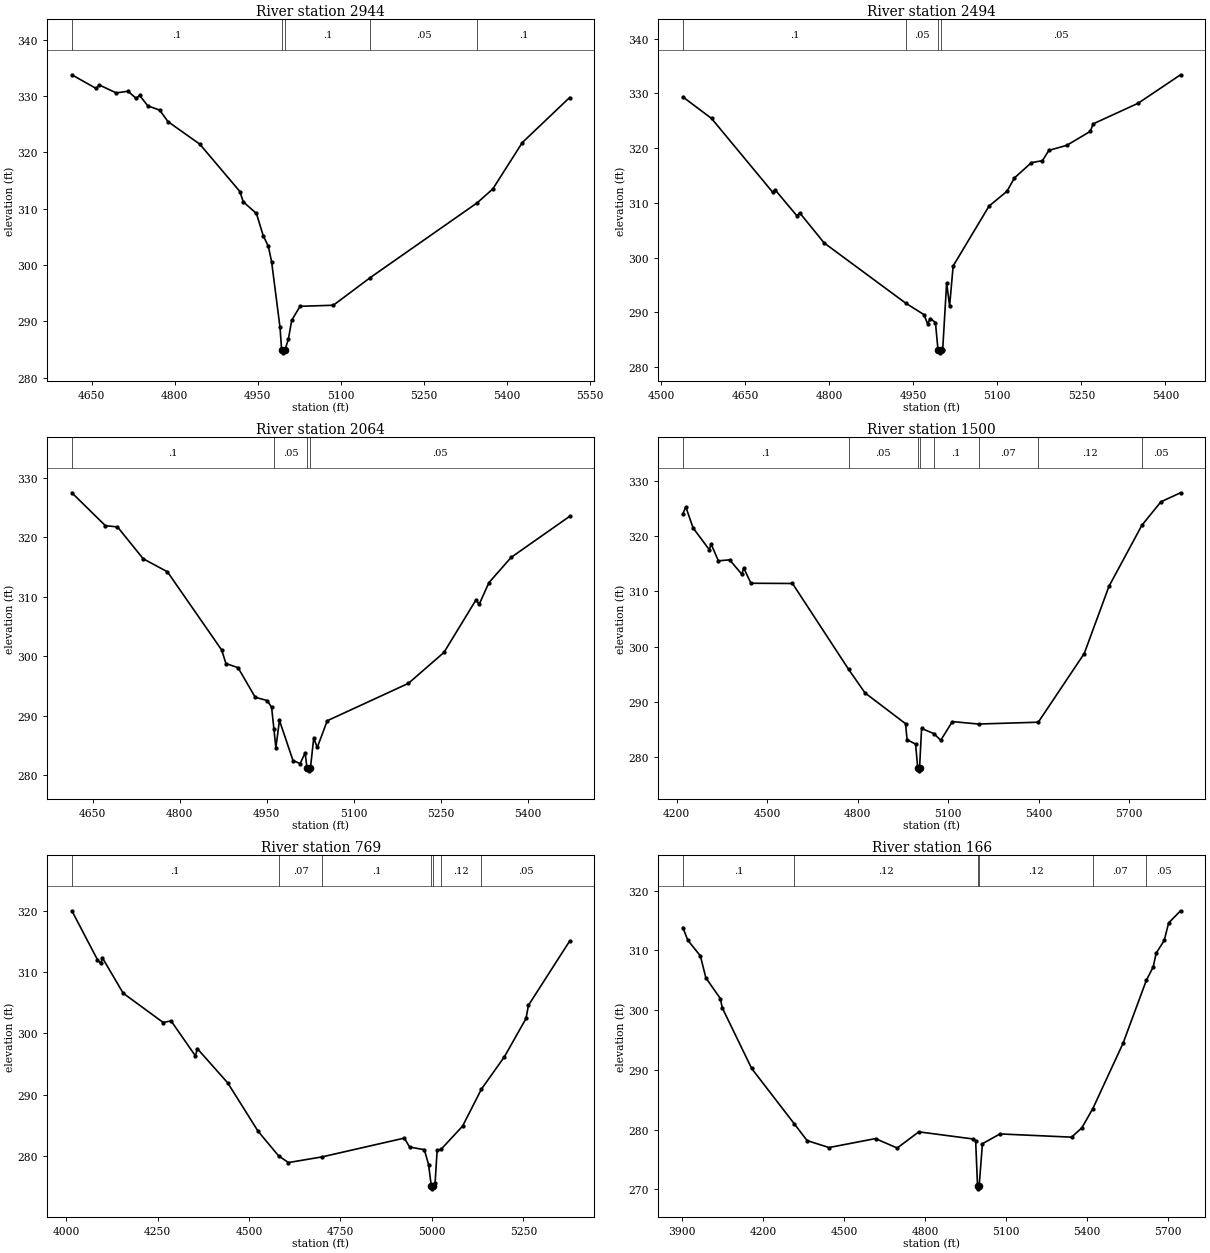
Type RM Length L Ch R = 1 ,2944    ,450,450,450
BEGIN DESCRIPTION:
UNT 119 IN UKCR 4.0
END DESCRIPTION:
XS GIS Cut Line= 3
      3660549.63     10574910.21       3660310.6     10574540.99
      3660149.62     10574110.23
#Sta/Elev= 30
  4613.9  333.78  4657.8  331.35  4663.7  331.96  4694.1  330.56  4715.2  330.86
  4730.3  329.58  4736.3  330.12  4751.4  328.25  4772.5  327.52  4787.7  325.46
  4845.1  321.47  4917.6  313.06  4923.7  311.23  4947.5  309.16  4959.9   305.2
  4969.1  303.33    4975  300.57  4990.2  288.92  4993.1  284.92  4995.9  284.42
  4999.1  284.92  5005.3  286.84  5011.3  290.19  5026.4  292.68  5086.6  292.87
  5153.4  297.78  5346.6  311.05  5374.9  313.52  5428.2  321.75  5513.6  329.73
#Mann= 5 ,-1 , 0
  4613.9      .1       0  4993.1     .07       0  4999.1      .1       0
  5153.4     .05       0  5346.6      .1       0
Bank Sta=4993.1,4999.1
XS Rating Curve= 0 ,0
Exp/Cntr=0.3,0.1

Type RM Length L Ch R = 1 ,2494    ,430,430,430
BEGIN DESCRIPTION:
UNT 119 IN UKCR 3.0
END DESCRIPTION:
XS GIS Cut Line= 3
      3660649.61     10574760.21      3660549.61     10574310.19
      3660399.61     10573910.19
#Sta/Elev= 30
  4538.8  329.34    4590  325.41  4698.9  311.96    4704  312.31  4742.4  307.62
  4747.5  308.15  4791.1  302.66    4937  291.64  4969.1  289.58  4975.5  287.93
  4980.6  288.87  4989.6  288.13  4994.2   283.1    4997   282.6  5000.2   283.1
  5002.5   283.1  5009.6  295.37  5014.9  291.18  5021.2  298.46  5085.2  309.39
  5117.3  312.11  5130.6  314.54  5160.9  317.34  5180.5  317.69    5192  319.57
  5224.1   320.5  5265.9  323.04  5271.2  324.42  5351.3  328.18    5427  333.38
#Mann= 4 ,-1 , 0
  4538.8      .1       0    4937     .05       0  4994.2     .03       0
  5000.2     .05       0
Bank Sta=4994.2,5000.2
XS Rating Curve= 0 ,0
Exp/Cntr=0.3,0.1

Type RM Length L Ch R = 1 ,2064    ,564,564,564
BEGIN DESCRIPTION:
UNT 119 IN UKCR 2.0
END DESCRIPTION:
XS GIS Cut Line= 3
      3660699.63     10574710.16      3660949.61     10574360.19
       3660799.6     10573960.17
#Sta/Elev= 30
  4614.2  327.52  4671.9  321.98  4692.8  321.77  4737.1   316.4  4778.8  314.21
  4872.2  301.04  4879.6  298.76  4900.5  298.05    4930  293.08  4950.9  292.51
  4958.3  291.36  4962.3  287.65  4965.6  284.59  4971.8  289.17  4995.1  282.42
  5007.4   281.9    5016   283.7  5019.2  281.18  5021.9  280.68  5025.2  281.18
  5030.8   286.2  5036.9  284.62  5054.1  289.12  5193.8  295.41  5255.2  300.63
  5310.4  309.49  5315.7  308.71  5332.6  312.38  5370.9  316.64  5471.5  323.54
#Mann= 4 ,-1 , 0
  4614.2      .1       0  4962.3     .05       0  5019.2     .03       0
  5025.2     .05       0
Bank Sta=5019.2,5025.2
XS Rating Curve= 0 ,0
Exp/Cntr=0.3,0.1

Type RM Length L Ch R = 1 ,1500    ,731,731,731
BEGIN DESCRIPTION:
Mapping XS f44787cd
END DESCRIPTION:
XS GIS Cut Line= 3
      3660805.36     10574818.77      3661395.67     10574584.39
      3661577.96     10573586.13
#Sta/Elev= 30
  4220.6  324.06  4230.4  325.32  4254.7   321.5  4308.7  317.53  4314.1  318.61
  4338.4  315.54  4375.8  315.72  4416.7  313.07  4422.1  314.29  4446.4  311.47
  4584.1  311.43  4769.8  295.89  4824.4  291.59  4958.9     286    4964  283.11
  4992.2  282.29  4999.3  277.95  5002.1  277.45  5005.3  277.95  5012.1  285.14
    5053  284.19  5075.5  282.99  5114.1  286.38  5200.9  285.94  5398.9  286.27
  5551.3  298.73  5633.4  310.93  5742.5     322  5805.4  326.24  5870.5  327.88
#Mann= 8 ,-1 , 0
  4220.6      .1       0  4769.8     .05       0  4999.3     .03       0
  5005.3     .05       0    5053      .1       0  5200.9     .07       0
  5398.9     .12       0  5742.5     .05       0
Bank Sta=4999.3,5005.3
XS Rating Curve= 0 ,0
Exp/Cntr=0.3,0.1

Type RM Length L Ch R = 1 ,769     ,603,603,603
BEGIN DESCRIPTION:
Mapping XS cdc61dab
END DESCRIPTION:
XS GIS Cut Line= 3
      3660840.13      10574844.8      3661577.96       10574758.
      3662142.23     10574506.25
#Sta/Elev= 30
  4015.6  319.96  4085.6  311.98  4094.2  311.37  4099.3  312.27    4156  306.52
  4265.4  301.75  4286.9  302.01  4353.5   296.3  4358.6  297.49  4441.6  291.92
  4524.7  284.03  4580.6  280.03  4607.8  278.92  4700.6  279.86  4924.6  282.91
  4939.1  281.45  4979.3  281.02    4991  278.57  4998.2  275.14    5001  274.64
  5004.2  275.14  5008.8  275.63  5014.3  280.89  5025.3   281.1  5083.9  284.86
  5135.5   290.9  5198.3  296.17  5257.4  302.41    5264  304.56  5376.4     315
#Mann= 7 ,-1 , 0
  4015.6      .1       0  4580.6     .07       0  4700.6      .1       0
  4998.2     .07       0  5004.2      .1       0  5025.3     .12       0
  5135.5     .05       0
Bank Sta=4998.2,5004.2
XS Rating Curve= 0 ,0
Exp/Cntr=0.3,0.1

Type RM Length L Ch R = 1 ,166     ,0,0,0
BEGIN DESCRIPTION:
UNT 119 IN UKCR 1.0
END DESCRIPTION:
XS GIS Cut Line= 4
       3660805.4     10574992.38      3661525.88      10575113.9
       3662098.8      10575070.5      3662202.97     10574540.96
#Sta/Elev= 30
  3901.8  313.83    3920  311.72  3966.9  309.07  3987.2   305.4    4041  301.93
    4048  300.38  4156.9  290.24  4314.3  281.01  4362.4  278.17  4443.6     277
    4616   278.5  4696.4  276.92  4776.6  279.63  4977.2  278.44  4987.2  278.17
  4994.2  270.59    4997  270.09  5000.2  270.59  5012.4  277.64  5077.5  279.28
  5342.8  278.74  5380.6  280.28  5421.6  283.52  5533.5  294.44    5620  304.99
  5645.6  307.25  5656.2  309.52  5686.3  311.67  5702.5  314.59  5746.7  316.63
#Mann= 6 ,-1 , 0
  3901.8      .1       0  4314.3     .12       0  4994.2     .07       0
  5000.2     .12       0  5421.6     .07       0    5620     .05       0
Bank Sta=4994.2,5000.2
XS Rating Curve= 0 ,0
Exp/Cntr=0.3,0.1

Chan Stop Cuts=-1
Use User Specified Reach Order=0
Composite Channel Slope=5