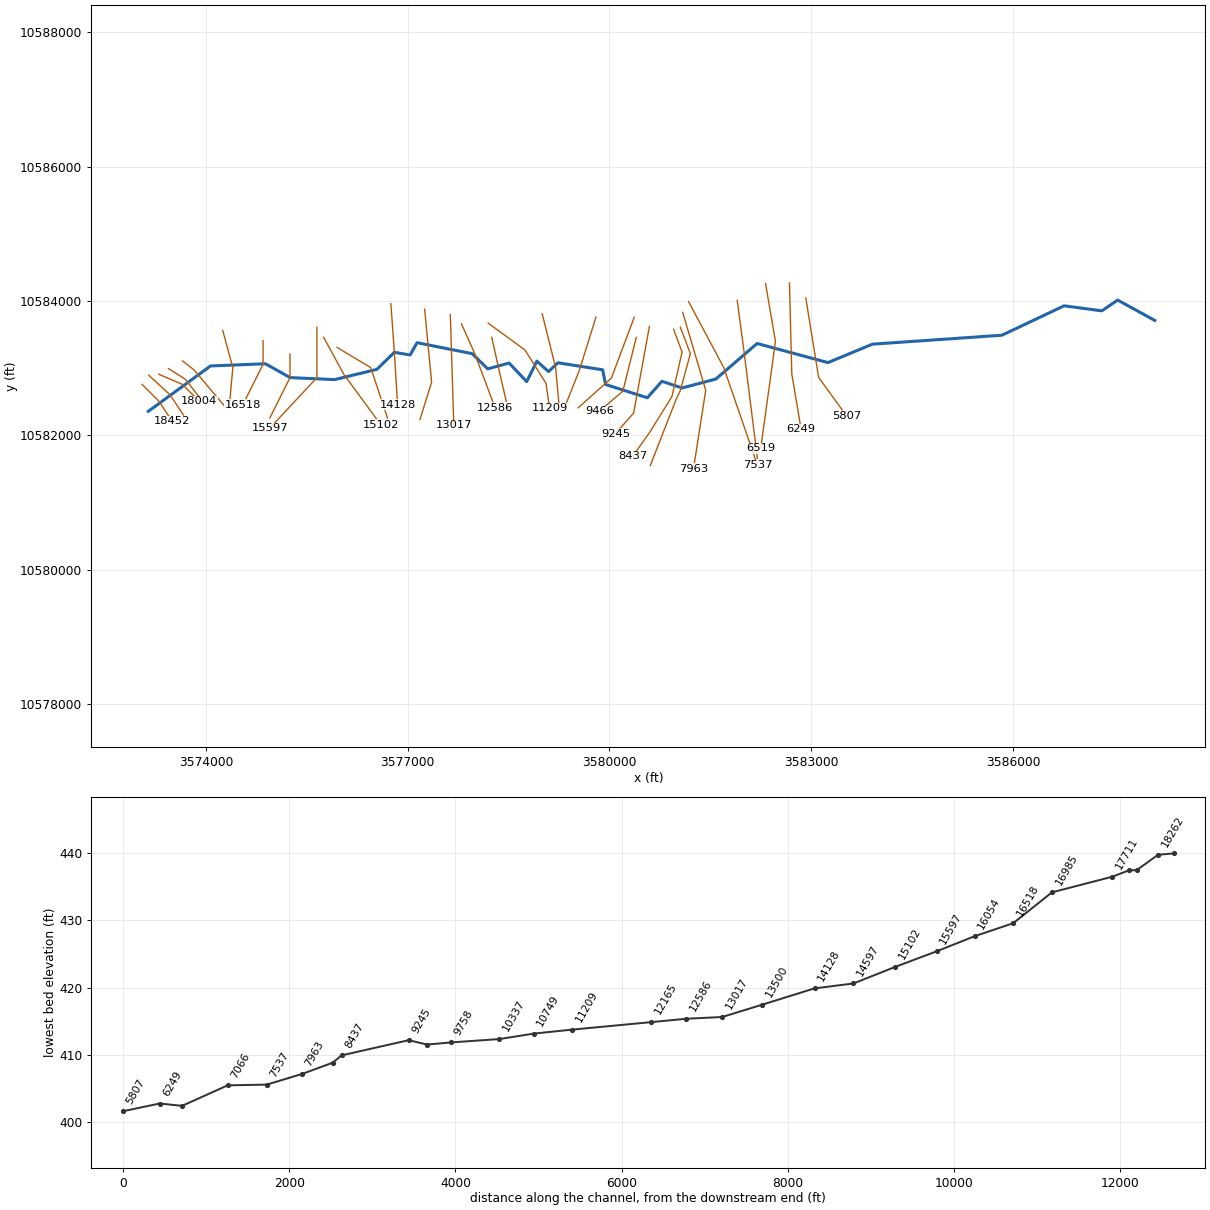
--- UNT 121 IN UKCR.prj (project) ---

Proj Title=UNT 121 IN UKCR Base Level Engineering
Current Plan=p01
Default Exp/Contr=0.3,0.1
English Units
Geom File=g01
Flow File=f01
Plan File=p01
Y Axis Title=Elevation
X Axis Title(PF)=Main Channel Distance
X Axis Title(XS)=Station
BEGIN DESCRIPTION:
UNT 121 IN UKCR
END DESCRIPTION:
DSS Export Rating Curves= 0
DSS Export Rating Curve Sorted= 0
DSS Export Volume Flow Curves= 0
DXF OffsetX= 0
DXF OffsetY= 0
DXF ScaleX= 1
DXF ScaleY= 10

--- UNT 121 IN UKCR.p01 (plan) ---

Plan Title=Multiple Run
Short Identifier=Multiple
Geom File=g01
Flow File=f01
Subcritical Flow
K Sum by GR= 0
Std Step Tol= 0.01
Critical Tol= 0.01
Num of Std Step Trials= 20
Max Error Tol= 0.3
Flow Tol Ratio= 0.001
Split Flow NTrial= 30
Split Flow Tol= 0.02
Split Flow Ratio= 0.02
Log Output Level= 0
Friction Slope Method= 1
Unsteady Friction Slope Method= 2
Unsteady Bridges Friction Slope Method= 1
Parabolic Critical Depth
Global Vel Dist=  1 , 1 , 1
Global Log Level= 0
CheckData=True
Encroach Param= -1, 0, 0, 0
BEGIN DESCRIPTION:
Multiple Run
END DESCRIPTION:

--- UNT 121 IN UKCR.f01 (steady flow) ---

Flow Title=Multiple
Program Version=4.10
Number of Profiles= 7
Profile Names=10-year,25-year,50-year,1pct_min,100-year,1pct_plu,500-year
River Rch & RM=UNT 121 IN UKCR,Reach-1         ,18452
    1227    1715    2126    1925    2603    3521    3889
River Rch & RM=UNT 121 IN UKCR,Reach-1         ,15102
    2411    3454    4349    3986    5390    7289    8258
River Rch & RM=UNT 121 IN UKCR,Reach-1         ,7963
    2534    3625    4561    4174    5645    7635    8627
River Rch & RM=UNT 121 IN UKCR,Reach-1         ,3498
    3027    4369    5529    5087    6879    9303   10626
River Rch & RM=UNT 121 IN UKCR,Reach-1         ,601
    3027    4369    5529    5087    6879    9303   10626
Boundary for River Rch & Prof#=UNT 121 IN UKCR,Reach-1         , 1
Up Type= 0
Dn Type= 3
Dn Slope=0.044
Boundary for River Rch & Prof#=UNT 121 IN UKCR,Reach-1         , 2
Up Type= 0
Dn Type= 3
Dn Slope=0.044
Boundary for River Rch & Prof#=UNT 121 IN UKCR,Reach-1         , 3
Up Type= 0
Dn Type= 3
Dn Slope=0.044
Boundary for River Rch & Prof#=UNT 121 IN UKCR,Reach-1         , 4
Up Type= 0
Dn Type= 3
Dn Slope=0.044
Boundary for River Rch & Prof#=UNT 121 IN UKCR,Reach-1         , 5
Up Type= 0
Dn Type= 3
Dn Slope=0.044
Boundary for River Rch & Prof#=UNT 121 IN UKCR,Reach-1         , 6
Up Type= 0
Dn Type= 3
Dn Slope=0.044
Boundary for River Rch & Prof#=UNT 121 IN UKCR,Reach-1         , 7
Up Type= 0
Dn Type= 3
Dn Slope=0.044
DSS Import GetInterval= 0
DSS Import GetPeak= 0
DSS Import FillOption= 0

--- UNT 121 IN UKCR.g01 (geometry) ---

Geom Title=Existing Conditions
Program Version=4.10

River Reach=UNT 121 IN UKCR ,Reach-1
Reach XY= 30
      3573142.25       10582359.      3574067.75       10583034.
      3574884.75       10583067.      3575249.75       10582861.
      3575913.75       10582831.      3576542.75       10582984.
        3576801.       10583237.        3577036.       10583197.
        3577139.       10583380.      3577958.25       10583217.
       3578189.5       10582991.      3578507.75       10583077.
      3578769.75       10582801.      3578920.75       10583106.
      3579093.75       10582950.        3579233.       10583081.
       3579898.5       10582977.        3579943.       10582758.
      3580563.25       10582561.       3580779.5       10582806.
        3581080.       10582707.      3581581.25       10582839.
       3582195.5       10583368.        3583249.       10583084.
      3583910.75       10583358.      3585835.75       10583491.
      3586760.25       10583928.      3587322.75       10583854.
        3587557.       10584014.        3588109.       10583711.

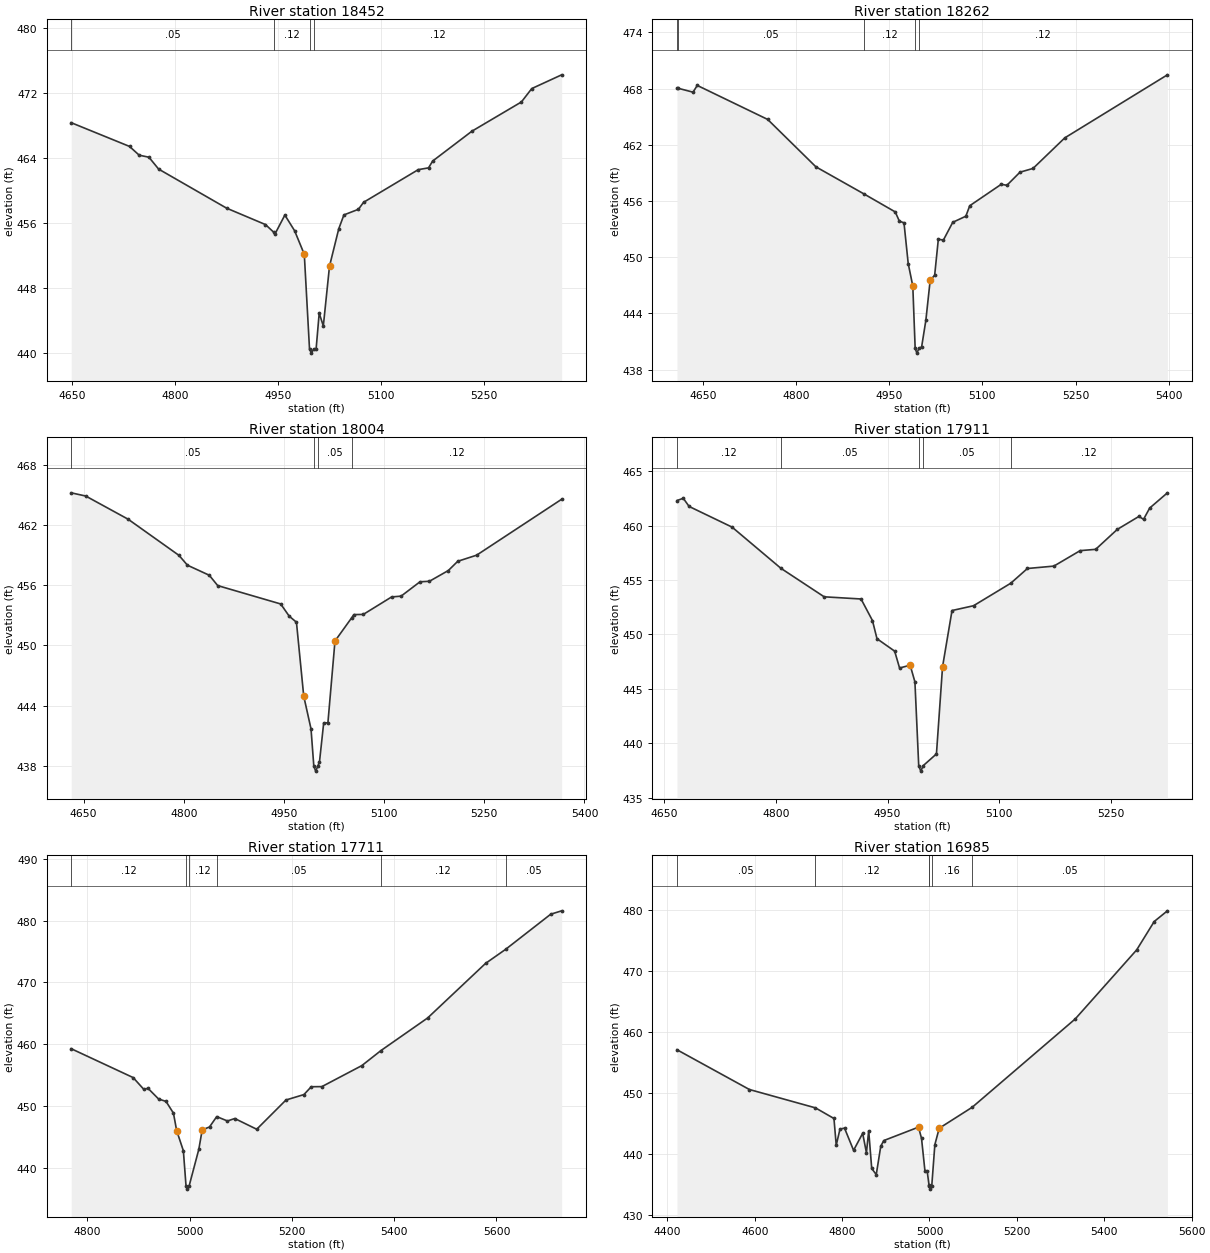
Type RM Length L Ch R = 1 ,18452   ,190,190,190
BEGIN DESCRIPTION:
UNT 121 IN UKCR 33.0
END DESCRIPTION:
XS GIS Cut Line= 3
       3573049.6      10582760.2      3573299.61     10582510.19
       3573499.6     10582210.21
#Sta/Elev= 30
  4648.9  468.33  4733.8  465.41  4747.9  464.33  4762.1  464.08  4776.2  462.62
  4875.2  457.81  4931.8  455.79    4944  454.83  4945.9  454.68    4960  456.96
  4974.2  455.03  4988.3  452.13  4995.9  440.47  4998.7  439.97  5001.9  440.47
  5005.5  440.47    5010   444.9    5016  443.31    5025  450.67  5038.5  455.28
    5046  456.98  5067.1  457.67  5074.6  458.53  5154.2  462.55  5169.2  462.77
  5175.2  463.61  5232.3  467.28  5304.4  470.88  5319.5  472.53    5363  474.22
#Mann= 4 ,-1 , 0
  4648.9     .05       0    4944     .12       0  4995.9     .07       0
  5001.9     .12       0
Bank Sta=4988.3,5025
XS Rating Curve= 0 ,0
Exp/Cntr=0.3,0.1

Type RM Length L Ch R = 1 ,18262   ,258,258,258
BEGIN DESCRIPTION:
Mapping XS 9e21970c
END DESCRIPTION:
XS GIS Cut Line= 3
      3573149.06     10582895.93      3573463.28     10582607.75
      3573664.49     10582305.08
#Sta/Elev= 30
  4608.1  468.02  4609.1  468.05    4634  467.62  4640.8  468.34  4754.2  464.71
  4831.9  459.65  4909.8  456.74  4959.6  454.84  4966.3  453.85  4973.7  453.68
  4980.5  449.33  4987.9  446.93  4991.7  440.27  4994.5  439.77  4997.7  440.27
  5002.1  440.43  5008.9  443.26  5015.9  447.56  5023.1  448.08    5029  451.92
  5037.2  451.84  5052.2  453.73  5073.3  454.38  5079.6   455.5  5130.4  457.79
  5139.4  457.68  5160.5  459.08  5181.5  459.48  5232.6  462.74  5397.9  469.47
#Mann= 5 ,-1 , 0
  4608.1     .12       0  4609.1     .05       0  4909.8     .12       0
  4991.7     .07       0  4997.7     .12       0
Bank Sta=4987.9,5015.9
XS Rating Curve= 0 ,0
Exp/Cntr=0.3,0.1

Type RM Length L Ch R = 1 ,18004   ,93,93,93
BEGIN DESCRIPTION:
UNT 121 IN UKCR 32.0
END DESCRIPTION:
XS GIS Cut Line= 3
      3573299.57     10582910.21      3573649.61     10582760.19
      3573899.62     10582510.18
#Sta/Elev= 30
  4631.4   465.2  4653.2  464.88  4716.7  462.57  4792.8  458.97  4805.5  457.99
  4838.2  456.99  4850.8  455.96  4945.1  454.13  4957.8  452.92  4968.7  452.31
  4979.6  444.95  4990.5  441.69  4994.7  437.98  4997.5  437.48  5000.7  437.98
  5003.2  438.41  5009.5  442.29  5015.8  442.29  5026.4  450.44  5051.7  452.78
  5054.7  453.07  5068.8  453.09  5111.2  454.83  5125.4  454.91  5153.7  456.34
  5167.8  456.39  5196.1  457.46  5210.2  458.38  5238.5  458.99  5365.8  464.56
#Mann= 4 ,-1 , 0
  4631.4     .05       0  4994.7     .03       0  5000.7     .05       0
  5051.7     .12       0
Bank Sta=4979.6,5026.4
XS Rating Curve= 0 ,0
Exp/Cntr=0.3,0.1

Type RM Length L Ch R = 1 ,17911   ,200,200,200
BEGIN DESCRIPTION:
Mapping XS c768a828
END DESCRIPTION:
XS GIS Cut Line= 3
      3573442.42     10582994.92      3573695.92     10582835.18
      3573915.53     10582551.59
#Sta/Elev= 30
  4667.3   462.3  4675.8  462.51  4683.6  461.76  4741.3  459.86  4806.8  456.08
  4864.9  453.46  4914.4  453.26  4929.7  451.28  4935.8  449.61  4959.5  448.47
  4966.1  446.92  4980.3  447.18  4986.7  445.65  4991.8  437.95  4994.6  437.45
  4997.8  437.95  5015.6  439.03  5023.8  447.04  5036.5   452.2  5065.4  452.64
  5115.4  454.71  5137.7  456.06  5173.2  456.28  5208.5   457.7  5229.3  457.82
  5258.3  459.65  5287.3  460.84  5293.6  460.58  5301.8  461.61  5325.6  463.01
#Mann= 5 ,-1 , 0
  4667.3     .12       0  4806.8     .05       0  4991.8     .03       0
  4997.8     .05       0  5115.4     .12       0
Bank Sta=4980.3,5023.8
XS Rating Curve= 0 ,0
Exp/Cntr=0.3,0.1

Type RM Length L Ch R = 1 ,17711   ,726,726,726
BEGIN DESCRIPTION:
UNT 121 IN UKCR 31.0
END DESCRIPTION:
XS GIS Cut Line= 3
      3573649.65     10583110.16      3573822.58     10582975.33
      3574299.58     10582410.22
#Sta/Elev= 30
  4768.6  459.25  4889.8  454.57  4910.6  452.66  4918.7  452.84  4939.5   451.1
    4954  450.71  4968.5  448.81  4974.8  445.98  4987.9  442.72  4993.1     437
  4995.8   436.5  4999.1     437  5018.1  442.95  5024.7   446.1    5039  446.57
  5053.1  448.25  5074.1  447.54  5088.4  447.94  5131.3   446.2  5188.5  450.94
  5223.6  451.82  5237.9  453.09  5258.7  453.11  5336.7  456.51  5374.3  458.96
  5465.4  464.23  5578.6  473.07  5617.7  475.34    5706  481.04  5727.4  481.59
#Mann= 6 ,-1 , 0
  4768.6     .12       0  4993.1     .07       0  4999.1     .12       0
  5053.1     .05       0  5374.3     .12       0  5617.7     .05       0
Bank Sta=4974.8,5024.7
XS Rating Curve= 0 ,0
Exp/Cntr=0.3,0.1

Type RM Length L Ch R = 1 ,16985   ,467,467,467
BEGIN DESCRIPTION:
UNT 121 IN UKCR 30.0
END DESCRIPTION:
XS GIS Cut Line= 3
      3574249.61     10583560.19      3574399.61     10583010.19
       3574349.6     10582460.14
#Sta/Elev= 30
  4422.1  457.03  4587.9  450.51  4739.1   447.5  4781.4  445.76  4786.6  441.38
  4795.2  444.02  4805.6  444.18  4826.3  440.54  4847.1  443.33  4855.7  440.15
  4860.9  443.75  4867.8  437.57  4878.2  436.56  4888.5  441.21  4895.4  442.14
  4974.9  444.34  4981.8   442.5  4989.6  437.18  4994.7  437.18  4998.9  434.85
  4999.2  434.68    5002  434.18  5005.2  434.68  5012.3  441.47  5022.3  444.16
  5097.8   447.6  5333.6  462.08  5474.2   473.4  5514.3  478.05  5544.5   479.8
#Mann= 6 ,-1 , 0
  4422.1     .05       0  4739.1     .12       0  4998.9     .16       0
  4999.2     .07       0  5005.2     .16       0  5097.8     .05       0
Bank Sta=4974.9,5022.3
XS Rating Curve= 0 ,0
Exp/Cntr=0.3,0.1

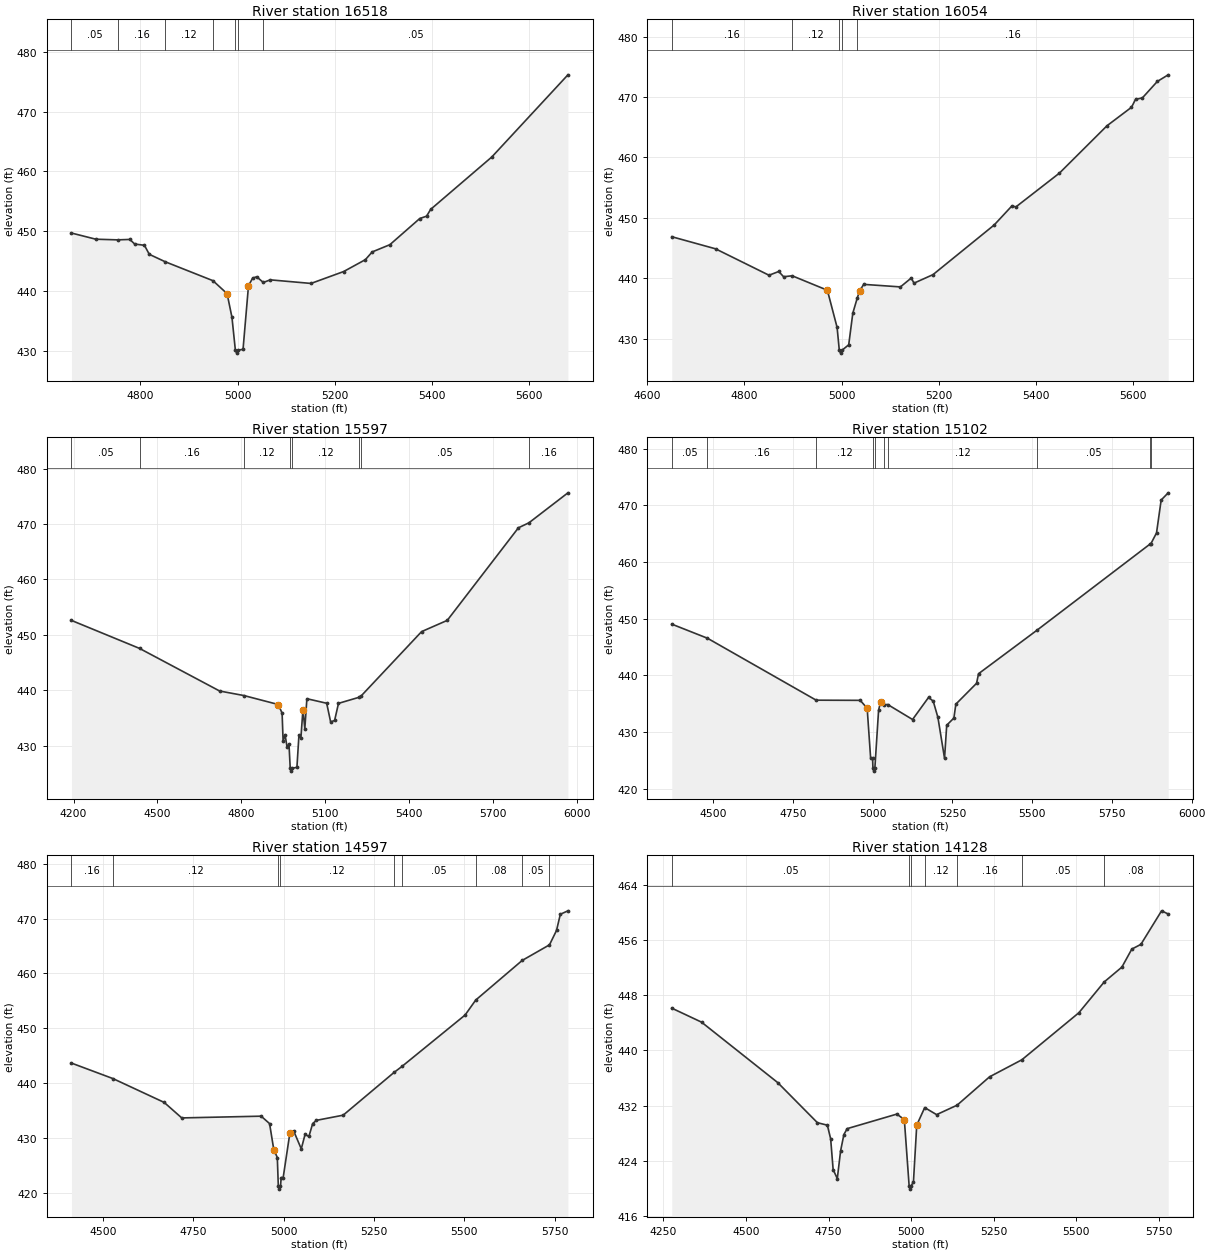
Type RM Length L Ch R = 1 ,16518   ,464,464,464
BEGIN DESCRIPTION:
UNT 121 IN UKCR 29.0
END DESCRIPTION:
XS GIS Cut Line= 3
      3574849.61     10583410.23      3574849.61     10583060.19
      3574549.59     10582460.15
#Sta/Elev= 30
  4658.3  449.67  4708.3  448.64  4753.1  448.53  4778.3   448.6  4788.3  447.83
  4808.3  447.62  4818.3  446.11  4851.2  444.86  4949.2   441.7  4978.3  439.53
  4988.3  435.57  4995.3  430.08  4998.1  429.58  5001.3  430.08  5011.1  430.22
  5022.3  440.86  5030.7  442.11  5039.1  442.36  5052.8   441.4    5067  441.84
  5150.9  441.24    5218  443.23  5262.7  445.22  5276.7  446.51    5313  447.72
  5374.5   452.1  5388.5  452.49  5396.9  453.63  5522.6  462.39  5679.2  476.14
#Mann= 7 ,-1 , 0
  4658.3     .05       0  4753.1     .16       0  4851.2     .12       0
  4949.2     .16       0  4995.3     .07       0  5001.3     .16       0
  5052.8     .05       0
Bank Sta=4978.3,5022.3
XS Rating Curve= 0 ,0
Exp/Cntr=0.3,0.1

Type RM Length L Ch R = 1 ,16054   ,457,457,457
BEGIN DESCRIPTION:
UNT 121 IN UKCR 28.0
END DESCRIPTION:
XS GIS Cut Line= 3
      3575249.61     10583210.16      3575249.61     10582860.19
      3574949.61     10582260.18
#Sta/Elev= 30
  4650.9   446.9  4740.9   444.9  4850.9  440.53  4870.9  441.15  4880.9  440.28
  4898.5  440.44  4970.9  438.05  4990.9   431.9  4995.4  428.15  4998.1  427.65
  5001.4  428.15  5014.8  429.03  5023.2  434.26  5032.2  436.72  5037.2  437.94
  5045.6  439.02  5121.1   438.6  5143.4  440.07    5149  439.22  5188.1  440.63
  5313.9  448.84  5350.3  451.99  5358.6  451.83  5448.1  457.42  5545.9  465.25
  5596.2   468.3  5604.6  469.62  5618.6  469.85  5649.3  472.57  5671.7  473.67
#Mann= 5 ,-1 , 0
  4650.9     .16       0  4898.5     .12       0  4995.4     .07       0
  5001.4     .12       0  5032.2     .16       0
Bank Sta=4970.9,5037.2
XS Rating Curve= 0 ,0
Exp/Cntr=0.3,0.1

Type RM Length L Ch R = 1 ,15597   ,495,495,495
BEGIN DESCRIPTION:
UNT 121 IN UKCR 27.0
END DESCRIPTION:
XS GIS Cut Line= 3
      3575649.61     10583610.24      3575649.61     10582860.19
      3574949.58     10582110.16
#Sta/Elev= 30
  4192.8   452.6  4436.2  447.55  4722.8  439.86  4809.8  439.04  4932.8  437.42
  4946.3  435.85  4949.9  430.78  4956.8  431.99  4964.1  429.73  4970.9  430.29
  4975.3   425.9    4978   425.4  4981.3   425.9  4999.3  426.09  5006.6  431.96
  5013.4  431.34  5020.8  436.48  5027.6  433.08  5034.9  438.47  5105.8  437.65
  5119.9  434.28  5134.1  434.54    5148  437.63  5221.1  438.72  5229.6     439
  5445.3  450.58  5537.1  452.61  5791.7  469.32  5829.3  470.22  5968.8  475.63
#Mann= 8 ,-1 , 0
  4192.8     .05       0  4436.2     .16       0  4809.8     .12       0
  4975.3     .07       0  4981.3     .12       0  5221.1     .16       0
  5229.6     .05       0  5829.3     .16       0
Bank Sta=4932.8,5020.8
XS Rating Curve= 0 ,0
Exp/Cntr=0.3,0.1

Type RM Length L Ch R = 1 ,15102   ,505,505,505
BEGIN DESCRIPTION:
UNT 121 IN UKCR 26.0
END DESCRIPTION:
XS GIS Cut Line= 3
      3575749.62     10583460.16      3576049.61     10582910.19
      3576599.59     10582160.21
#Sta/Elev= 30
  4369.9  449.04  4481.9  446.55  4822.7  435.62  4960.8  435.59  4982.6   434.2
  4993.5  425.38  4999.5  425.38  5000.7   423.6  5003.4   423.1  5006.7   423.6
  5018.4  433.85  5024.6  435.32  5034.8  434.84  5047.1  434.85  5124.9  432.21
  5175.1  436.11  5189.7  435.45  5204.4  432.58  5225.2  425.35    5232   431.2
  5254.5  432.47  5260.7  434.92  5325.6   438.6  5331.8  440.29  5515.1  447.97
  5869.8  463.18  5872.3  463.24  5889.8  465.13  5904.4  470.94  5926.4  472.21
#Mann= 10 ,-1 , 0
  4369.9     .05       0  4481.9     .16       0  4822.7     .12       0
  5000.7     .07       0  5006.7     .12       0  5034.8     .16       0
  5047.1     .12       0  5515.1     .05       0  5869.8     .08       0
  5872.3      .1       0
Bank Sta=4982.6,5024.6
XS Rating Curve= 0 ,0
Exp/Cntr=0.3,0.1

Type RM Length L Ch R = 1 ,14597   ,469,469,469
BEGIN DESCRIPTION:
UNT 121 IN UKCR 25.0
END DESCRIPTION:
XS GIS Cut Line= 3
      3575949.63     10583310.18      3576449.61     10583010.19
       3576699.6     10582260.23
#Sta/Elev= 30
  4413.2  443.63    4528   440.8  4669.7  436.45  4718.3  433.62    4938  433.94
  4961.3  432.58  4972.9  427.84  4982.7  426.39  4985.5  421.12  4988.2  420.62
  4991.5  421.12  4993.4  422.72  4998.9  422.72  5017.4  430.83  5027.9  431.25
    5049  427.97  5059.5  430.61  5070.1  430.23  5080.6   432.6  5091.1  433.18
  5164.9  434.12  5305.6  441.92  5327.6  443.02  5502.2   452.4  5531.7  455.14
  5660.2  462.37  5735.8  465.22  5755.2  467.84  5765.8   470.8  5786.8  471.43
#Mann= 9 ,-1 , 0
  4413.2     .16       0    4528     .12       0  4985.5     .07       0
  4991.5     .12       0  5305.6     .16       0  5327.6     .05       0
  5531.7     .08       0  5660.2     .05       0  5735.8     .08       0
Bank Sta=4972.9,5017.4
XS Rating Curve= 0 ,0
Exp/Cntr=0.3,0.1

Type RM Length L Ch R = 1 ,14128   ,628,628,628
BEGIN DESCRIPTION:
UNT 121 IN UKCR 24.0
END DESCRIPTION:
XS GIS Cut Line= 3
      3576749.61     10583960.18      3576799.61     10583260.19
      3576849.61     10582460.23
#Sta/Elev= 30
    4275  446.13  4365.2   444.1  4595.8  435.34  4716.1  429.52  4746.2  429.16
  4756.2  427.18  4763.7  422.73  4776.3  421.41  4786.3  425.44  4796.3  427.81
  4806.3  428.66  4956.7  430.77  4979.3  429.97  4993.8  420.39  4996.6  419.89
  4999.8  420.39  5006.8  420.87  5016.9  429.17    5041  431.71    5077  430.69
  5139.1  432.06  5237.3  436.17  5335.1  438.64  5507.8  445.46  5584.6  449.93
  5638.1  452.08  5668.1  454.69  5695.7  455.38  5758.3  460.24  5778.3  459.78
#Mann= 7 ,-1 , 0
    4275     .05       0  4993.8     .03       0  4999.8     .05       0
    5041     .12       0  5139.1     .16       0  5335.1     .05       0
  5584.6     .08       0
Bank Sta=4979.3,5016.9
XS Rating Curve= 0 ,0
Exp/Cntr=0.3,0.1

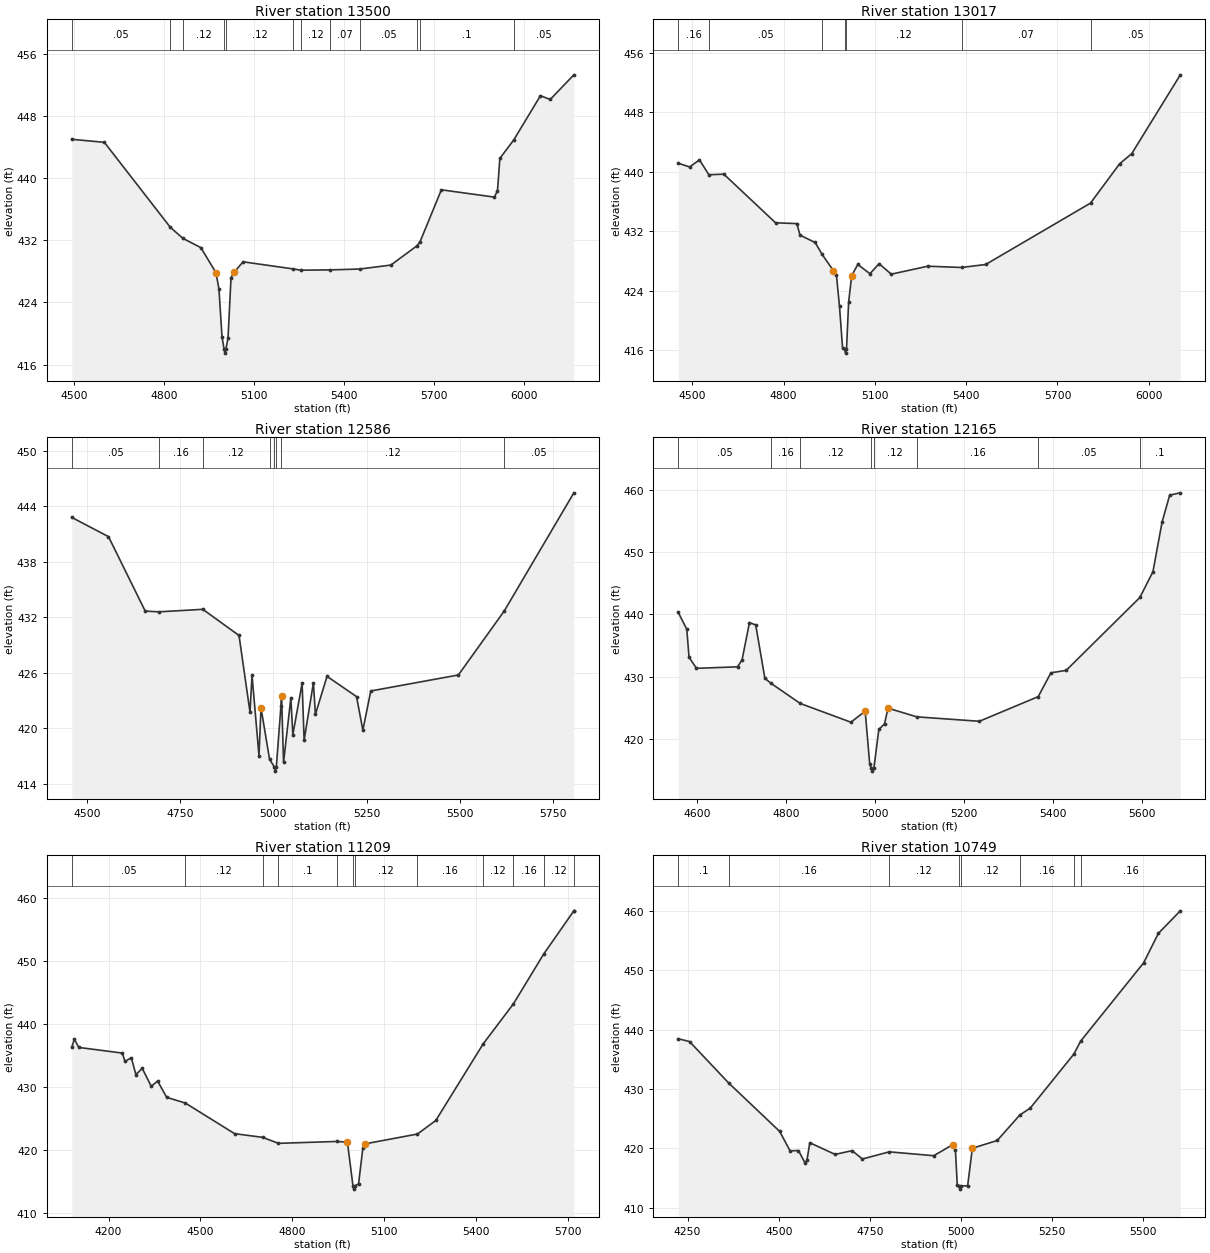
Type RM Length L Ch R = 1 ,13500   ,483,483,483
BEGIN DESCRIPTION:
UNT 121 IN UKCR 23.0
END DESCRIPTION:
XS GIS Cut Line= 3
       3577251.4     10583878.16      3577355.57     10582793.04
      3577181.94     10582237.44
#Sta/Elev= 30
  4492.2  445.03  4600.7  444.64  4820.6  433.68  4862.8  432.25  4922.1  431.07
  4972.4  427.84  4982.4  425.74  4992.5   419.6  4999.5  417.97  5002.3  417.47
  5005.5  417.97  5012.6  419.39  5022.6  427.19  5032.6  427.88  5062.8  429.24
    5230  428.32  5255.4  428.16  5353.6   428.2  5451.7  428.31    5555  428.82
  5641.5  431.29    5652  431.81  5723.2  438.52  5899.6  437.58  5910.1  438.39
    5918  442.57  5964.1  444.94  6053.2  450.65  6085.7  450.16  6164.4  453.34
#Mann= 12 ,-1 , 0
  4492.2     .05       0  4820.6     .16       0  4862.8     .12       0
  4999.5     .07       0  5005.5     .12       0    5230     .07       0
  5255.4     .12       0  5353.6     .07       0  5451.7     .05       0
  5641.5     .08       0    5652      .1       0  5964.1     .05       0
Bank Sta=4972.4,5032.6
XS Rating Curve= 0 ,0
Exp/Cntr=0.3,0.1

Type RM Length L Ch R = 1 ,13017   ,431,431,431
BEGIN DESCRIPTION:
UNT 121 IN UKCR 22.0
END DESCRIPTION:
XS GIS Cut Line= 2
      3577633.35     10583799.95      3577685.43     10582150.67
#Sta/Elev= 30
  4453.6  441.17    4491  440.67  4523.4  441.62  4554.3  439.62  4603.4   439.7
  4773.5  433.16  4843.6  433.05  4853.6   431.5  4903.6  430.51  4926.4  428.91
  4963.6  426.72  4973.6  426.09  4983.6  421.92  4993.6  416.37  5000.6  416.13
  5003.4  415.63  5006.6  416.13  5013.6  422.47  5023.6  426.05  5043.7  427.55
  5083.7  426.31  5113.7  427.66  5153.7  426.25  5273.8  427.32  5384.8  427.15
  5463.9  427.55  5808.6  435.81  5904.1  441.09  5944.1  442.46  6103.7  453.06
#Mann= 7 ,-1 , 0
  4453.6     .16       0  4554.3     .05       0  4926.4     .12       0
  5000.6     .07       0  5006.6     .12       0  5384.8     .07       0
  5808.6     .05       0
Bank Sta=4963.6,5023.6
XS Rating Curve= 0 ,0
Exp/Cntr=0.3,0.1

Type RM Length L Ch R = 1 ,12586   ,421,421,421
BEGIN DESCRIPTION:
UNT 121 IN UKCR 21.0
END DESCRIPTION:
XS GIS Cut Line= 3
      3577799.62     10583660.17      3577999.61     10583210.19
       3578299.6     10582410.21
#Sta/Elev= 30
  4459.2  442.81  4557.7  440.73  4656.2  432.68  4692.8   432.6  4810.8  432.87
  4907.9  430.04  4937.3  421.75  4942.7  425.75  4961.4  417.04  4966.8  422.22
  4989.9  416.63    5002  415.87  5004.8  415.37    5008  415.87  5020.3  422.42
  5021.9  423.53  5027.3  416.33  5046.9  423.28  5052.2  419.31  5077.1  424.88
  5082.5  418.71  5107.4  424.93  5112.7   421.5  5143.9  425.62  5223.1  423.43
    5240   419.8  5261.3  424.04  5496.3  425.77  5619.3  432.69    5806  445.47
#Mann= 8 ,-1 , 0
  4459.2     .05       0  4692.8     .16       0  4810.8     .12       0
  4989.9     .16       0    5002     .07       0    5008     .16       0
  5020.3     .12       0  5619.3     .05       0
Bank Sta=4966.8,5021.9
XS Rating Curve= 0 ,0
Exp/Cntr=0.3,0.1

Type RM Length L Ch R = 1 ,12165   ,956,956,956
BEGIN DESCRIPTION:
UNT 121 IN UKCR 20.0
END DESCRIPTION:
XS GIS Cut Line= 3
      3578249.61     10583460.17      3578349.61     10583010.19
       3578499.6     10582360.23
#Sta/Elev= 30
  4557.4  440.32  4576.6  437.61  4581.7  433.12  4598.4  431.35  4690.6  431.59
  4700.8   432.7  4717.4  438.68  4731.5   438.3    4752  429.76  4765.3  428.97
  4831.4  425.72  4945.4  422.71  4977.4  424.48  4987.6     416    4991  415.37
  4993.8  414.87    4997  415.37  5008.1  421.56  5020.9  422.45  5028.6  424.97
  5093.4  423.57  5233.9  422.86  5366.1  426.81  5394.7  430.63  5428.9  431.02
  5594.6  442.71  5623.9  446.83  5644.4  454.78  5661.5  459.11  5685.4  459.48
#Mann= 8 ,-1 , 0
  4557.4     .05       0  4765.3     .16       0  4831.4     .12       0
    4991     .07       0    4997     .12       0  5093.4     .16       0
  5366.1     .05       0  5594.6      .1       0
Bank Sta=4977.4,5028.6
XS Rating Curve= 0 ,0
Exp/Cntr=0.3,0.1

Type RM Length L Ch R = 1 ,11209   ,460,460,460
BEGIN DESCRIPTION:
UNT 121 IN UKCR 19.0
END DESCRIPTION:
XS GIS Cut Line= 4
      3578197.56     10583669.79      3578744.46     10583270.47
      3579056.96     10582775.68      3579108.85     10582403.76
#Sta/Elev= 30
  4080.1  436.24  4088.4  437.57    4103  436.25  4245.2  435.35  4253.6  434.03
  4274.5  434.61  4289.2  431.94    4310  432.92  4339.4  430.08  4360.2  430.91
  4389.6  428.33  4450.5  427.42  4611.2  422.56  4702.7  421.97  4754.3  421.02
  4944.5  421.32  4979.3  421.21  4997.5  414.25  5000.3  413.75  5003.5  414.25
  5015.8  414.61  5029.6  420.24    5037  420.94  5207.9   422.5  5267.6  424.65
  5422.4  436.83  5520.9  443.17  5619.4  451.06  5717.9  457.93    5718  457.94
#Mann= 12 ,-1 , 0
  4080.1     .05       0  4450.5     .12       0  4702.7     .08       0
  4754.3      .1       0  4944.5     .12       0  4997.5     .07       0
  5003.5     .12       0  5207.9     .16       0  5422.4     .12       0
  5520.9     .16       0  5619.4     .12       0  5717.9     .08       0
Bank Sta=4979.3,5037
XS Rating Curve= 0 ,0
Exp/Cntr=0.3,0.1

Type RM Length L Ch R = 1 ,10749   ,412,412,412
BEGIN DESCRIPTION:
UNT 121 IN UKCR 18.0
END DESCRIPTION:
XS GIS Cut Line= 3
      3578999.61     10583810.17      3579199.61     10583010.19
      3579249.61     10582460.16
#Sta/Elev= 30
  4224.3  438.45  4255.2  437.98  4362.6  431.01  4502.6  422.86  4530.9   419.6
  4554.1  419.65  4572.2  417.54  4577.3  418.01  4585.1  420.96  4654.6     419
    4701  419.63  4729.4  418.23  4802.9  419.43  4925.2  418.78  4976.7  420.63
  4984.5  419.69  4989.6   413.8  4994.4  413.66  4997.1  413.16  5000.4  413.66
    5018  413.74  5030.9  420.03  5099.1  421.34  5161.3  425.64  5189.5  426.77
    5309  435.85  5327.9  438.05  5500.8  451.23  5540.9  456.16  5601.2  459.96
#Mann= 8 ,-1 , 0
  4224.3      .1       0  4362.6     .16       0  4802.9     .12       0
  4994.4     .07       0  5000.4     .12       0  5161.3     .16       0
    5309     .12       0  5327.9     .16       0
Bank Sta=4976.7,5030.9
XS Rating Curve= 0 ,0
Exp/Cntr=0.3,0.1

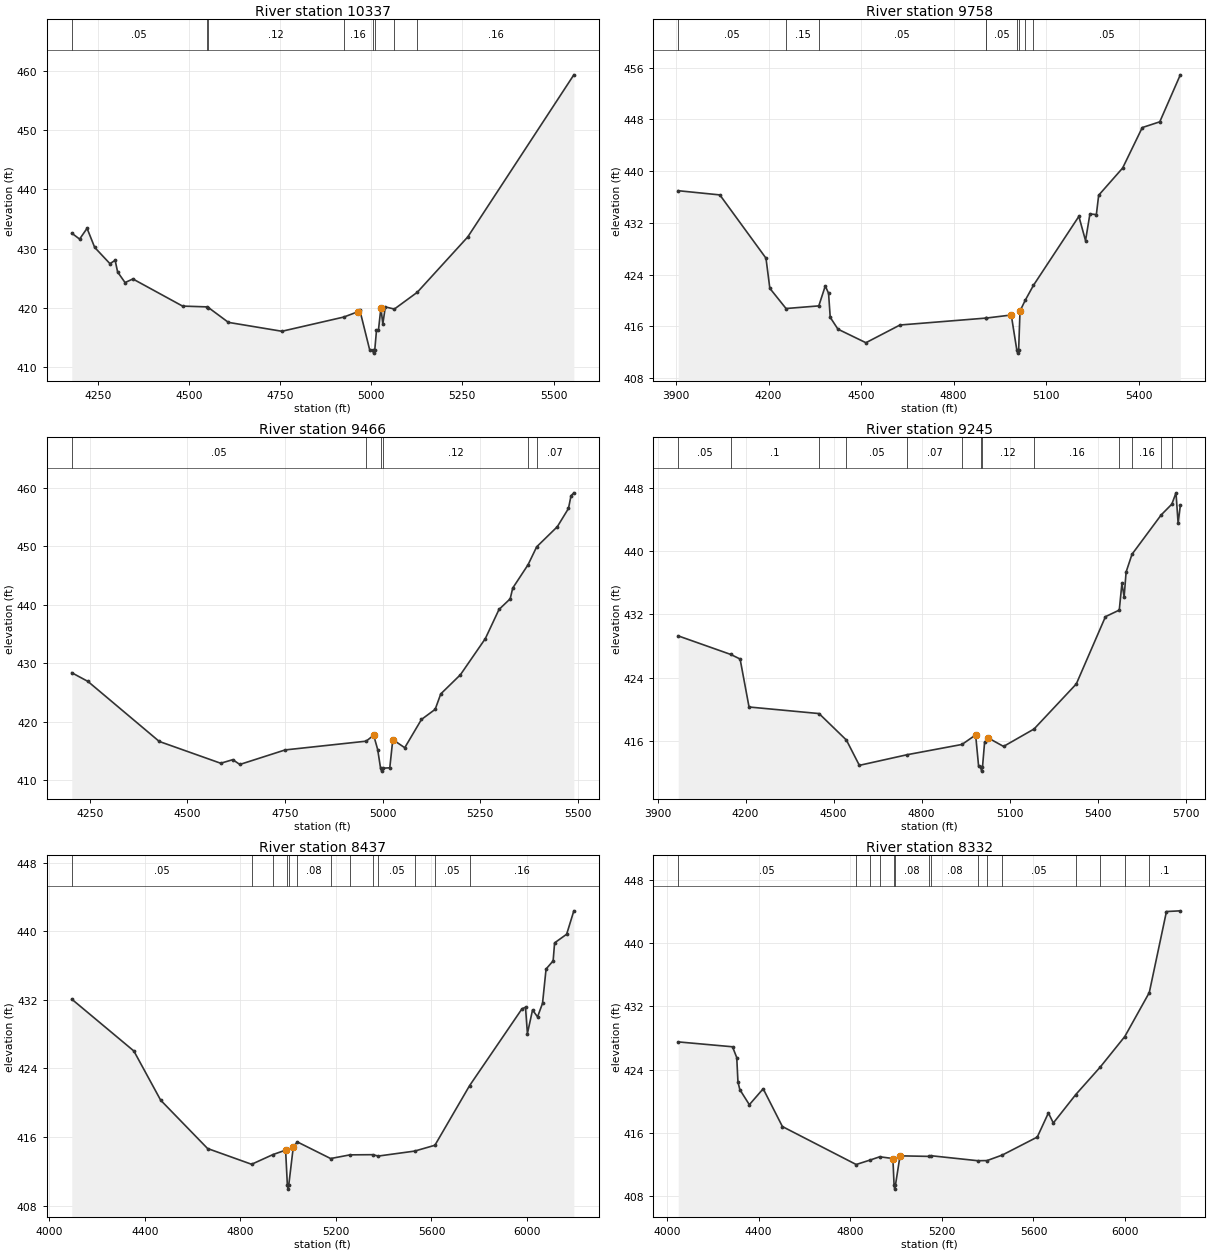
Type RM Length L Ch R = 1 ,10337   ,579,579,579
BEGIN DESCRIPTION:
UNT 121 IN UKCR 17.0
END DESCRIPTION:
XS GIS Cut Line= 3
       3579799.6     10583760.16      3579549.61     10582960.19
      3579349.62     10582460.23
#Sta/Elev= 30
  4179.1   432.6  4200.6   431.6    4221  433.42  4241.9   430.2  4283.8  427.45
    4298  428.02  4304.8  426.05  4325.2  424.26  4346.7  424.87  4482.9  420.29
  4548.6  420.16  4553.6  420.05  4608.6  417.54  4755.3  416.04  4924.9  418.44
  4963.3  419.33  4968.5   419.7  4995.7  412.96  5003.8  412.85  5006.5  412.35
  5009.8  412.85  5014.6  416.19  5019.9  416.19  5026.7  419.99    5032  417.28
  5038.8  420.15  5063.6  419.79  5126.4  422.62  5264.9  431.97  5555.7  459.33
#Mann= 8 ,-1 , 0
  4179.1     .05       0  4548.6     .16       0  4553.6     .12       0
  4924.9     .16       0  5003.8     .07       0  5009.8     .16       0
  5063.6     .12       0  5126.4     .16       0
Bank Sta=4963.3,5026.7
XS Rating Curve= 0 ,0
Exp/Cntr=0.3,0.1

Type RM Length L Ch R = 1 ,9758    ,292,292,292
BEGIN DESCRIPTION:
UNT 121 IN UKCR 16.0
END DESCRIPTION:
XS GIS Cut Line= 3
       3580367.7     10583756.54      3580029.18     10582853.81
       3579534.5      10582411.2
#Sta/Elev= 30
    3907  436.98  4041.9  436.33  4191.5  426.54    4204  421.88  4256.5  418.75
  4362.8  419.16  4383.7  422.24  4394.4  421.12  4399.8  417.39  4424.8  415.56
  4515.5  413.46  4625.9   416.2    4904  417.27  4904.8  417.27  4986.8  417.75
  5004.7  412.35  5007.5  411.85  5010.7  412.35  5015.2  418.37  5032.2  420.04
  5058.6  422.33    5206  433.01  5227.6  429.26  5241.8  433.38  5262.7  433.29
  5270.2  436.28  5347.9  440.49  5411.5  446.75  5468.3  447.64  5534.9  454.91
#Mann= 9 ,-1 , 0
    3907     .05       0  4256.5     .15       0  4362.8     .05       0
    4904     .12       0  4904.8     .05       0  5004.7    .035       0
  5010.7     .05       0  5032.2     .16       0  5058.6     .05       0
Bank Sta=4986.8,5015.2
XS Rating Curve= 0 ,0
Exp/Cntr=0.3,0.1

Type RM Length L Ch R = 1 ,9466    ,221,221,221
BEGIN DESCRIPTION:
UNT 121 IN UKCR 15.0
END DESCRIPTION:
XS GIS Cut Line= 3
       3580399.6     10583460.14      3580199.61     10582660.19
      3579849.57     10582360.16
#Sta/Elev= 30
  4203.8  428.38    4245   426.9  4427.9  416.61  4585.1  412.88  4616.1  413.49
  4634.1  412.67  4750.1  415.16  4957.6  416.66  4976.8  417.68  4987.1  415.23
  4994.5  412.03  4997.2  411.53  5000.5  412.03  5018.1   412.1  5025.8  416.93
  5056.4  415.54  5099.2  420.38  5134.3  422.11  5148.6  424.75    5199  428.04
  5262.7  434.22  5297.8  439.22  5326.4  441.04  5332.9  442.88  5372.2  446.88
  5394.2  449.94  5447.1  453.39  5475.6  456.51  5482.2  458.69  5489.4  459.19
#Mann= 6 ,-1 , 0
  4203.8     .05       0  4957.6     .12       0  4994.5     .07       0
  5000.5     .12       0  5372.2     .08       0  5394.2     .07       0
Bank Sta=4976.8,5025.8
XS Rating Curve= 0 ,0
Exp/Cntr=0.3,0.1

Type RM Length L Ch R = 1 ,9245    ,808,808,808
BEGIN DESCRIPTION:
UNT 121 IN UKCR 14.0
END DESCRIPTION:
XS GIS Cut Line= 3
      3580593.41     10583617.65      3580359.04     10582332.97
      3580089.97     10582029.18
#Sta/Elev= 30
  3970.6  429.26  4149.4  426.92  4181.5  426.34    4212  420.28  4450.7  419.45
    4544   416.1  4588.1  412.91  4751.9  414.26    4938  415.55  4984.5  416.75
  4994.7  412.78  5001.9  412.68  5004.6  412.18  5007.9  412.68    5015   415.8
  5026.4  416.39  5079.7   415.3  5183.6   417.5  5327.7  423.19  5427.1  431.69
  5474.2  432.52  5483.2  435.88  5490.8  434.21  5497.5  437.33  5517.6  439.57
  5617.1  444.54  5653.4   445.9  5667.6  447.33  5674.8  443.48  5682.3  445.74
#Mann= 13 ,-1 , 0
  3970.6     .05       0  4149.4      .1       0  4450.7     .15       0
    4544     .05       0  4751.9     .07       0    4938     .12       0
  5001.9     .07       0  5007.9     .12       0  5183.6     .16       0
  5474.2      .1       0  5517.6     .16       0  5617.1     .08       0
  5653.4     .05       0
Bank Sta=4984.5,5026.4
XS Rating Curve= 0 ,0
Exp/Cntr=0.3,0.1

Type RM Length L Ch R = 1 ,8437    ,105,105,105
BEGIN DESCRIPTION:
UNT 121 IN UKCR 13.0
END DESCRIPTION:
XS GIS Cut Line= 5
      3580954.21     10583579.44      3581080.06     10583240.94
      3580928.15     10582576.88      3580598.29     10582047.36
      3580346.58      10581691.5
#Sta/Elev= 30
  4093.9  432.09  4353.9  426.04  4466.1   420.3  4662.5  414.66  4846.8  412.82
  4936.8  413.96  4989.2  414.47  4996.5  410.42  4999.3  409.92  5002.5  410.42
  5021.4  414.85  5038.3  415.43  5177.7  413.49  5258.9  413.92  5353.6  413.94
  5377.4  413.78  5529.6  414.36  5614.3  415.04  5759.5     422  5978.8  430.96
  5993.6  431.15  6001.6  428.08  6023.1  430.83    6044  430.02  6064.9  431.61
  6079.7  435.61  6109.3  436.56  6115.4  438.66  6165.9  439.67    6196   442.4
#Mann= 13 ,-1 , 0
  4093.9     .05       0  4846.8     .12       0  4936.8     .16       0
  4996.5     .07       0  5002.5     .16       0  5038.3     .08       0
  5177.7     .12       0  5258.9     .05       0  5353.6     .12       0
  5377.4     .05       0  5529.6     .12       0  5614.3     .05       0
  5759.5     .16       0
Bank Sta=4989.2,5021.4
XS Rating Curve= 0 ,0
Exp/Cntr=0.3,0.1

Type RM Length L Ch R = 1 ,8332    ,369,369,369
BEGIN DESCRIPTION:
UNT 121 IN UKCR 12.0
END DESCRIPTION:
XS GIS Cut Line= 5
      3581053.59      10583611.8      3581202.89     10583215.98
      3581052.28     10582664.33      3580996.29     10582549.75
      3580607.48     10581553.87
#Sta/Elev= 30
  4049.5   427.5  4286.4  426.88  4304.9  425.51  4310.2  422.41  4318.4  421.45
  4359.9  419.54  4420.3  421.56  4504.2  416.77  4826.2  411.96  4888.5  412.54
    4929  412.94  4986.5  412.72  4991.6  409.34  4994.4  408.84  4997.6  409.34
  5017.6  413.06    5142  412.99  5153.9  413.07  5357.1  412.44  5397.6  412.46
    5464  413.16  5616.7  415.44  5665.3   418.5  5686.7  417.22  5784.8  420.83
  5891.8  424.32  5998.7  428.18  6105.6  433.75  6180.5  444.02    6241  444.11
#Mann= 15 ,-1 , 0
  4049.5     .05       0  4826.2     .16       0  4888.5     .05       0
    4929     .08       0  4991.6     .07       0  4997.6     .08       0
    5142     .05       0  5153.9     .08       0  5357.1     .05       0
  5397.6     .08       0    5464     .05       0  5784.8     .08       0
  5891.8     .05       0  5998.7     .08       0  6105.6      .1       0
Bank Sta=4986.5,5017.6
XS Rating Curve= 0 ,0
Exp/Cntr=0.3,0.1

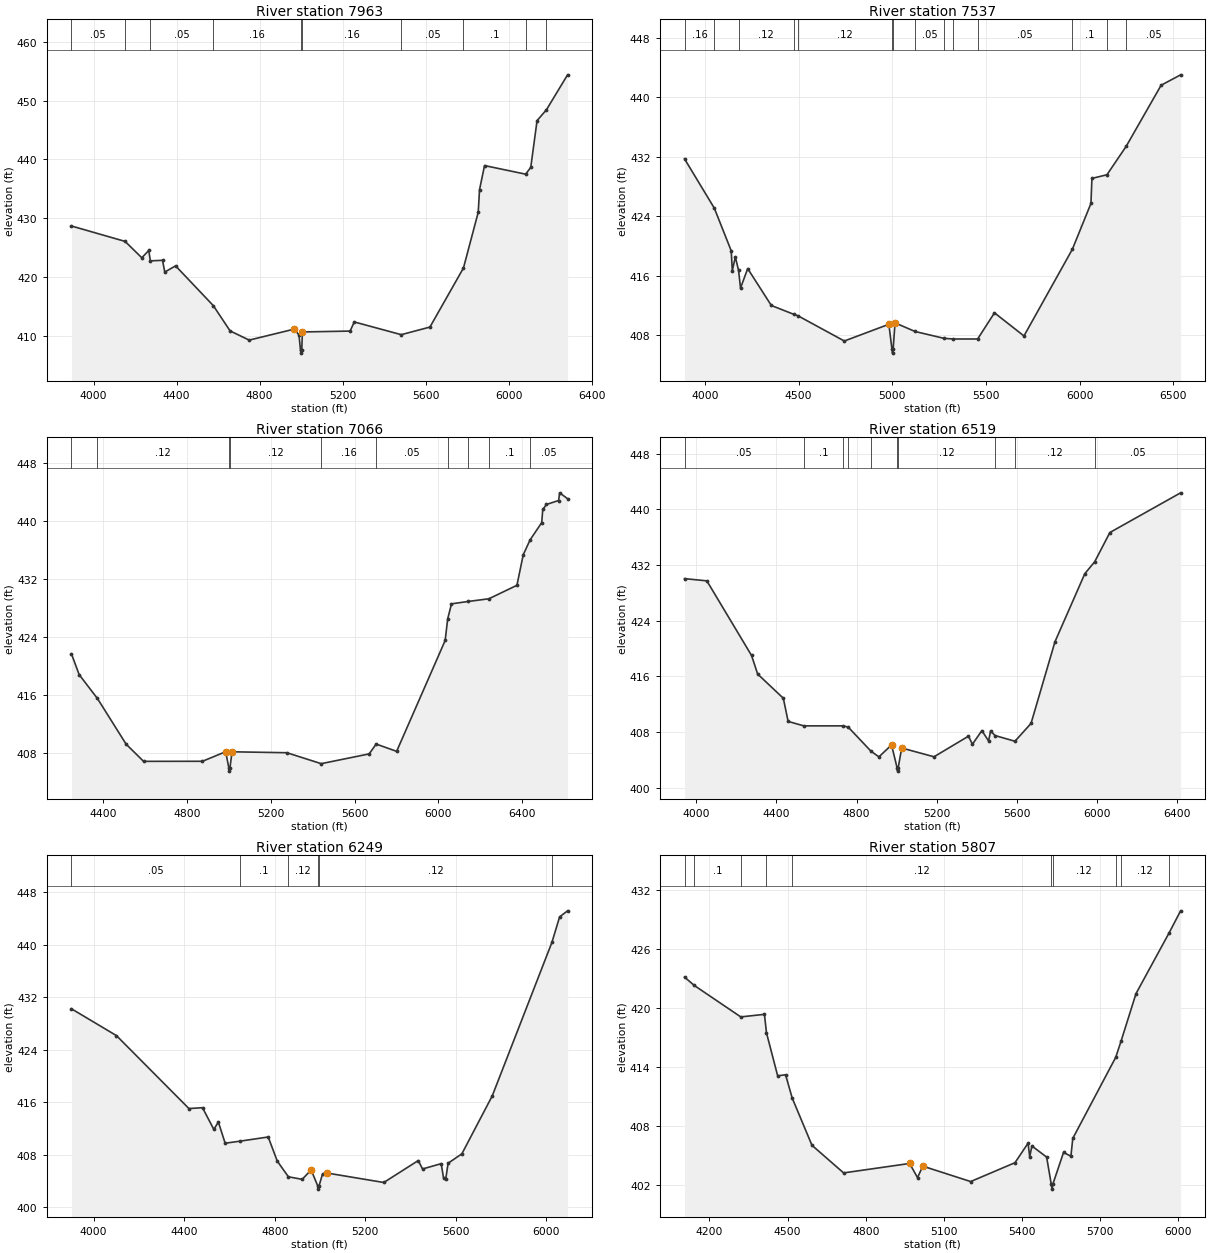
Type RM Length L Ch R = 1 ,7963    ,426,426,426
BEGIN DESCRIPTION:
Mapping XS 262ac3e8
END DESCRIPTION:
XS GIS Cut Line= 3
      3581088.74     10583831.22      3581431.62     10582672.36
      3581249.36     10581505.02
#Sta/Elev= 30
  3893.3  428.72  4151.6  426.11  4232.2  423.33  4265.5  424.57  4273.4  422.81
    4332   422.9  4342.8  420.91  4394.9  421.96  4576.8  415.21  4657.5  410.93
  4749.5  409.37  4967.3  411.24  4989.4  410.22  4996.8  407.66  4999.5  407.16
  5002.8  407.66  5005.8  410.75  5235.6   410.9  5255.8  412.45  5482.1  410.29
  5620.2  411.58  5781.8   421.6    5853  431.06  5859.2  434.88  5883.3  438.97
  6081.4  437.51    6106  438.67  6136.4   446.6  6181.3  448.42  6283.3  454.36
#Mann= 10 ,-1 , 0
  3893.3     .05       0  4151.6     .12       0  4273.4     .05       0
  4576.8     .16       0  4996.8     .07       0  5002.8     .16       0
  5482.1     .05       0  5781.8      .1       0  6081.4     .15       0
  6181.3     .08       0
Bank Sta=4967.3,5005.8
XS Rating Curve= 0 ,0
Exp/Cntr=0.3,0.1

Type RM Length L Ch R = 1 ,7537    ,471,471,471
BEGIN DESCRIPTION:
UNT 121 IN UKCR 11.0
END DESCRIPTION:
XS GIS Cut Line= 3
      3581175.54     10583991.82      3581699.61     10583010.19
      3582199.62     10581560.14
#Sta/Elev= 30
  3891.8   431.7  4050.7  425.07    4141  419.33  4146.7  416.66  4162.9  418.51
  4180.1   416.7  4190.6  414.32  4228.8  416.94  4354.9  411.98  4475.8  410.78
  4495.8  410.61  4744.3   407.2  4981.9  409.45  4998.7  406.07  5001.5  405.57
  5004.7  406.07  5014.9  409.64  5121.7  408.48    5276  407.56  5326.4  407.47
  5455.5  407.47  5545.4  410.99  5702.7  407.88  5960.9  419.54    6060   425.7
  6065.3  429.07  6145.4  429.56  6247.7  433.37  6434.4   441.6  6538.4     443
#Mann= 14 ,-1 , 0
  3891.8     .16       0  4050.7     .07       0  4180.1     .12       0
  4475.8     .05       0  4495.8     .12       0  4998.7     .07       0
  5004.7     .12       0  5121.7     .05       0    5276     .12       0
  5326.4     .16       0  5455.5     .05       0  5960.9      .1       0
  6145.4     .08       0  6247.7     .05       0
Bank Sta=4981.9,5014.9
XS Rating Curve= 0 ,0
Exp/Cntr=0.3,0.1

Type RM Length L Ch R = 1 ,7066    ,547,547,547
BEGIN DESCRIPTION:
UNT 121 IN UKCR 10.0
END DESCRIPTION:
XS GIS Cut Line= 3
      3581899.61     10584010.22      3581999.61     10583260.19
      3582199.61     10581660.21
#Sta/Elev= 30
  4248.1  421.65  4284.7  418.79  4372.1  415.49  4509.2  409.18  4592.4  406.81
  4873.6  406.82  4984.6  408.14  4999.2  405.96    5002  405.46  5005.2  405.96
  5014.8  408.13  5276.9     408  5440.8  406.49  5669.9  407.84  5703.1   409.2
  5800.9  408.19  6032.7   423.5  6044.8  426.49  6062.9  428.56  6143.1  428.89
  6241.5  429.26  6375.4  431.12  6405.6  435.34  6438.2  437.39  6493.8  439.78
  6498.8  441.59  6516.4  442.28  6574.4  442.83  6579.4  443.89  6617.2  443.08
#Mann= 10 ,-1 , 0
  4248.1     .05       0  4372.1     .12       0  4999.2     .07       0
  5005.2     .12       0  5440.8     .16       0  5703.1     .05       0
  6044.8     .08       0  6143.1     .15       0  6241.5      .1       0
  6438.2     .05       0
Bank Sta=4984.6,5014.8
XS Rating Curve= 0 ,0
Exp/Cntr=0.3,0.1

Type RM Length L Ch R = 1 ,6519    ,270,270,270
BEGIN DESCRIPTION:
UNT 121 IN UKCR 9.0
END DESCRIPTION:
XS GIS Cut Line= 3
      3582320.84     10584260.09      3582468.41     10583400.68
       3582249.6     10581810.15
#Sta/Elev= 30
    3941  430.05  4052.5  429.73  4275.7  419.02  4306.2  416.35  4434.5  412.87
  4458.4  409.55  4536.5  408.91  4733.5  408.91  4758.8  408.72  4872.6  405.26
  4911.8  404.46    4975  406.17  5002.3  402.91    5005  402.41  5008.3  402.91
  5025.5  405.73    5187  404.47  5359.1  407.43  5378.8  406.27    5426  408.23
  5459.5  406.74  5469.6  408.18  5491.7  407.52  5591.2   406.7  5671.5  409.26
  5791.2     421  5940.3  430.77  5989.4  432.47  6065.2  436.67  6418.5  442.37
#Mann= 10 ,-1 , 0
    3941     .05       0  4536.5      .1       0  4733.5     .08       0
  4758.8      .1       0  4872.6     .12       0  5002.3     .07       0
  5008.3     .12       0  5491.7     .16       0  5591.2     .12       0
  5989.4     .05       0
Bank Sta=4975,5025.5
XS Rating Curve= 0 ,0
Exp/Cntr=0.3,0.1

Type RM Length L Ch R = 1 ,6249    ,442,442,442
BEGIN DESCRIPTION:
UNT 121 IN UKCR 8.0
END DESCRIPTION:
XS GIS Cut Line= 3
      3582676.75      10584268.7      3582711.47     10582914.57
      3582850.35     10582089.96
#Sta/Elev= 30
  3902.3  430.22  4100.9  426.14    4421  415.03    4481  415.16    4531  411.85
    4551  412.98    4581  409.75  4645.7  410.06  4771.1   410.7  4811.1  407.03
  4860.3  404.64  4921.2  404.25  4960.8  405.69  4989.7  403.26  4992.5  402.76
  4995.7  403.26  5011.2  405.09  5031.2  405.21  5281.6  403.77  5433.7  407.11
  5452.7  405.83  5535.1  406.64  5545.3  404.47  5555.4  404.35  5565.5   406.7
  5626.4  408.14  5760.4  416.95  6024.1  440.34    6058  444.22  6093.1  445.14
#Mann= 6 ,-1 , 0
  3902.3     .05       0  4645.7      .1       0  4860.3     .12       0
  4989.7     .07       0  4995.7     .12       0  6024.1     .07       0
Bank Sta=4960.8,5031.2
XS Rating Curve= 0 ,0
Exp/Cntr=0.3,0.1

Type RM Length L Ch R = 1 ,5807    ,571,571,571
BEGIN DESCRIPTION:
UNT 121 IN UKCR 7.0
END DESCRIPTION:
XS GIS Cut Line= 3
       3582919.8     10584043.08      3583110.77     10582862.49
      3583527.41     10582289.61
#Sta/Elev= 30
  4104.2  423.18  4141.6  422.33  4320.1  419.13    4411  419.39  4418.8  417.51
  4461.7  413.14  4492.1  413.24  4517.5  410.88  4593.4  406.07  4714.9  403.26
  4968.2  404.22  4998.6  402.78  5018.8  403.95  5202.6  402.38  5372.8   404.3
  5423.1  406.29  5429.2  404.89  5437.7     406  5494.2  404.87    5512  402.11
  5514.8  401.61    5518  402.11  5559.1  405.34  5587.4  404.96  5594.6  406.77
  5759.5  415.02  5780.5  416.71  5837.3   421.5  5964.4  427.68  6008.5  429.92
#Mann= 10 ,-1 , 0
  4104.2     .05       0  4141.6      .1       0  4320.1     .15       0
  4418.8     .05       0  4517.5     .12       0    5512     .07       0
    5518     .12       0  5759.5      .1       0  5780.5     .12       0
  5964.4     .05       0
Bank Sta=4968.2,5018.8
XS Rating Curve= 0 ,0
Exp/Cntr=0.3,0.1