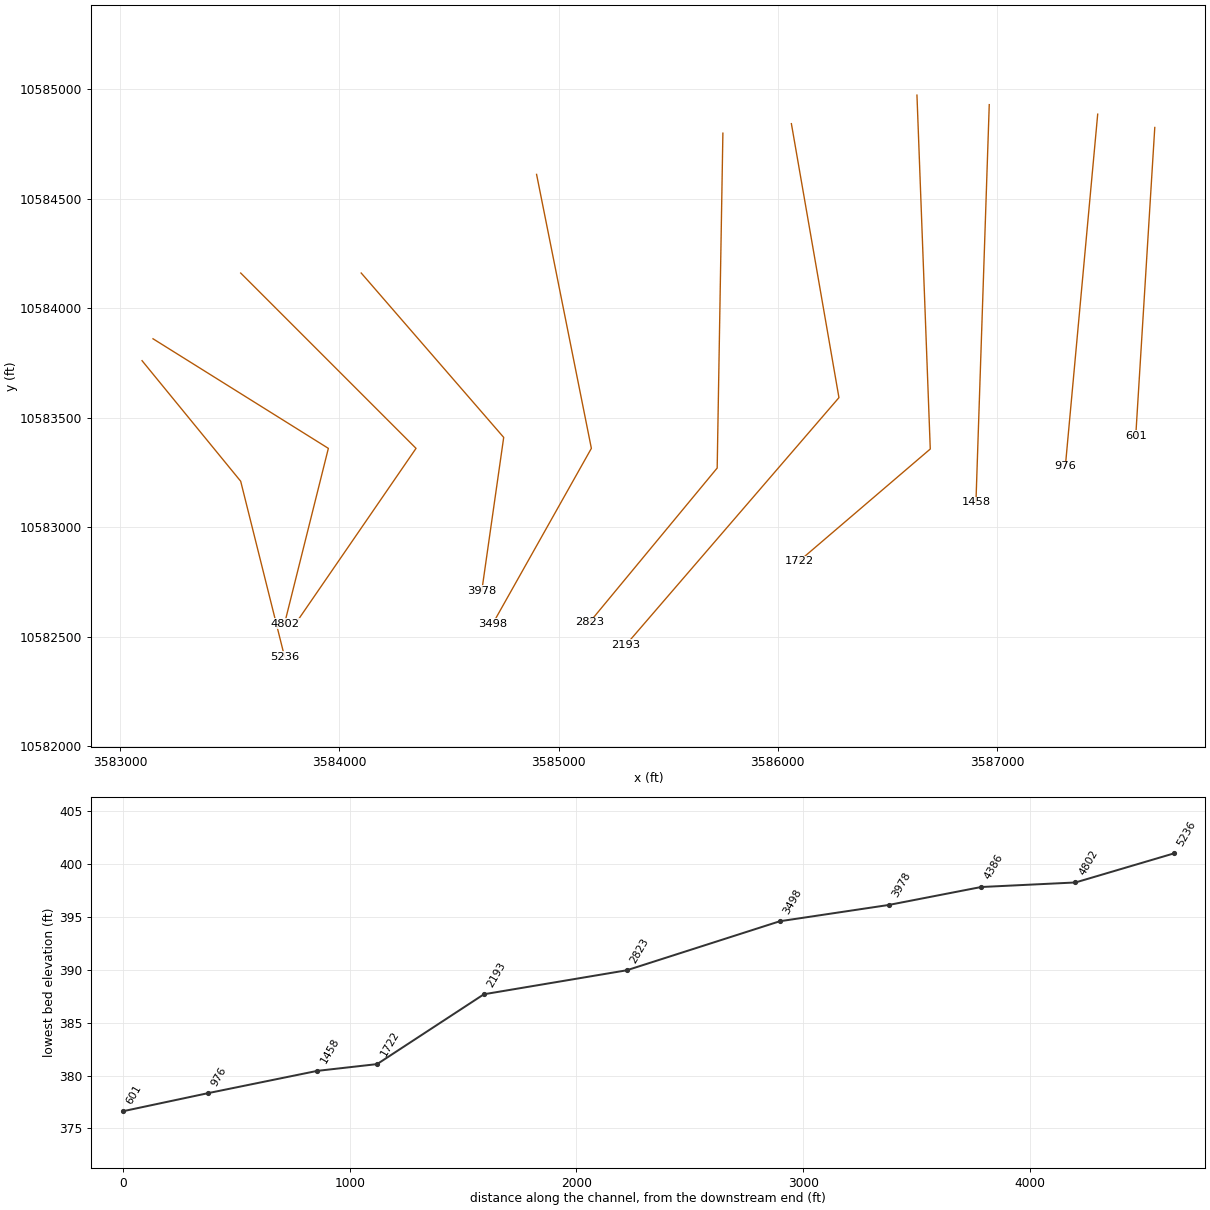
HEC-RAS study UNT 121 IN UKCR.prj: UNT 121 IN UKCR Base Level Engineering

--- UNT 121 IN UKCR.g01 (geometry) --- (continued)

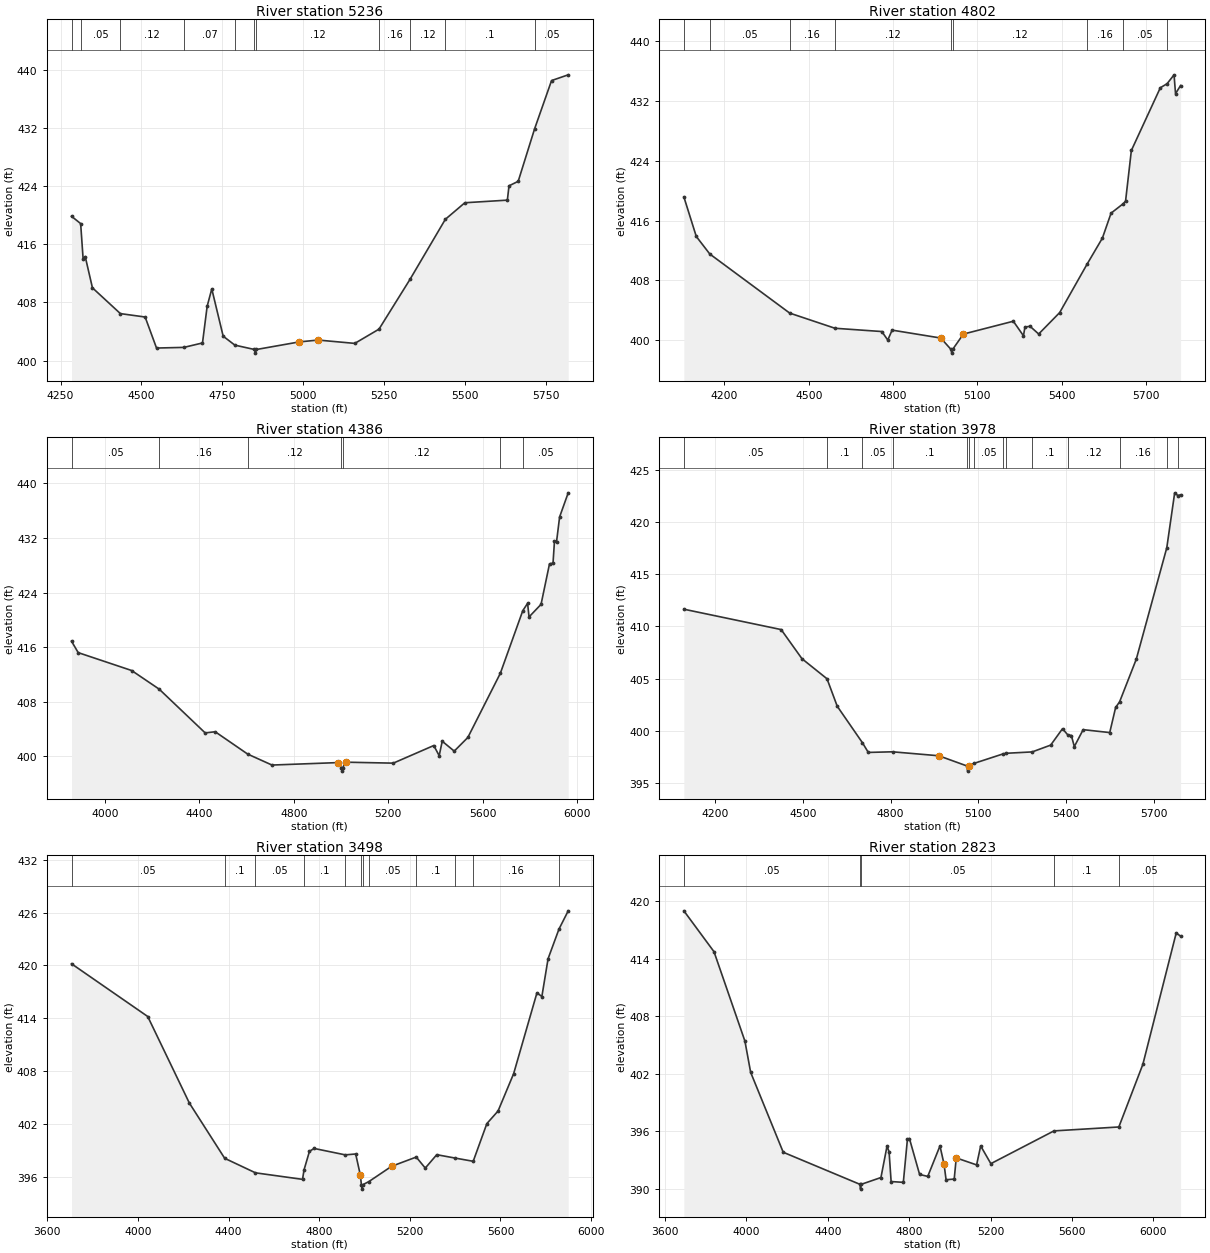
Type RM Length L Ch R = 1 ,5236    ,434,434,434
BEGIN DESCRIPTION:
UNT 121 IN UKCR 6.0
END DESCRIPTION:
XS GIS Cut Line= 3
      3583099.58     10583760.23      3583549.61     10583210.19
      3583749.61     10582410.19
#Sta/Elev= 30
  4283.7  419.86    4312  418.85  4319.6  413.99  4326.1  414.31  4348.4  410.01
  4434.8  406.46  4511.3  405.99  4546.5  401.72    4631  401.81  4688.6  402.42
    4703  407.47  4717.3  409.86  4752.5  403.35  4788.6  402.12  4849.3  401.52
    4852  401.02  4855.3  401.52  4987.2  402.56  5045.9  402.82  5159.3  402.36
  5234.1  404.32  5330.2  411.19  5439.2  419.44  5499.5  421.72  5630.9  422.08
    5636  424.05  5664.4  424.67  5715.2  431.91  5767.5  438.54    5819  439.33
#Mann= 11 ,-1 , 0
  4283.7      .1       0    4312     .05       0  4434.8     .12       0
    4631     .07       0  4788.6     .12       0  4849.3     .07       0
  4855.3     .12       0  5234.1     .16       0  5330.2     .12       0
  5439.2      .1       0  5715.2     .05       0
Bank Sta=4987.2,5045.9
XS Rating Curve= 0 ,0
Exp/Cntr=0.3,0.1

Type RM Length L Ch R = 1 ,4802    ,416,416,416
BEGIN DESCRIPTION:
UNT 121 IN UKCR 5.0
END DESCRIPTION:
XS GIS Cut Line= 3
      3583149.61     10583860.19      3583949.61     10583360.19
      3583749.61     10582560.21
#Sta/Elev= 30
  4055.7  419.19  4099.9  413.89    4148  411.54  4432.4  403.63  4593.5   401.6
  4760.3  401.16  4781.5  400.02  4796.9  401.35  4970.2  400.29  5006.4  398.77
  5009.2  398.27  5012.4  398.77  5050.6  400.82  5228.4  402.54  5264.5  400.59
  5269.7  401.75  5287.7  401.87  5318.6  400.83  5393.4   403.7  5490.4  410.15
  5545.4  413.67  5576.3  417.01    5620  418.29  5627.9  418.63  5648.5   425.4
  5751.6   433.8  5775.6  434.34  5800.5  435.53  5805.7  433.01  5823.7   434.1
#Mann= 9 ,-1 , 0
  4055.7     .08       0    4148     .05       0  4432.4     .16       0
  4593.5     .12       0  5006.4     .07       0  5012.4     .12       0
  5490.4     .16       0    5620     .05       0  5775.6      .1       0
Bank Sta=4970.2,5050.6
XS Rating Curve= 0 ,0
Exp/Cntr=0.3,0.1

Type RM Length L Ch R = 1 ,4386    ,408,408,408
BEGIN DESCRIPTION:
UNT 121 IN UKCR 4.0
END DESCRIPTION:
XS GIS Cut Line= 3
      3583549.63     10584160.17      3584349.61     10583360.19
      3583799.59     10582560.16
#Sta/Elev= 30
  3859.3  416.88  3887.6   415.2  4113.8  412.58  4230.4  409.85    4425  403.44
  4467.4  403.61  4605.2  400.33  4707.8  398.73  4987.1  399.09  5001.2  398.34
  5003.9  397.84  5007.2  398.34  5019.1  399.15  5221.2  399.01  5392.5  401.59
  5415.4   400.1  5428.3  402.22  5479.1  400.77  5536.7  402.77  5674.2  412.17
  5769.3  421.35  5789.6  422.42  5795.7  420.43  5846.5  422.27  5882.3   428.2
  5897.2  428.31  5903.3   431.5  5912.1  431.44  5925.1  435.08  5961.5  438.61
#Mann= 7 ,-1 , 0
  3859.3     .05       0  4230.4     .16       0  4605.2     .12       0
  5001.2     .07       0  5007.2     .12       0  5674.2     .16       0
  5769.3     .05       0
Bank Sta=4987.1,5019.1
XS Rating Curve= 0 ,0
Exp/Cntr=0.3,0.1

Type RM Length L Ch R = 1 ,3978    ,480,480,480
BEGIN DESCRIPTION:
UNT 121 IN UKCR 3.0
END DESCRIPTION:
XS GIS Cut Line= 3
      3584099.59     10584160.21      3584749.61     10583410.19
      3584649.61      10582710.2
#Sta/Elev= 30
  4092.7  411.64  4425.6  409.69  4496.8   406.9  4582.5  404.98  4617.5  402.35
  4703.4  398.87  4723.8  397.93  4806.7  397.99  4965.1  397.61  5060.8  396.64
  5063.6  396.14  5066.8  396.64  5085.4  396.88    5185  397.79  5196.6  397.85
  5284.6  397.98  5347.8  398.63  5388.3   400.2  5406.3  399.61  5418.6  399.55
  5428.7  398.49    5459  400.11  5549.9  399.83  5570.1  402.24  5583.6  402.77
  5640.8  406.86  5745.1  417.52  5772.1  422.78  5782.8  422.52  5792.3  422.59
#Mann= 14 ,-1 , 0
  4092.7     .05       0  4582.5      .1       0  4703.4     .05       0
  4806.7      .1       0  5060.8     .07       0  5066.8      .1       0
  5085.4     .05       0    5185      .1       0  5196.6     .05       0
  5284.6      .1       0  5406.3     .12       0  5583.6     .16       0
  5745.1     .07       0  5782.8      .1       0
Bank Sta=4965.1,5066.8
XS Rating Curve= 0 ,0
Exp/Cntr=0.3,0.1

Type RM Length L Ch R = 1 ,3498    ,675,675,675
BEGIN DESCRIPTION:
UNT 121 IN UKCR 2.0
END DESCRIPTION:
XS GIS Cut Line= 3
      3584899.61     10584610.19      3585149.61     10583360.19
      3584699.63     10582560.22
#Sta/Elev= 30
  3706.4  420.19  4042.9   414.2  4226.5  404.38  4382.6   398.1  4518.6  396.45
  4726.2  395.71    4733   396.8  4756.8  398.89  4777.2  399.22  4914.8  398.49
  4960.8  398.59  4981.2  396.22  4986.1   395.1  4988.9   394.6  4992.1   395.1
  5019.3  395.46  5119.2  397.19  5228.1  398.24    5268  396.99  5318.7  398.51
  5401.2  398.12  5479.6  397.76  5539.9  402.04  5589.3  403.47  5658.1  407.71
    5761  416.89  5782.7  416.47  5810.1  420.76  5858.1  424.12    5899   426.2
#Mann= 12 ,-1 , 0
  3706.4     .05       0  4382.6      .1       0  4518.6     .05       0
    4733      .1       0  4914.8     .15       0  4986.1     .07       0
  4992.1     .15       0  5019.3     .05       0  5228.1      .1       0
  5401.2     .05       0  5479.6     .16       0  5858.1     .05       0
Bank Sta=4981.2,5119.2
XS Rating Curve= 0 ,0
Exp/Cntr=0.3,0.1

Type RM Length L Ch R = 1 ,2823    ,630,630,630
BEGIN DESCRIPTION:
Mapping XS a72a2db7
END DESCRIPTION:
XS GIS Cut Line= 3
      3585749.66      10584798.3      3585723.62     10583270.47
      3585142.05     10582567.38
#Sta/Elev= 30
  3693.3  419.02  3841.4  414.75  3993.2  405.42  4021.5  402.15  4181.5  393.81
  4558.5  390.46  4561.3  389.96  4564.5  390.46  4661.6  391.17  4691.6  394.46
  4701.6  393.85  4711.6  390.75  4771.6  390.67  4791.6  395.15  4801.6  395.24
  4851.6  391.49  4891.6  391.29  4951.6  394.47  4971.6  392.57  4981.6  390.94
  5021.6  391.01  5031.6  393.22  5131.6  392.49  5151.6  394.47  5201.6  392.62
  5511.7  396.04  5830.5  396.45  5948.5  402.99  6112.4  416.71  6133.8  416.37
#Mann= 5 ,-1 , 0
  3693.3     .05       0  4558.5     .03       0  4564.5     .05       0
  5511.7      .1       0  5830.5     .05       0
Bank Sta=4971.6,5031.6
XS Rating Curve= 0 ,0
Exp/Cntr=0.3,0.1

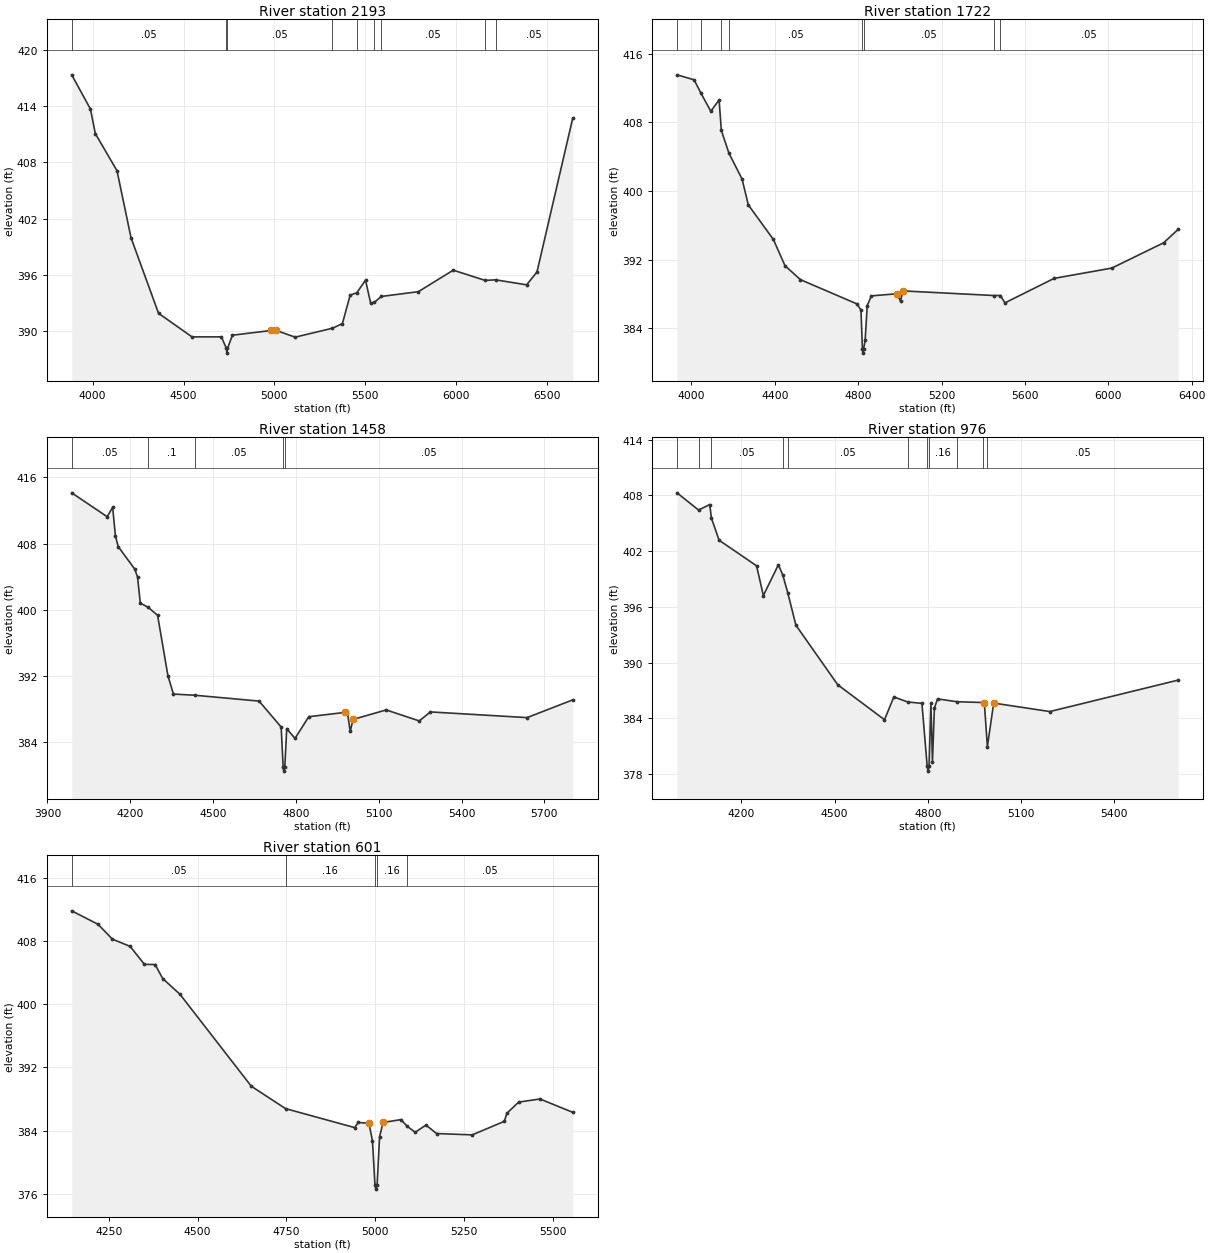
Type RM Length L Ch R = 1 ,2193    ,471,471,471
BEGIN DESCRIPTION:
Mapping XS 81769860
END DESCRIPTION:
XS GIS Cut Line= 3
      3586062.16     10584841.66      3586279.18     10583591.65
      3585307.82     10582464.19
#Sta/Elev= 30
  3884.8  417.31  3987.8  413.67  4014.6  411.06    4134   407.1  4211.1  399.97
  4362.5  391.93  4546.6  389.42  4708.4  389.42  4735.9  388.19  4738.6  387.69
  4741.9  388.19  4769.3   389.6  4982.5   390.1  5008.9  390.11  5114.4  389.39
  5319.6  390.34  5374.1  390.83  5416.9  393.86  5453.6  394.12  5501.4  395.46
  5529.9  392.99  5550.6   393.1  5587.6  393.72  5792.1  394.23  5984.1  396.52
  6159.6  395.43  6216.9  395.49  6387.9  394.96  6444.9  396.33  6641.7  412.71
#Mann= 9 ,-1 , 0
  3884.8     .05       0  4735.9     .03       0  4741.9     .05       0
  5319.6     .08       0  5453.6      .1       0  5550.6     .08       0
  5587.6     .05       0  6159.6      .1       0  6216.9     .05       0
Bank Sta=4982.5,5008.9
XS Rating Curve= 0 ,0
Exp/Cntr=0.3,0.1

Type RM Length L Ch R = 1 ,1722    ,264,264,264
BEGIN DESCRIPTION:
Mapping XS c8e97caa
END DESCRIPTION:
XS GIS Cut Line= 3
      3586635.08     10584971.83      3586695.84     10583357.28
      3586096.93     10582845.16
#Sta/Elev= 30
  3931.3  413.54    4013  412.96  4045.8  411.41  4093.1  409.29  4133.1  410.61
  4143.8  407.05  4180.4  404.39  4243.2  401.39  4273.2  398.37  4393.3  394.34
  4449.4  391.27  4523.4  389.65  4793.5  386.83  4813.6  386.11  4820.6  381.58
  4823.3  381.08  4826.6  381.58  4833.6  382.56  4843.6  386.63  4863.6  387.76
  4985.5     388  5003.7  387.15  5013.7  388.34  5450.9   387.8    5483   387.8
  5504.1  386.94  5740.4   389.8  6017.1     391  6265.7  393.95    6335  395.51
#Mann= 8 ,-1 , 0
  3931.3     .05       0  4045.8      .1       0  4143.8     .08       0
  4180.4     .05       0  4820.6     .03       0  4826.6     .05       0
  5450.9      .1       0    5483     .05       0
Bank Sta=4985.5,5013.7
XS Rating Curve= 0 ,0
Exp/Cntr=0.3,0.1

Type RM Length L Ch R = 1 ,1458    ,482,482,482
BEGIN DESCRIPTION:
Mapping XS da7547d9
END DESCRIPTION:
XS GIS Cut Line= 2
      3586964.94     10584928.41      3586904.19     10583114.73
#Sta/Elev= 30
  3988.2  414.14  4116.5  411.25  4136.5  412.38  4146.5  408.91  4156.5  407.63
  4216.6   404.9  4226.6  403.94  4236.6  400.79  4265.4  400.27  4299.2  399.31
  4336.6     392  4356.6  389.77  4434.4  389.63  4666.8  388.92  4746.8  385.78
  4753.9  380.94  4756.6  380.44  4759.9  380.94  4766.9  385.58  4796.9   384.4
  4846.9  387.03    4977  387.55    4987   387.5    4997  385.24    5007   386.7
  5127.1  387.85  5247.1  386.52  5287.2  387.61  5637.3  386.92  5802.9  389.07
#Mann= 5 ,-1 , 0
  3988.2     .05       0  4265.4      .1       0  4434.4     .05       0
  4753.9     .03       0  4759.9     .05       0
Bank Sta=4977,5007
XS Rating Curve= 0 ,0
Exp/Cntr=0.3,0.1

Type RM Length L Ch R = 1 ,976     ,375,375,375
BEGIN DESCRIPTION:
Mapping XS 536573d6
END DESCRIPTION:
XS GIS Cut Line= 2
      3587459.73     10584885.04      3587312.16     10583279.11
#Sta/Elev= 30
    3993  408.27  4062.2  406.42  4098.3  407.01  4103.6  405.55  4128.4  403.17
  4248.9  400.42  4270.8  397.22  4319.2  400.53  4333.3  399.43  4349.5   397.5
  4375.6  394.03    4510  387.63  4660.7  383.86  4690.8  386.31  4735.4  385.77
  4781.2  385.62  4798.2  378.83    4801  378.33  4804.2  378.83  4810.1  385.69
  4815.1  379.32  4821.3  385.11  4831.4   386.1  4893.4   385.8    4977  385.71
    4982  385.71  4991.9  380.96  5012.1  385.65  5192.9  384.74  5605.7  388.12
#Mann= 11 ,-1 , 0
    3993     .05       0  4062.2     .08       0  4103.6     .05       0
  4333.3     .15       0  4349.5     .05       0  4735.4     .16       0
  4798.2     .03       0  4804.2     .16       0  4893.4     .05       0
    4977     .16       0  4991.9     .05       0
Bank Sta=4982,5012.1
XS Rating Curve= 0 ,0
Exp/Cntr=0.3,0.1

Type RM Length L Ch R = 1 ,601     ,0,0,0
BEGIN DESCRIPTION:
UNT 121 IN UKCR 1.0
END DESCRIPTION:
XS GIS Cut Line= 2
      3587720.15     10584824.26      3587633.34     10583418.04
#Sta/Elev= 30
  4146.1  411.81  4220.3   410.1  4260.4  408.23  4310.5  407.31  4350.6  405.04
  4380.6  405.02    4402  403.25  4450.8  401.24  4651.1  389.63  4747.4   386.8
  4941.7   384.4  4951.7  385.05  4981.8  384.94  4991.8  382.75  4998.8  377.12
  5001.6  376.62  5004.8  377.12  5011.8  383.26  5021.8  385.05  5071.9  385.41
    5089  384.58    5112  383.81  5142.1  384.72  5172.1  383.65  5272.3  383.48
  5362.5  385.19  5369.8  386.21  5402.6  387.62  5462.7  388.02    5555  386.33
#Mann= 5 ,-1 , 0
  4146.1     .05       0  4747.4     .16       0  4998.8     .07       0
  5004.8     .16       0    5089     .05       0
Bank Sta=4981.8,5021.8
XS Rating Curve= 0 ,0
Exp/Cntr=0.3,0.1

Chan Stop Cuts=-1
Use User Specified Reach Order=0
Composite Channel Slope=5