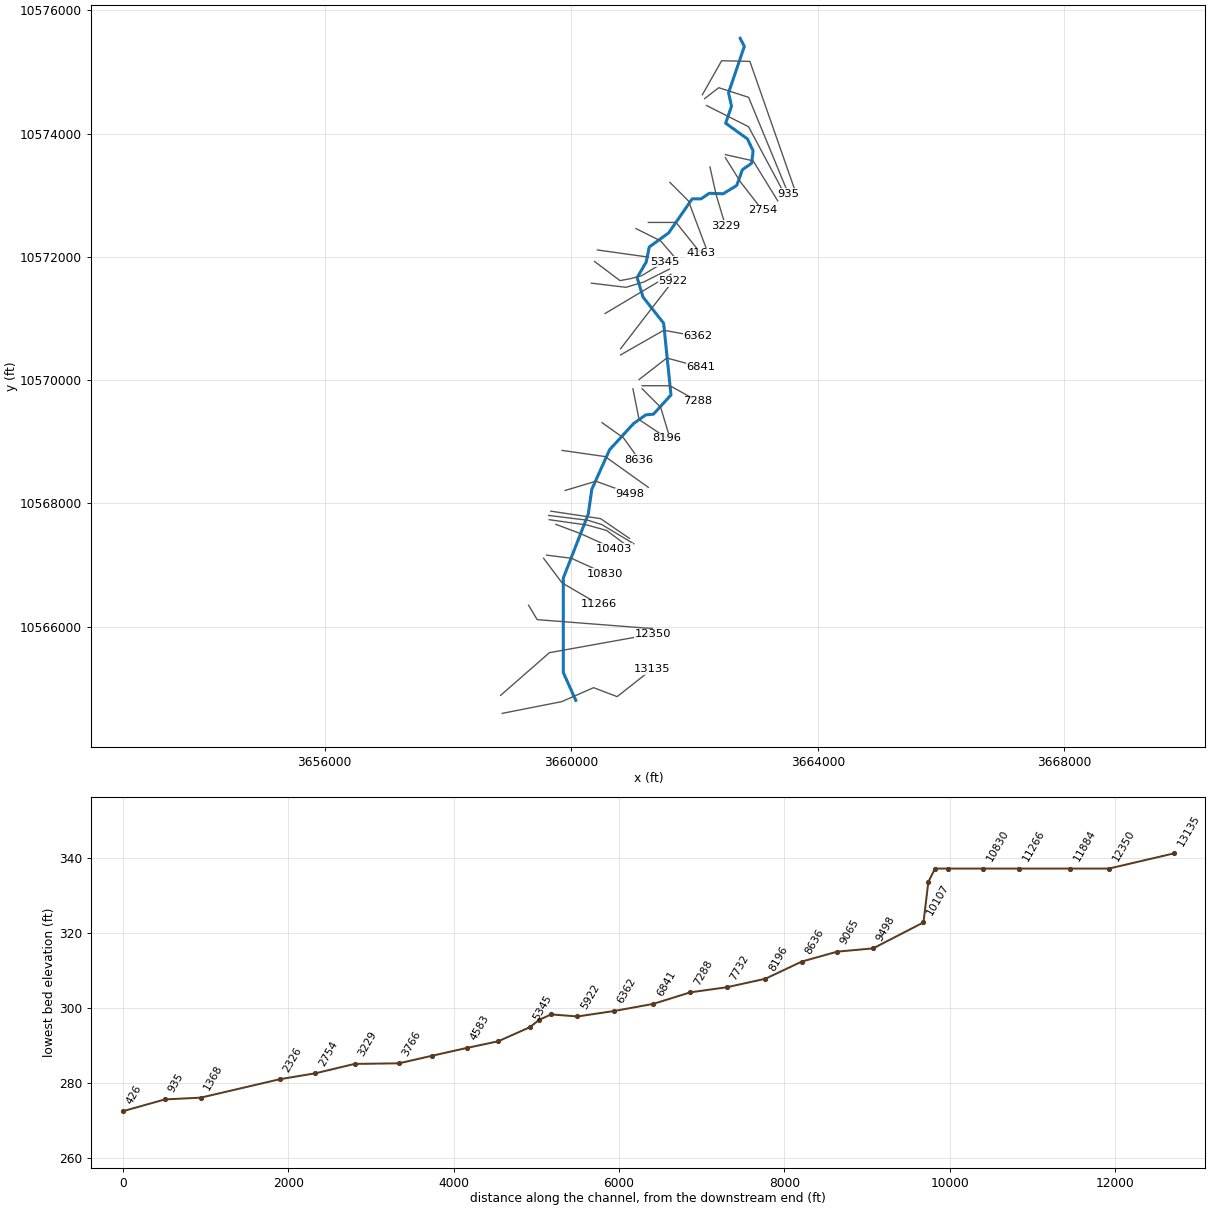
--- UNT 123 IN UKCR.prj (project) ---

Proj Title=UNT 123 IN UKCR Base Level Engineering
Current Plan=p01
Default Exp/Contr=0.3,0.1
English Units
Geom File=g01
Flow File=f01
Plan File=p01
Y Axis Title=Elevation
X Axis Title(PF)=Main Channel Distance
X Axis Title(XS)=Station
BEGIN DESCRIPTION:
UNT 123 IN UKCR
END DESCRIPTION:
DSS Export Rating Curves= 0
DSS Export Rating Curve Sorted= 0
DSS Export Volume Flow Curves= 0
DXF OffsetX= 0
DXF OffsetY= 0
DXF ScaleX= 1
DXF ScaleY= 10

--- UNT 123 IN UKCR.p01 (plan) ---

Plan Title=Multiple Run
Short Identifier=Multiple
Geom File=g01
Flow File=f01
Subcritical Flow
K Sum by GR= 0
Std Step Tol= 0.01
Critical Tol= 0.01
Num of Std Step Trials= 20
Max Error Tol= 0.3
Flow Tol Ratio= 0.001
Split Flow NTrial= 30
Split Flow Tol= 0.02
Split Flow Ratio= 0.02
Log Output Level= 0
Friction Slope Method= 1
Unsteady Friction Slope Method= 2
Unsteady Bridges Friction Slope Method= 1
Parabolic Critical Depth
Global Vel Dist=  1 , 1 , 1
Global Log Level= 0
CheckData=True
Encroach Param= -1, 0, 0, 0
BEGIN DESCRIPTION:
Multiple Run
END DESCRIPTION:

--- UNT 123 IN UKCR.f01 (steady flow) ---

Flow Title=Multiple
Program Version=4.10
Number of Profiles= 7
Profile Names=10-year,25-year,50-year,1pct_min,100-year,1pct_plu,500-year
River Rch & RM=UNT 123 IN UKCR,Reach-1         ,13135
     515     698     850     761    1029    1392    1516
River Rch & RM=UNT 123 IN UKCR,Reach-1         ,11884
     744    1025    1259    1137    1537    2079    2301
River Rch & RM=UNT 123 IN UKCR,Reach-1         ,5345
     799    1102    1356    1225    1657    2240    2483
Boundary for River Rch & Prof#=UNT 123 IN UKCR,Reach-1         , 1
Up Type= 0
Dn Type= 3
Dn Slope=0.004
Boundary for River Rch & Prof#=UNT 123 IN UKCR,Reach-1         , 2
Up Type= 0
Dn Type= 3
Dn Slope=0.004
Boundary for River Rch & Prof#=UNT 123 IN UKCR,Reach-1         , 3
Up Type= 0
Dn Type= 3
Dn Slope=0.004
Boundary for River Rch & Prof#=UNT 123 IN UKCR,Reach-1         , 4
Up Type= 0
Dn Type= 3
Dn Slope=0.004
Boundary for River Rch & Prof#=UNT 123 IN UKCR,Reach-1         , 5
Up Type= 0
Dn Type= 3
Dn Slope=0.004
Boundary for River Rch & Prof#=UNT 123 IN UKCR,Reach-1         , 6
Up Type= 0
Dn Type= 3
Dn Slope=0.004
Boundary for River Rch & Prof#=UNT 123 IN UKCR,Reach-1         , 7
Up Type= 0
Dn Type= 3
Dn Slope=0.004
DSS Import GetInterval= 0
DSS Import GetPeak= 0
DSS Import FillOption= 0

--- UNT 123 IN UKCR.g01 (geometry) ---

Geom Title=Existing Conditions
Program Version=4.10

River Reach=UNT 123 IN UKCR ,Reach-1
Reach XY= 30
      3660072.72     10564803.05      3659870.25       10565255.
       3659869.5       10566787.        3660275.       10567827.
       3660332.5       10568229.      3660620.25       10568870.
        3661009.       10569295.       3661206.5       10569436.
      3661333.25       10569449.        3661617.       10569760.
      3661497.75       10570924.      3661162.75       10571350.
        3661068.       10571664.      3661215.25       10571918.
      3661264.75       10572162.        3661579.       10572390.
      3661960.75       10572942.      3662103.75       10572942.
       3662239.5       10573033.      3662462.25       10573025.
      3662683.25       10573159.       3662776.5       10573417.
        3662926.       10573521.       3662949.5       10573722.
      3662858.23     10573915.27       3662503.5       10574171.
      3662599.25       10574446.        3662551.       10574664.
        3662807.       10575416.       3662739.5       10575548.

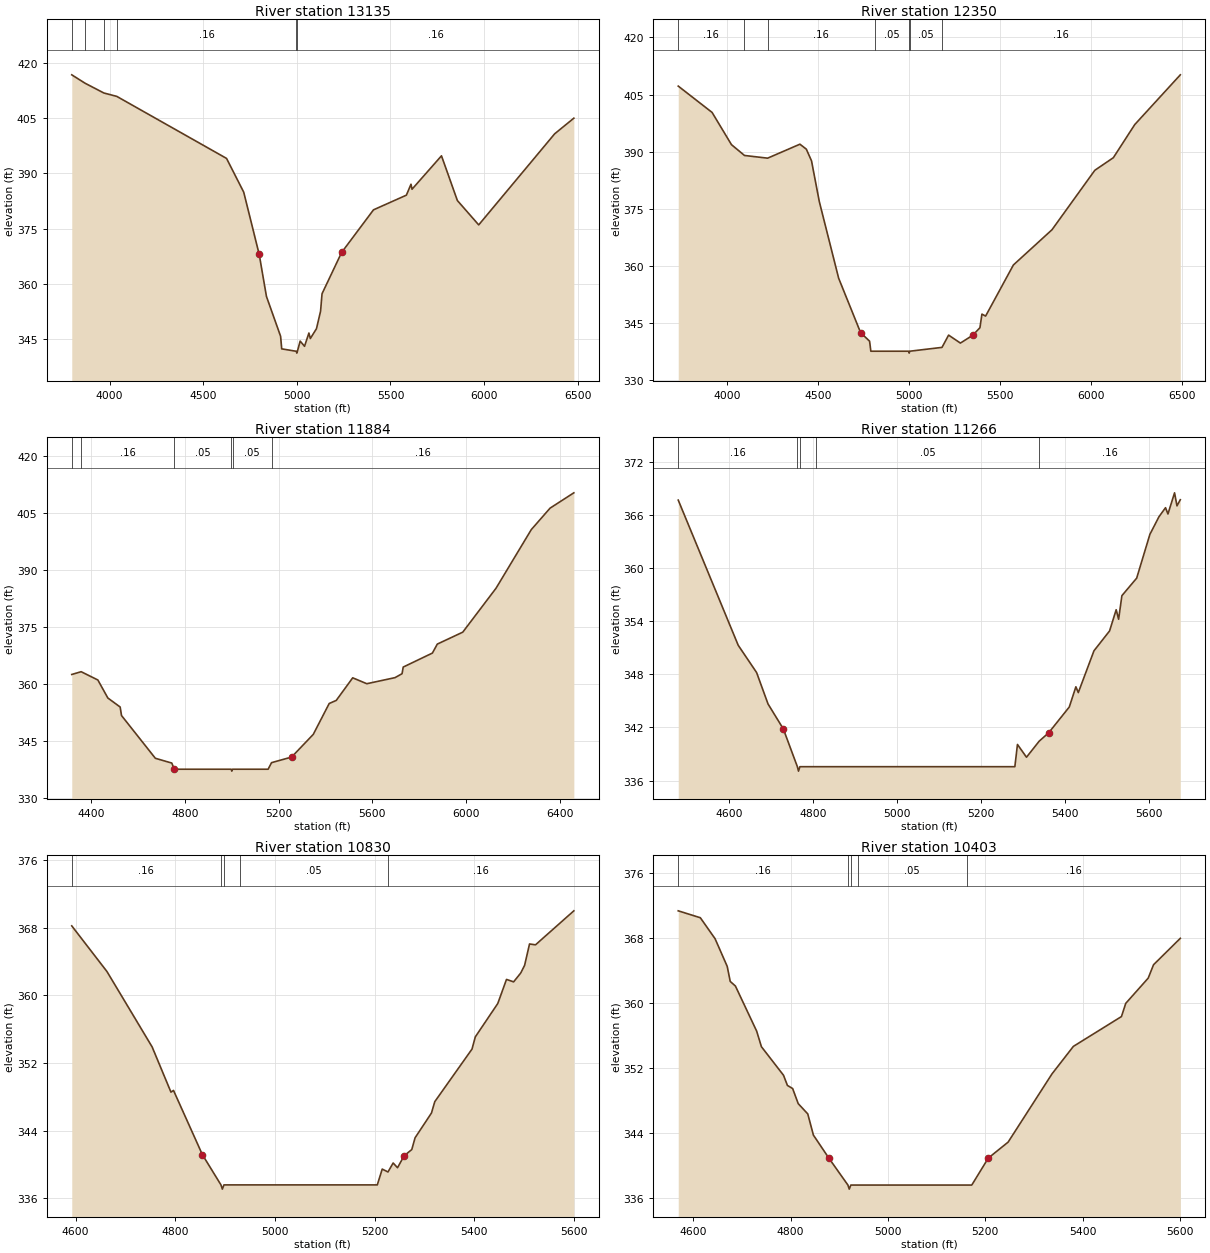
Type RM Length L Ch R = 1 ,13135   ,785,785,785
BEGIN DESCRIPTION:
UNT 123 IN UKCR 23.0
END DESCRIPTION:
XS GIS Cut Line= 5
      3658878.84     10564592.41      3659844.84     10564783.05
      3660361.77     10565009.61      3660743.28     10564863.78
      3661310.99      10565311.7
#Sta/Elev= 30
  3798.3  416.84  3869.4  414.55  3969.5   411.9  4038.8  410.97  4624.7  394.09
  4716.4   384.9  4799.1  367.96  4837.7  356.53  4913.3  345.68  4919.2  342.26
    4997   341.6  4999.8   341.1    5003   341.6  5017.7  344.37    5041  342.96
  5064.4  346.57    5072  345.07  5104.8  347.76  5126.6   352.5  5134.5  357.26
    5239  368.49  5409.3   380.1  5584.8  384.09  5609.5  387.07  5614.9   385.7
  5772.2   394.8  5857.1  382.63    5971     376  6376.6  400.79  6478.9  405.04
#Mann= 6 ,-1 , 0
  3798.3      .1       0  3869.4     .16       0  3969.5      .1       0
  4038.8     .16       0    4997     .07       0    5003     .16       0
Bank Sta=4799.1,5239
XS Rating Curve= 0 ,0
Exp/Cntr=0.3,0.1

Type RM Length L Ch R = 1 ,12350   ,466,466,466
BEGIN DESCRIPTION:
Mapping XS 304c0a22
END DESCRIPTION:
XS GIS Cut Line= 3
      3658852.64      10564884.6      3659644.32     10565577.32
      3661321.37      10565879.4
#Sta/Elev= 30
  3732.1  407.21    3918  400.29  4024.3  391.83  4095.7  388.99  4222.8  388.28
  4400.1  391.95  4435.3  390.64  4463.7  387.57  4506.4  376.89  4612.7  356.74
  4733.3  342.44  4782.4  340.21  4789.4  337.57  4811.8  337.57    4997  337.57
  4999.8  337.07    5003  337.57  5180.1  338.58  5216.2   341.8    5281  339.71
  5348.3  341.75  5388.2  343.74  5399.1  347.32  5419.4   346.8  5571.8  360.22
  5783.8  369.48  6018.9   385.1  6120.5   388.4    6238   397.1  6488.1  410.17
#Mann= 7 ,-1 , 0
  3732.1     .16       0  4095.7     .05       0  4222.8     .16       0
  4811.8     .05       0    4997    .033       0    5003     .05       0
  5180.1     .16       0
Bank Sta=4733.3,5348.3
XS Rating Curve= 0 ,0
Exp/Cntr=0.3,0.1

Type RM Length L Ch R = 1 ,11884   ,618,618,618
BEGIN DESCRIPTION:
Mapping XS f4c7049d
END DESCRIPTION:
XS GIS Cut Line= 4
      3659305.78     10566348.15      3659446.41     10566113.78
      3661185.99     10565978.36      3661311.01     10565973.15
#Sta/Elev= 30
  4316.7  362.49  4356.8  363.22  4428.1  361.04  4470.8   356.3  4523.3  353.93
  4529.1  351.69  4673.5  340.45  4743.7  339.19  4754.4  337.57    4997  337.57
  4999.8  337.07    5003  337.57  5154.9  337.57  5169.6   339.3  5255.2  340.77
  5347.7  346.74  5415.7  354.86  5445.8  355.67    5516  361.61  5576.2  360.06
  5696.6  361.66  5726.6  362.69  5731.6  364.44  5856.2  368.12  5877.1  370.48
  5985.8  373.62  6127.9  385.18  6278.3  400.59  6358.5  406.24    6460  410.27
#Mann= 6 ,-1 , 0
  4316.7     .05       0  4356.8     .16       0  4754.4     .05       0
    4997    .033       0    5003     .05       0  5169.6     .16       0
Bank Sta=4754.4,5255.2
XS Rating Curve= 0 ,0
Exp/Cntr=0.3,0.1

Type RM Length L Ch R = 1 ,11266   ,436,436,436
BEGIN DESCRIPTION:
UNT 123 IN UKCR 22.0
END DESCRIPTION:
XS GIS Cut Line= 3
      3659549.59     10567110.21      3659849.61     10566710.19
      3660449.65     10566360.17
#Sta/Elev= 30
    4479  367.67  4621.7  351.28  4665.5   348.2  4692.6  344.66    4729  341.84
  4762.5  337.57  4765.2  337.07  4768.5  337.57  4807.7  337.57    5280  337.57
  5286.2  340.08  5307.7  338.64  5337.7  340.44  5360.7  341.41  5409.5  344.31
  5425.2  346.59    5431  345.94  5468.2  350.65  5505.4   352.9  5521.1  355.29
  5526.9  354.22  5534.7  356.88  5569.9  358.86  5601.3   363.8  5622.8  365.78
  5638.5  366.81  5644.3   366.1    5660  368.49  5665.8  367.02  5673.7  367.71
#Mann= 5 ,-1 , 0
    4479     .16       0  4762.5    .033       0  4768.5     .16       0
  4807.7     .05       0  5337.7     .16       0
Bank Sta=4729,5360.7
XS Rating Curve= 0 ,0
Exp/Cntr=0.3,0.1

Type RM Length L Ch R = 1 ,10830   ,427,427,427
BEGIN DESCRIPTION:
UNT 123 IN UKCR 21.0
END DESCRIPTION:
XS GIS Cut Line= 3
      3659599.64     10567160.19      3659999.61     10567110.19
      3660549.57      10566860.2
#Sta/Elev= 30
  4592.5   368.2    4663  362.81  4753.7  353.89  4791.5  348.54  4796.6  348.74
  4854.5  341.15  4891.8  337.57  4894.6  337.07  4897.8  337.57    4929  337.57
  5205.4  337.57  5215.3  339.44  5226.9   339.1  5237.2  340.16    5246   339.6
  5259.2  341.01  5274.6  341.75  5281.2  343.14  5314.1  346.07  5320.7  347.41
  5395.4  353.63    5402  355.07  5447.1  359.02  5464.6  361.87  5478.9  361.58
  5493.2  362.63  5500.9  363.53  5510.8  366.06  5522.8  365.96  5599.7  369.98
#Mann= 5 ,-1 , 0
  4592.5     .16       0  4891.8    .033       0  4897.8     .16       0
    4929     .05       0  5226.9     .16       0
Bank Sta=4854.5,5259.2
XS Rating Curve= 0 ,0
Exp/Cntr=0.3,0.1

Type RM Length L Ch R = 1 ,10403   ,157,157,157
BEGIN DESCRIPTION:
UNT 123 IN UKCR 20.0
END DESCRIPTION:
XS GIS Cut Line= 3
       3659749.6     10567660.19      3660149.61     10567510.19
      3660699.65     10567260.17
#Sta/Elev= 30
  4569.2  371.29  4614.6  370.44  4644.9  367.86  4669.8  364.46    4676  362.61
  4686.7  362.04  4730.3   356.5  4740.1  354.58  4785.5  351.07  4793.5  349.82
  4804.2  349.44  4815.7  347.58  4835.3  346.32  4846.9  343.71  4878.9  340.86
  4917.8  337.57  4920.5  337.07  4923.8  337.57  4938.5  337.57  5161.4  337.57
  5172.2  337.57  5206.2  340.89  5246.9  342.85  5336.9  351.23  5380.9  354.62
  5479.7  358.29  5488.5  359.91  5534.7  363.02  5545.6  364.66  5600.6  367.91
#Mann= 5 ,-1 , 0
  4569.2     .16       0  4917.8    .033       0  4923.8     .16       0
  4938.5     .05       0  5161.4     .16       0
Bank Sta=4878.9,5206.2
XS Rating Curve= 0 ,0
Exp/Cntr=0.3,0.1

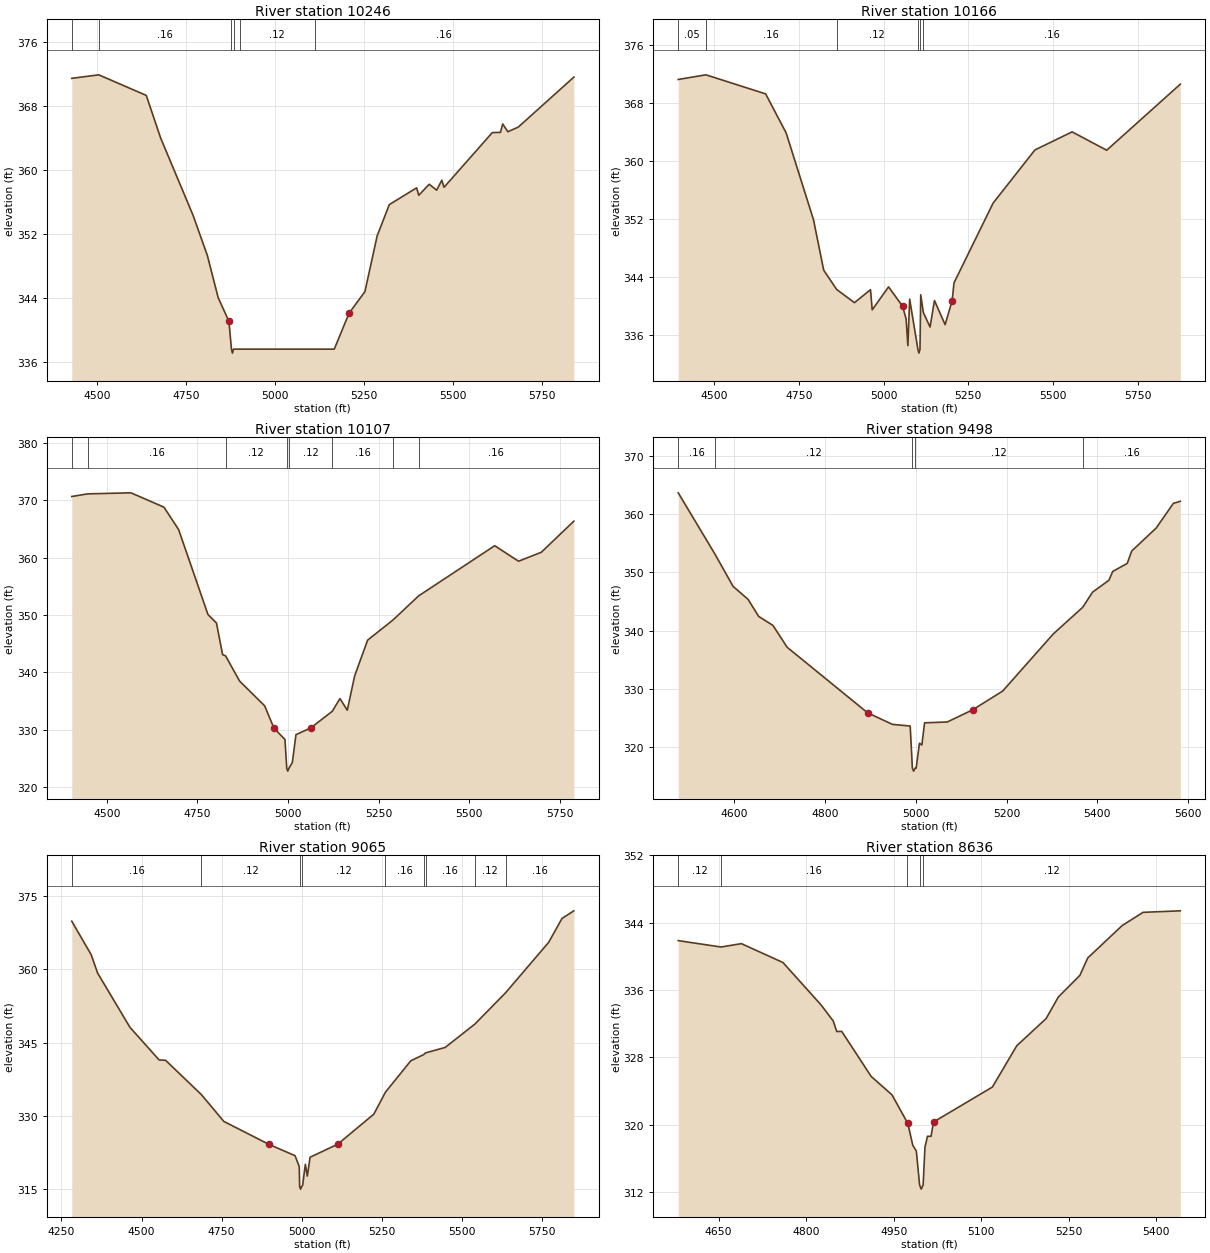
Type RM Length L Ch R = 1 ,10246   ,80,80,80
BEGIN DESCRIPTION:
Mapping XS e9b1c49b
END DESCRIPTION:
XS GIS Cut Line= 4
      3659642.24     10567735.42      3660258.52     10567648.62
      3660571.02     10567561.82       3660943.5     10567284.62
#Sta/Elev= 30
  4429.5   371.5  4505.4  371.94  4638.9  369.36  4679.3  364.02  4770.2  354.36
  4810.6   349.3  4840.9  344.03  4871.2  341.05  4878.3  337.57    4881  337.07
  4884.3  337.57  4901.3  337.57    5112  337.57  5167.2  337.57  5208.7  342.06
  5253.4  344.78  5287.7  351.75  5321.9  355.68  5398.6  357.78  5404.8  356.85
    5434  358.23  5454.9  357.49  5469.5  358.73  5475.7  357.85  5611.3   364.7
  5634.3  364.73  5640.5  365.78  5655.1  364.81  5684.3  365.39  5840.5  371.65
#Mann= 6 ,-1 , 0
  4429.5     .05       0  4505.4     .16       0  4878.3     .07       0
  4884.3     .16       0  4901.3     .12       0    5112     .16       0
Bank Sta=4871.2,5208.7
XS Rating Curve= 0 ,0
Exp/Cntr=0.3,0.1

Type RM Length L Ch R = 1 ,10166   ,59,59,59
BEGIN DESCRIPTION:
Mapping XS 65b2a7b2
END DESCRIPTION:
XS GIS Cut Line= 4
      3659633.54     10567804.87       3660267.2     10567726.75
      3660492.89      10567657.3      3661013.39       10567345.
#Sta/Elev= 30
  4394.2  371.23  4475.9  371.87  4652.2  369.24  4712.7  363.85  4793.3  351.89
  4823.5  344.92  4861.6  342.27  4914.2  340.44  4961.6  342.23  4966.6  339.45
  5014.9  342.62  5056.1  339.96  5066.6   338.2  5071.9  334.51  5077.1  340.93
  5101.6  333.98  5104.3  333.48  5107.6  333.98  5109.8  341.53  5117.6  339.07
  5137.3  337.08  5150.3  340.74  5181.7  337.41  5202.6  340.72  5207.9  343.16
  5323.3  354.17  5446.8  361.51  5556.5     364  5658.6  361.47  5875.8  370.58
#Mann= 6 ,-1 , 0
  4394.2     .05       0  4475.9     .16       0  4861.6     .12       0
  5101.6     .07       0  5107.6     .12       0  5117.6     .16       0
Bank Sta=5056.1,5202.6
XS Rating Curve= 0 ,0
Exp/Cntr=0.3,0.1

Type RM Length L Ch R = 1 ,10107   ,609,609,609
BEGIN DESCRIPTION:
UNT 123 IN UKCR 19.0
END DESCRIPTION:
XS GIS Cut Line= 3
      3659668.23     10567874.32      3660475.53     10567752.79
      3660944.26     10567431.62
#Sta/Elev= 30
  4403.6  370.64  4447.7   371.1  4566.8  371.28  4657.8  368.78  4698.3  364.87
  4779.2  350.06  4802.6  348.58  4819.6  343.05  4827.7  342.86  4866.6  338.44
  4935.5  334.14  4961.2  330.24  4991.5  328.27  4996.5  323.25  4999.2  322.75
  5002.5  323.25  5011.8  324.25  5021.9  329.11  5062.3  330.27  5122.1  333.19
  5143.2   335.4  5163.4  333.37  5183.7  339.36  5219.5  345.59  5288.8  349.07
  5360.4  353.32    5570  362.06  5635.7  359.35  5698.6  360.92  5788.2  366.34
#Mann= 8 ,-1 , 0
  4403.6     .05       0  4447.7     .16       0  4827.7     .12       0
  4996.5     .07       0  5002.5     .12       0  5122.1     .16       0
  5288.8     .12       0  5360.4     .16       0
Bank Sta=4961.2,5062.3
XS Rating Curve= 0 ,0
Exp/Cntr=0.3,0.1

Type RM Length L Ch R = 1 ,9498    ,433,433,433
BEGIN DESCRIPTION:
UNT 123 IN UKCR 18.0
END DESCRIPTION:
XS GIS Cut Line= 3
      3659899.58     10568210.18      3660399.61     10568360.19
      3660949.62     10568160.18
#Sta/Elev= 30
    4476  363.66  4557.2   353.1    4597  347.59    4630  345.36  4653.5  342.42
  4684.8  340.89  4716.2  337.13  4893.6  325.87  4948.5  323.88  4987.6   323.6
  4992.4  316.35  4995.2  315.85  4998.4  316.35  5000.7  316.35    5008  320.64
  5013.3  320.33  5019.3  324.15  5069.2  324.29  5125.1  326.37  5191.6  329.61
  5303.3  339.43    5368  343.99  5389.8   346.6  5425.7  348.63  5434.3  350.16
  5466.2  351.53  5476.2  353.67  5530.1  357.61    5568  361.85  5583.3  362.21
#Mann= 5 ,-1 , 0
    4476     .16       0  4557.2     .12       0  4992.4     .07       0
  4998.4     .12       0    5368     .16       0
Bank Sta=4893.6,5125.1
XS Rating Curve= 0 ,0
Exp/Cntr=0.3,0.1

Type RM Length L Ch R = 1 ,9065    ,429,429,429
BEGIN DESCRIPTION:
UNT 123 IN UKCR 17.0
END DESCRIPTION:
XS GIS Cut Line= 3
      3659849.64     10568860.18      3660549.61     10568760.19
       3661249.6     10568260.19
#Sta/Elev= 30
  4282.3  369.84  4342.9  362.98  4363.1   359.2  4464.1   348.1    4555  341.43
  4575.2  341.36  4686.9  334.34    4757  328.85  4898.5  324.13  4979.3  321.84
  4992.4   319.6  4993.7  315.49  4996.5  314.99  4999.7  315.49  5002.9  315.75
  5011.5  320.07  5017.6  317.66  5026.2  321.52  5112.3  324.18  5225.3  330.34
  5261.6  334.85  5340.8  341.27  5380.7  342.52  5386.6  342.88  5447.8  343.99
  5540.7  348.78  5636.6  355.19    5771  365.51  5812.7   370.4  5849.6  371.96
#Mann= 9 ,-1 , 0
  4282.3     .16       0  4686.9     .12       0  4993.7     .07       0
  4999.7     .12       0  5261.6     .16       0  5380.7     .12       0
  5386.6     .16       0  5540.7     .12       0  5636.6     .16       0
Bank Sta=4898.5,5112.3
XS Rating Curve= 0 ,0
Exp/Cntr=0.3,0.1

Type RM Length L Ch R = 1 ,8636    ,440,440,440
BEGIN DESCRIPTION:
UNT 123 IN UKCR 16.0
END DESCRIPTION:
XS GIS Cut Line= 3
      3660499.59      10569310.2      3660849.61     10569060.19
      3661099.64     10568710.15
#Sta/Elev= 30
  4580.8  341.88  4654.1  341.12    4689  341.52  4760.2  339.28  4825.4  334.25
  4846.3  332.34  4852.4  331.08    4861  331.09  4911.4  325.74    4947  323.56
  4973.2  320.28  4974.1  320.18  4982.7  317.56  4988.8  316.88  4994.4  312.85
  4997.2  312.35  5000.4  312.85  5003.6  317.34  5007.9  318.63    5014  318.63
  5018.3  320.33  5119.1  324.48  5160.9  329.39  5211.2  332.62  5232.1  335.18
    5269  337.75  5282.5  339.82  5341.5  343.67  5377.2  345.24  5441.1  345.42
#Mann= 5 ,-1 , 0
  4580.8     .12       0  4654.1     .16       0  4973.2     .12       0
  4994.4     .07       0  5000.4     .12       0
Bank Sta=4974.1,5018.3
XS Rating Curve= 0 ,0
Exp/Cntr=0.3,0.1

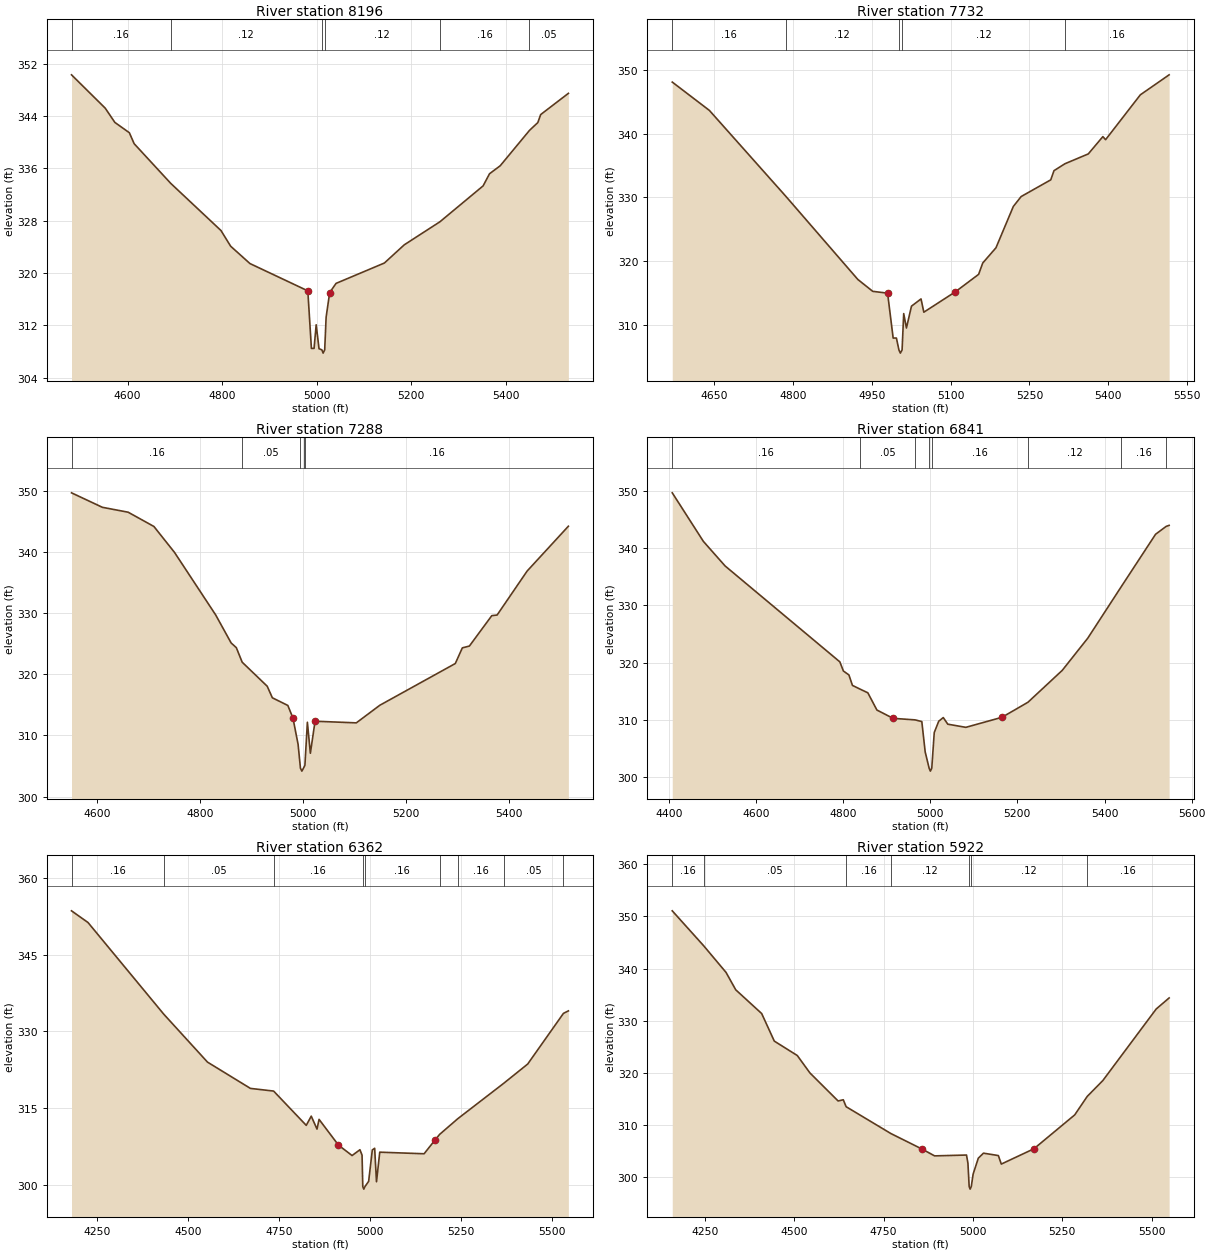
Type RM Length L Ch R = 1 ,8196    ,464,464,464
BEGIN DESCRIPTION:
UNT 123 IN UKCR 15.0
END DESCRIPTION:
XS GIS Cut Line= 3
      3660999.62     10569860.14      3661099.61     10569360.19
      3661549.62     10569060.18
#Sta/Elev= 30
  4481.4  350.28  4552.7  345.19  4573.1  343.01  4603.7  341.44  4613.9  339.76
  4691.3   333.7  4797.5   326.5  4817.9  324.11  4858.7  321.46  4981.1  317.29
  4988.7   308.5  4994.3   308.5  4998.8  312.11  5004.8  308.46  5010.8  308.28
  5013.5  307.78  5016.8  308.28  5019.8  313.26  5027.3  317.02  5040.8  318.43
    5143  321.54  5185.1  324.32  5260.5  327.84  5351.8  333.32  5365.3  335.17
  5387.9  336.39  5449.8  341.79  5467.5  342.99  5473.5  344.21  5532.1  347.45
#Mann= 6 ,-1 , 0
  4481.4     .16       0  4691.3     .12       0  5010.8     .07       0
  5016.8     .12       0  5260.5     .16       0  5449.8     .05       0
Bank Sta=4981.1,5027.3
XS Rating Curve= 0 ,0
Exp/Cntr=0.3,0.1

Type RM Length L Ch R = 1 ,7732    ,444,444,444
BEGIN DESCRIPTION:
UNT 123 IN UKCR 14.0
END DESCRIPTION:
XS GIS Cut Line= 3
      3661149.62     10569860.18      3661449.61     10569560.19
      3661599.62     10569060.16
#Sta/Elev= 30
  4569.7  348.12  4640.4  343.67  4785.7   330.2  4923.2   317.1  4951.5  315.24
  4979.8  314.95  4990.4   307.9  4996.6   307.9  5001.4  306.03  5004.1  305.53
  5007.4  306.03  5010.5  311.74  5015.7  309.48  5025.3  312.91  5043.5  314.05
  5048.8  311.96  5108.8  315.16  5153.2  317.91    5161  319.69  5186.2  322.08
  5219.3  328.58  5234.1  330.13  5290.6  332.76  5296.7   334.2  5317.6  335.29
    5362  336.83  5389.8  339.55    5395  339.07  5461.2  346.12    5516  349.26
#Mann= 5 ,-1 , 0
  4569.7     .16       0  4785.7     .12       0  5001.4     .07       0
  5007.4     .12       0  5317.6     .16       0
Bank Sta=4979.8,5108.8
XS Rating Curve= 0 ,0
Exp/Cntr=0.3,0.1

Type RM Length L Ch R = 1 ,7288    ,447,447,447
BEGIN DESCRIPTION:
UNT 123 IN UKCR 13.0
END DESCRIPTION:
XS GIS Cut Line= 3
      3661149.58     10569910.19      3661599.61     10569910.19
       3662049.6     10569660.19
#Sta/Elev= 30
    4550  349.67    4610   347.3    4660   346.5    4710  344.17    4750  339.93
    4830   329.7    4860  325.12    4870  324.36  4881.4  321.98    4930  318.05
    4940  316.16    4970  314.91    4980  312.85    4990  308.53  4994.5  304.67
  4997.3  304.17  5000.5  304.67  5003.2  305.11    5008  312.16  5013.8  307.09
  5022.9  312.33    5103  312.06  5148.7  314.94  5295.2  321.76  5308.9  324.32
  5322.6  324.62  5366.1  329.59  5376.4  329.69  5434.7  336.88  5514.8  344.21
#Mann= 5 ,-1 , 0
    4550     .16       0  4881.4     .05       0  4994.5     .03       0
  5000.5     .05       0  5003.2     .16       0
Bank Sta=4980,5022.9
XS Rating Curve= 0 ,0
Exp/Cntr=0.3,0.1

Type RM Length L Ch R = 1 ,6841    ,479,479,479
BEGIN DESCRIPTION:
UNT 123 IN UKCR 12.0
END DESCRIPTION:
XS GIS Cut Line= 3
      3661099.62      10570010.2      3661549.61     10570360.19
      3662099.65     10570210.18
#Sta/Elev= 30
  4408.1   349.6  4479.6  341.13  4529.3  336.86  4792.7  320.14  4800.8  318.55
  4813.5  317.86  4821.6  316.04  4839.4  315.38  4856.9  314.75  4877.7  311.75
  4914.8   310.3  4965.5  310.03  4980.8  309.73  4988.5  304.45  4997.6   301.6
  5000.4   301.1  5003.6   301.6  5009.3  307.82  5019.6   309.8    5030  310.43
  5040.4  309.28  5081.8  308.73  5164.7  310.48  5224.3   313.1  5302.9  318.65
  5361.7  324.28  5437.9  333.18  5517.2  342.38  5541.5  343.75  5548.3  343.93
#Mann= 8 ,-1 , 0
  4408.1     .16       0  4839.4     .05       0  4965.5     .16       0
  4997.6     .07       0  5003.6     .16       0  5224.3     .12       0
  5437.9     .16       0  5541.5     .05       0
Bank Sta=4914.8,5164.7
XS Rating Curve= 0 ,0
Exp/Cntr=0.3,0.1

Type RM Length L Ch R = 1 ,6362    ,440,440,440
BEGIN DESCRIPTION:
UNT 123 IN UKCR 11.0
END DESCRIPTION:
XS GIS Cut Line= 3
      3660799.61     10570410.19      3661499.61     10570810.19
      3662049.57      10570710.2
#Sta/Elev= 30
  4180.5  353.57  4225.8  351.29  4433.8  333.39  4554.1  324.01  4672.1  318.87
  4735.8  318.35  4825.5  311.65  4839.2  313.45    4855  310.92  4860.7  312.82
    4914  307.79  4951.4  305.75    4973  306.89  4978.8  305.82  4980.8  299.69
  4983.6  299.19  4986.8  299.69  4996.9  300.71    5007  306.85  5013.4  307.17
  5018.5  300.63  5027.4  306.41  5149.3   306.1  5178.6  308.73    5192  309.89
  5241.8  312.95  5367.9  319.86  5433.9  323.63  5532.1  333.53  5545.7  334.02
#Mann= 9 ,-1 , 0
  4180.5     .16       0  4433.8     .05       0  4735.8     .16       0
  4980.8     .07       0  4986.8     .16       0    5192     .12       0
  5241.8     .16       0  5367.9     .05       0  5532.1      .1       0
Bank Sta=4914,5178.6
XS Rating Curve= 0 ,0
Exp/Cntr=0.3,0.1

Type RM Length L Ch R = 1 ,5922    ,317,317,317
BEGIN DESCRIPTION:
UNT 123 IN UKCR 10.0
END DESCRIPTION:
XS GIS Cut Line= 3
      3660799.58     10570510.15      3661299.61     10571160.19
      3661649.61     10571610.19
#Sta/Elev= 30
  4158.9  351.07    4247  344.36  4309.4  339.27  4336.5  335.94  4409.1  331.39
  4444.4  326.11  4508.7  323.35  4544.1  320.01  4622.9  314.64  4637.4  314.87
  4645.4  313.54  4770.6   308.4  4857.6  305.43  4892.9  304.12  4982.2  304.28
  4986.2  302.69  4989.6  298.25  4992.3  297.75  4995.6  298.25  5000.7  300.63
  5015.2  303.68  5029.7  304.64  5071.3  304.18  5079.5  302.55  5170.8  305.48
  5284.9  311.97  5319.9  315.51  5363.6  318.55  5512.9  332.26  5549.1  334.38
#Mann= 7 ,-1 , 0
  4158.9     .16       0    4247     .05       0  4645.4     .16       0
  4770.6     .12       0  4989.6     .07       0  4995.6     .12       0
  5319.9     .16       0
Bank Sta=4857.6,5170.8
XS Rating Curve= 0 ,0
Exp/Cntr=0.3,0.1

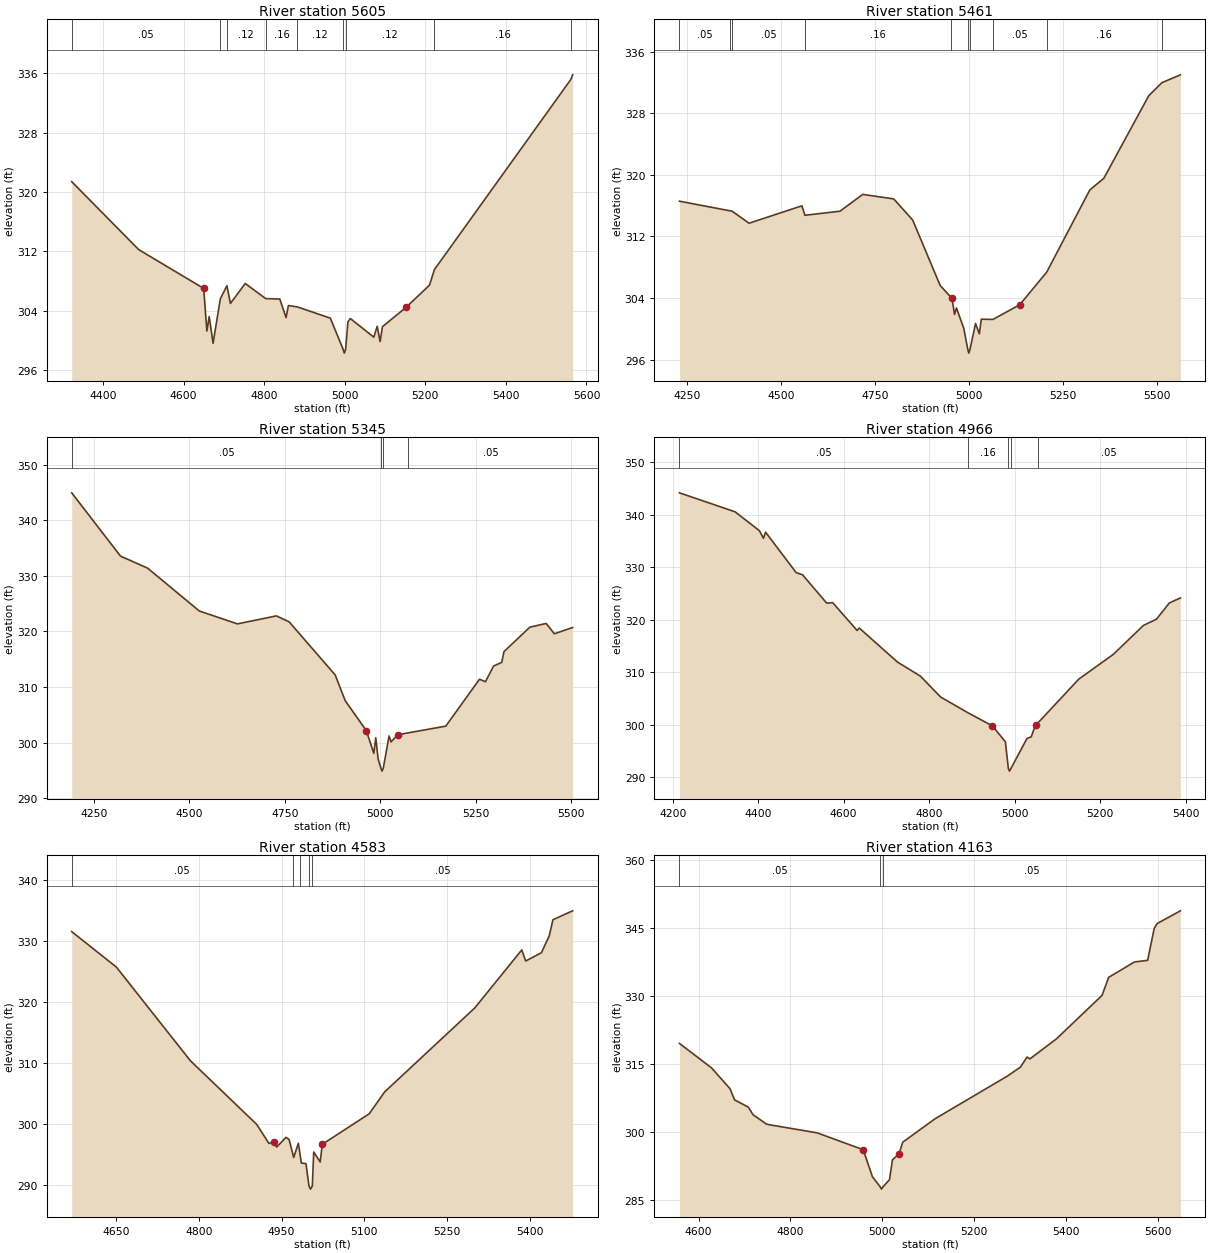
Type RM Length L Ch R = 1 ,5605    ,144,144,144
BEGIN DESCRIPTION:
Mapping XS c0617aca
END DESCRIPTION:
XS GIS Cut Line= 2
      3660548.14     10571082.28      3661616.32     10571719.29
#Sta/Elev= 30
    4322  321.39  4488.2  312.25  4649.7  307.02  4657.6  301.28  4663.4  303.23
    4673  299.64    4691  305.62  4707.4  307.38    4716     305  4752.9  307.68
  4803.6  305.65  4838.6  305.59  4854.2  303.09    4860  304.71  4881.7  304.54
  4964.1  303.02    4996  298.81  4998.8  298.31    5002  298.81  5007.9  302.54
  5013.7  302.97  5072.1  300.46  5080.5  301.92  5087.7  299.87  5093.5  301.87
  5151.9  304.46  5210.3  307.46  5222.6  309.56    5561  335.13  5565.7  335.77
#Mann= 9 ,-1 , 0
    4322     .05       0    4691     .16       0  4707.4     .12       0
  4803.6     .16       0  4881.7     .12       0    4996     .07       0
    5002     .12       0  5222.6     .16       0    5561     .05       0
Bank Sta=4649.7,5151.9
XS Rating Curve= 0 ,0
Exp/Cntr=0.3,0.1

Type RM Length L Ch R = 1 ,5461    ,116,116,116
BEGIN DESCRIPTION:
UNT 123 IN UKCR 9.0
END DESCRIPTION:
XS GIS Cut Line= 4
      3660325.82     10571574.39      3660887.99     10571507.13
      3661174.26     10571593.36      3661591.55       10571802.
#Sta/Elev= 30
    4230  316.58  4363.5  315.34  4369.5   315.3  4415.1  313.72  4555.5  315.98
  4563.6  314.75  4656.8  315.28  4717.2  317.46  4799.6  316.88  4850.1  314.13
  4923.1  305.63  4952.8  304.04  4954.5  303.98  4961.3  301.87  4966.5  302.71
  4985.9  300.06  4996.5  297.34  4999.3  296.84  5002.5  297.34  5017.2  300.69
  5027.3  299.35  5032.5  301.25  5063.6  301.22  5134.7  303.13  5206.3  307.36
    5321  318.04  5358.3  319.56  5477.5  330.27  5512.6  331.98  5561.7     333
#Mann= 10 ,-1 , 0
    4230     .05       0  4363.5     .08       0  4369.5     .05       0
  4563.6     .16       0  4952.8     .12       0  4996.5     .07       0
  5002.5     .12       0  5063.6     .05       0  5206.3     .16       0
  5512.6     .05       0
Bank Sta=4954.5,5134.7
XS Rating Curve= 0 ,0
Exp/Cntr=0.3,0.1

Type RM Length L Ch R = 1 ,5345    ,379,379,379
BEGIN DESCRIPTION:
UNT 123 IN UKCR 8.0
END DESCRIPTION:
XS GIS Cut Line= 5
      3660377.53     10571926.19       3660789.7     10571615.77
      3660956.97     10571646.81      3661143.22     10571696.82
      3661513.96     10571920.99
#Sta/Elev= 30
  4191.9  344.93  4319.7  333.55  4390.8  331.38  4526.1  323.68  4626.1  321.36
  4728.1   322.8  4761.6  321.72    4882  312.19  4908.5  307.53  4963.6  302.17
  4983.3  298.08  4988.4   300.9  4994.6  297.07    5002  295.38  5004.7  294.88
    5008  295.38  5023.3   301.2  5028.4  300.14  5046.4  301.42  5073.2  301.76
  5171.8  302.97  5260.2  311.41  5275.7  310.96  5297.1  313.78  5318.4  314.44
  5324.3  316.38  5392.1  320.77  5434.8  321.44  5456.2  319.58  5504.1  320.71
#Mann= 4 ,-1 , 0
  4191.9     .05       0    5002     .04       0    5008     .05       0
  5073.2     .05       0
Bank Sta=4963.6,5046.4
XS Rating Curve= 0 ,0
Exp/Cntr=0.3,0.1

Type RM Length L Ch R = 1 ,4966    ,383,383,383
BEGIN DESCRIPTION:
Mapping XS 5d725c5f
END DESCRIPTION:
XS GIS Cut Line= 2
      3660424.44      10572113.1        3661585.     10571950.41
#Sta/Elev= 30
  4215.8   344.2    4346  340.58  4402.8  336.99  4412.3  335.54  4417.4  336.69
  4488.8     329  4503.8  328.58  4560.1  323.19  4574.4  323.26  4631.5  317.97
  4636.5  318.43  4725.9  311.95  4779.2  309.28  4826.9  305.28  4889.8  302.33
  4948.1  299.77  4978.3  296.76  4985.3  291.66    4988  291.16  4991.3  291.66
  5028.8  297.38  5038.9  297.71    5049  300.04  5055.1   300.4    5150  308.69
  5230.8  313.41  5301.5  318.94  5331.8  320.12  5362.1  323.22  5387.7  324.17
#Mann= 5 ,-1 , 0
  4215.8     .05       0  4889.8     .16       0  4985.3     .07       0
  4991.3     .16       0  5055.1     .05       0
Bank Sta=4948.1,5049
XS Rating Curve= 0 ,0
Exp/Cntr=0.3,0.1

Type RM Length L Ch R = 1 ,4583    ,420,420,420
BEGIN DESCRIPTION:
UNT 123 IN UKCR 7.0
END DESCRIPTION:
XS GIS Cut Line= 3
      3661049.63     10572460.18      3661449.61     10572260.19
      3661749.63     10571910.16
#Sta/Elev= 30
  4569.5  331.48  4650.5  325.68  4784.7  310.36  4904.9  299.96  4927.2  296.83
  4935.6  297.12  4941.2  296.25    4958  297.84  4963.6  297.49  4969.9  295.29
    4972  294.55  4980.4  296.87    4983  295.34  4985.9  293.64  4994.3  293.53
  4999.7  289.87  5002.5  289.37  5005.7  289.87  5008.3  295.44    5020  293.81
  5023.8   296.7  5108.9  301.69  5136.9  305.27  5300.4  319.01  5385.5  328.49
  5392.6  326.67  5421.1  328.03  5435.4  330.81    5442  333.42  5477.7  334.88
#Mann= 5 ,-1 , 0
  4569.5     .05       0  4969.9     .16       0    4983     .05       0
  4999.7     .03       0  5005.7     .05       0
Bank Sta=4935.6,5023.8
XS Rating Curve= 0 ,0
Exp/Cntr=0.3,0.1

Type RM Length L Ch R = 1 ,4163    ,397,397,397
BEGIN DESCRIPTION:
UNT 123 IN UKCR 6.0
END DESCRIPTION:
XS GIS Cut Line= 3
      3661249.66     10572560.19      3661699.61     10572560.19
      3662099.63     10572060.16
#Sta/Elev= 30
  4558.4   319.5  4628.4  314.08  4668.4   309.5  4678.4  307.03  4708.4  305.41
  4718.4  303.76  4748.4  301.63  4858.4  299.73  4958.4  296.01  4978.4  290.04
  4995.4   287.8  4998.1   287.3  5001.4   287.8  5015.6   289.4    5022  293.77
  5036.4   295.1  5044.4  297.67  5114.8  302.85  5271.7  312.25  5300.5  314.25
  5314.9  316.48  5321.3  316.08  5378.9   320.5  5478.2  330.11  5492.6  334.09
  5548.6  337.49  5577.4  337.86  5591.8  344.92  5598.2  345.99  5648.7   348.8
#Mann= 3 ,-1 , 0
  4558.4     .05       0  4995.4     .03       0  5001.4     .05       0
Bank Sta=4958.4,5036.4
XS Rating Curve= 0 ,0
Exp/Cntr=0.3,0.1

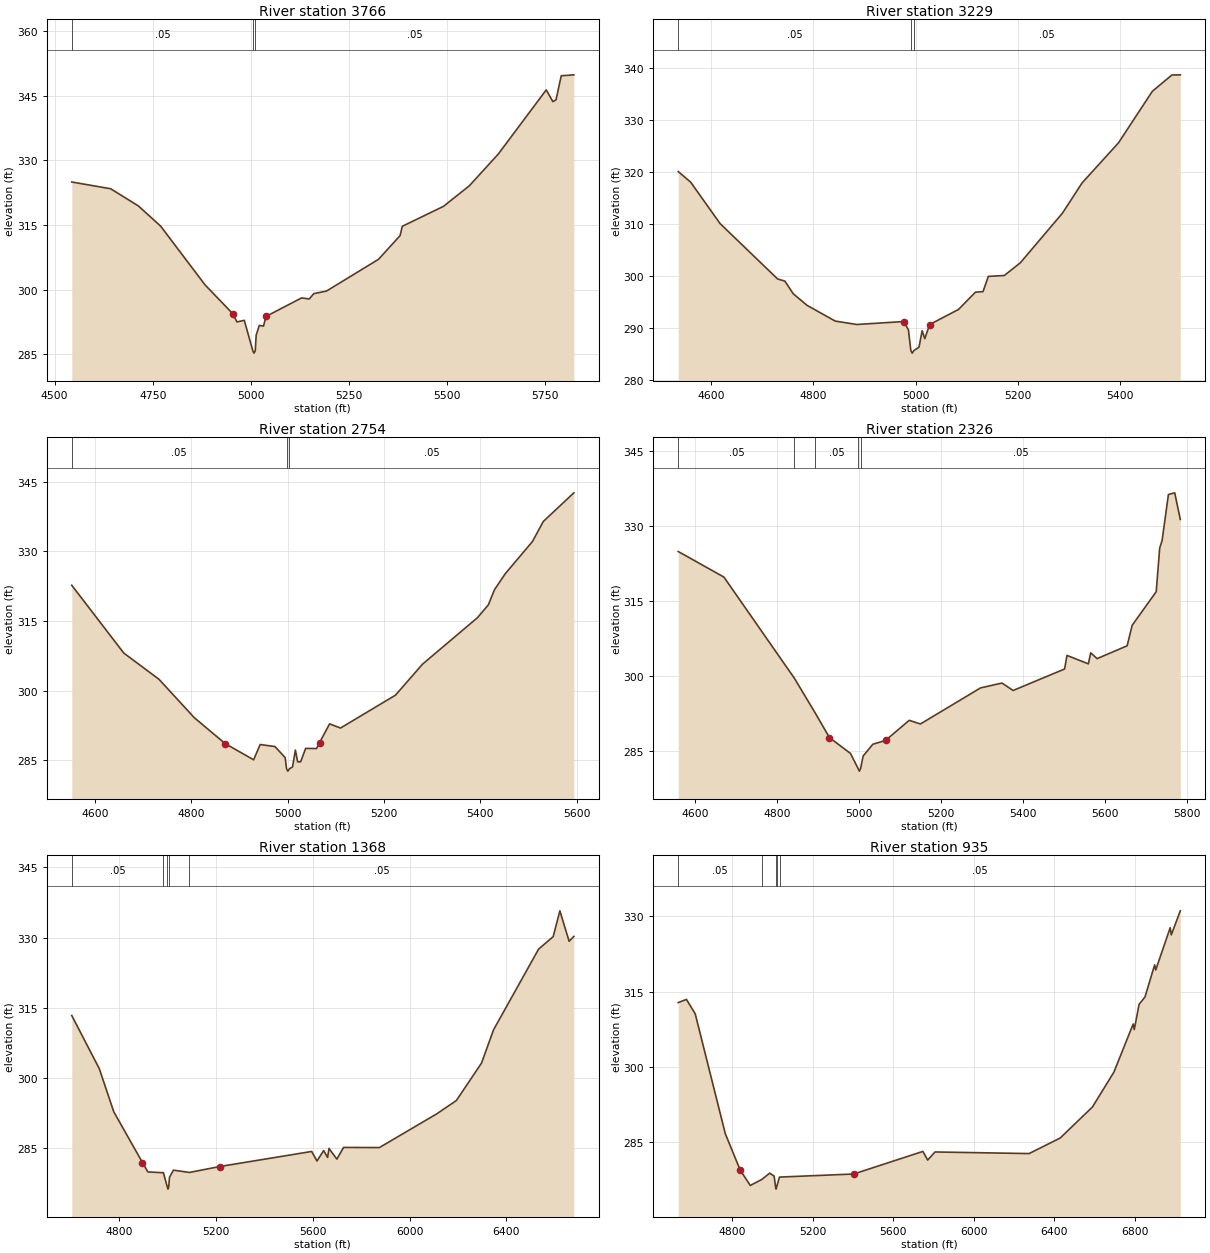
Type RM Length L Ch R = 1 ,3766    ,537,537,537
BEGIN DESCRIPTION:
UNT 123 IN UKCR 5.0
END DESCRIPTION:
XS GIS Cut Line= 3
       3661599.6      10573210.2      3661899.61     10572910.19
      3662199.62     10572110.16
#Sta/Elev= 30
  4543.8  324.96  4642.8   323.4  4713.5  319.41  4770.1  314.74  4883.2  301.12
  4953.9  294.43  4964.5  292.53  4983.2   292.9  5005.1   285.8  5007.9   285.3
  5011.1   285.8  5013.5   289.5  5021.5  291.73  5032.2  291.56  5038.4   293.8
  5129.2   298.1  5148.7  297.85  5160.3  299.09  5192.4  299.68    5325  307.04
  5380.1  312.55  5385.5  314.69  5490.5  319.32  5556.4  324.09  5630.2  331.45
  5752.2  346.31  5769.1  343.59  5777.1  344.02  5790.4  349.58  5822.5   349.8
#Mann= 3 ,-1 , 0
  4543.8     .05       0  5005.1     .03       0  5011.1     .05       0
Bank Sta=4953.9,5038.4
XS Rating Curve= 0 ,0
Exp/Cntr=0.3,0.1

Type RM Length L Ch R = 1 ,3229    ,475,475,475
BEGIN DESCRIPTION:
UNT 123 IN UKCR 4.0
END DESCRIPTION:
XS GIS Cut Line= 3
      3662249.62     10573460.16      3662349.61     10573010.19
      3662499.62     10572510.15
#Sta/Elev= 30
  4535.2  320.13  4559.5  318.09  4617.1  310.11  4729.8  299.43  4743.9  299.02
  4760.5  296.57  4787.4  294.35  4842.5  291.32  4884.7  290.66  4976.9  291.23
  4985.9  289.62  4990.6  285.64  4993.3  285.14  4996.6  285.64  5006.6  286.29
  5012.7  289.46  5017.9  287.93  5027.5  290.65    5084  293.56  5117.1  296.89
  5131.9  296.99  5142.3  299.93  5173.6   300.1    5205  302.55  5287.6  312.13
  5325.9  317.94  5397.2  325.67  5463.4  335.59  5501.6  338.73  5518.2  338.77
#Mann= 3 ,-1 , 0
  4535.2     .05       0  4990.6     .03       0  4996.6     .05       0
Bank Sta=4976.9,5027.5
XS Rating Curve= 0 ,0
Exp/Cntr=0.3,0.1

Type RM Length L Ch R = 1 ,2754    ,428,428,428
BEGIN DESCRIPTION:
UNT 123 IN UKCR 3.0
END DESCRIPTION:
XS GIS Cut Line= 3
      3662499.61     10573610.18      3662749.61     10573210.19
      3663099.62     10572760.17
#Sta/Elev= 30
  4552.1  322.66    4660  308.07  4733.1  302.42  4806.2  294.16  4870.5  288.56
  4929.5  285.08    4943  288.37  4973.7  287.93  4994.9  285.55  4997.8  283.14
  5000.5  282.64  5003.8  283.14  5010.2  283.56  5016.1  287.17  5020.8  284.64
    5027  284.64  5037.4  287.54    5060   287.5  5066.3  288.78  5087.1  292.82
  5109.8  291.92  5223.8     299  5279.9  305.67  5393.9  315.68  5416.5  318.44
  5429.2   321.7  5451.8  325.18  5507.9  332.07  5530.5   336.4  5593.9  342.57
#Mann= 3 ,-1 , 0
  4552.1     .05       0  4997.8     .03       0  5003.8     .05       0
Bank Sta=4870.5,5066.3
XS Rating Curve= 0 ,0
Exp/Cntr=0.3,0.1

Type RM Length L Ch R = 1 ,2326    ,958,958,958
BEGIN DESCRIPTION:
UNT 123 IN UKCR 2.0
END DESCRIPTION:
XS GIS Cut Line= 3
      3662499.63     10573660.18      3662949.61     10573560.19
      3663349.62     10572910.16
#Sta/Elev= 30
  4558.6  324.87    4670  319.77  4841.9  299.59  4892.4   292.7  4927.4  287.76
  4978.6  284.61  4997.3  281.58  5000.1  281.08  5003.3  281.58  5009.3  284.07
  5033.1  286.44    5064   287.2  5121.9  291.21  5149.1  290.48  5295.9  297.68
    5348  298.64  5375.1  297.16  5500.6  301.44  5506.5  304.15  5558.6  302.47
  5564.4  304.67  5579.9  303.51  5653.2  306.07  5665.4  310.16  5724.1  316.86
  5732.5  325.55  5738.4  327.06  5753.8  336.23  5769.2  336.57  5782.8  331.26
#Mann= 5 ,-1 , 0
  4558.6     .05       0  4841.9      .1       0  4892.4     .05       0
  4997.3     .03       0  5003.3     .05       0
Bank Sta=4927.4,5064
XS Rating Curve= 0 ,0
Exp/Cntr=0.3,0.1

Type RM Length L Ch R = 1 ,1368    ,433,433,433
BEGIN DESCRIPTION:
Mapping XS 697b2818
END DESCRIPTION:
XS GIS Cut Line= 3
      3662194.78     10574457.27      3662875.34     10574113.52
      3663493.39     10572957.28
#Sta/Elev= 30
  4605.1  313.32  4718.8  301.94  4778.6  292.72  4897.1  281.86  4919.4  279.85
  4983.5  279.68  4999.6  276.67  5002.4  276.17  5005.6  276.67  5008.6  278.69
    5025  280.23  5091.3  279.74  5215.5     281  5595.9  284.23  5617.8  282.19
  5645.4  284.42  5661.7  282.95  5667.4  284.88  5699.9  282.59  5727.6  285.09
  5875.5  285.06  6111.2  292.24  6193.3  295.12  6297.4  303.15    6347  310.26
  6533.1  327.53  6593.3   330.2  6620.9  335.72  6659.1  329.21  6678.6  330.24
#Mann= 5 ,-1 , 0
  4605.1     .05       0  4983.5     .16       0  4999.6     .07       0
  5005.6     .16       0  5091.3     .05       0
Bank Sta=4897.1,5215.5
XS Rating Curve= 0 ,0
Exp/Cntr=0.3,0.1

Type RM Length L Ch R = 1 ,935     ,509,509,509
BEGIN DESCRIPTION:
Mapping XS b0c572c0
END DESCRIPTION:
XS GIS Cut Line= 4
      3662162.87     10574569.81      3662392.02     10574746.89
       3662876.4     10574590.64      3663521.78     10573024.02
#Sta/Elev= 30
  4533.3  312.85  4574.1  313.48  4617.6  310.62    4767  286.74  4841.4  279.46
  4891.1  276.43  4948.6  277.63  4987.3  278.88  5009.5   278.3  5016.3   276.2
  5019.1   275.7  5022.3   276.2  5036.1   278.1  5404.3  278.71    5748  283.21
  5771.9  281.49  5808.2   283.1  6275.5  282.78  6429.9  285.88  6589.8  292.05
  6696.4  298.99  6792.2  308.58  6797.6  307.48  6821.5  312.49  6850.9  313.97
  6898.8  320.36  6904.2  319.34    6976  327.76  6981.4  326.33  7026.2  331.12
#Mann= 5 ,-1 , 0
  4533.3     .05       0  4948.6     .07       0  5016.3     .07       0
  5022.3     .07       0  5036.1     .05       0
Bank Sta=4841.4,5404.3
XS Rating Curve= 0 ,0
Exp/Cntr=0.3,0.1

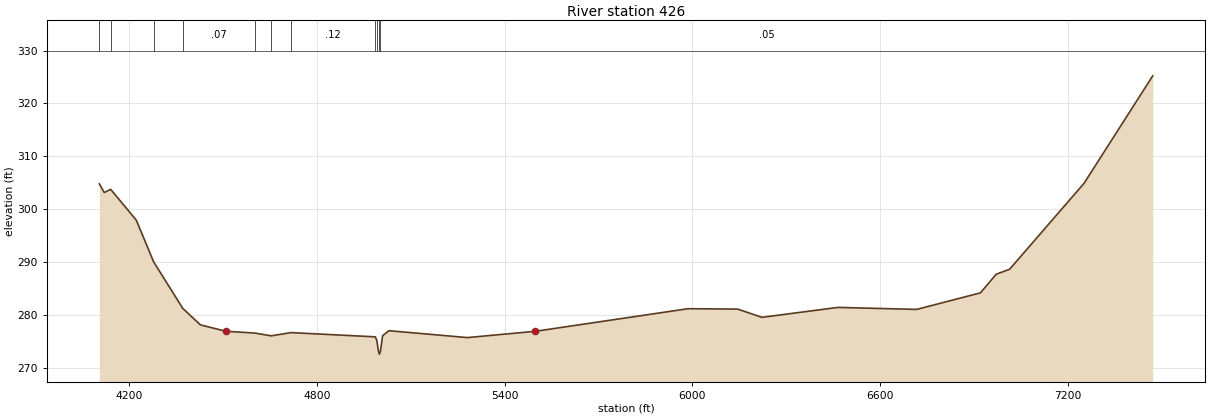
Type RM Length L Ch R = 1 ,426     ,0,0,0
BEGIN DESCRIPTION:
UNT 123 IN UKCR 1.0
END DESCRIPTION:
XS GIS Cut Line= 4
      3662126.41     10574632.33       3662438.9     10575184.39
      3662897.23     10575173.97      3663647.22     10573028.18
#Sta/Elev= 30
  4105.3  304.77    4121  303.14  4141.6  303.73  4223.5   297.9    4279     290
  4372.1   281.2  4428.4  278.09  4509.2  276.89  4602.6  276.54  4654.8  276.02
  4717.8  276.63  4987.1  275.83    4992  275.13  4997.4  273.06  5000.2  272.56
  5003.4  273.06  5010.4  276.03  5030.4  276.99  5281.3  275.69  5498.7  276.88
    5986  281.15  6144.9  281.08  6222.5  279.52  6465.6   281.4    6717  281.02
  6920.6  284.15  6971.2  287.68  7013.8  288.61  7251.5  304.86  7471.2  325.21
#Mann= 11 ,-1 , 0
  4105.3     .05       0  4141.6     .07       0    4279     .05       0
  4372.1     .07       0  4602.6     .05       0  4654.8     .07       0
  4717.8     .12       0  4987.1     .07       0    4992     .05       0
  4997.4     .03       0  5003.4     .05       0
Bank Sta=4509.2,5498.7
XS Rating Curve= 0 ,0
Exp/Cntr=0.3,0.1

Chan Stop Cuts=-1
Use User Specified Reach Order=0
Composite Channel Slope=5