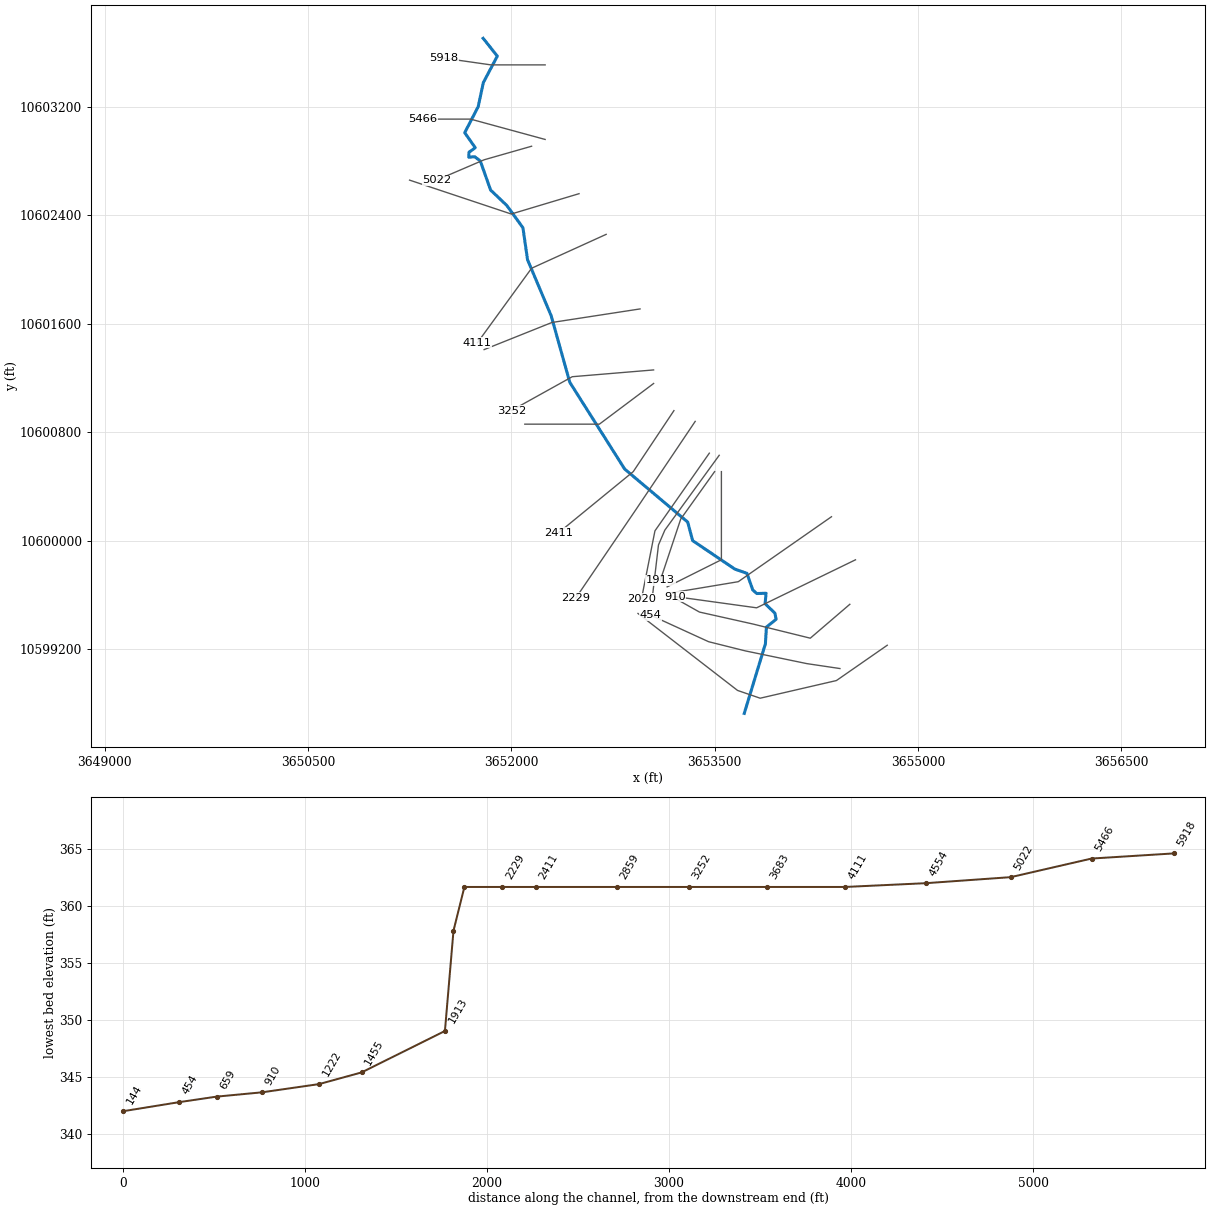
--- UNT 124 IN UKCR.prj (project) ---

Proj Title=UNT 124 IN UKCR Base Level Engineering
Current Plan=p01
Default Exp/Contr=0.3,0.1
English Units
Geom File=g01
Flow File=f01
Plan File=p01
BEGIN DESCRIPTION:
UNT 124 IN UKCR
END DESCRIPTION:

--- UNT 124 IN UKCR.p01 (plan) ---

Plan Title=Multiple Run
Short Identifier=Multiple
Geom File=g01
Flow File=f01
Subcritical Flow
K Sum by GR= 0
Std Step Tol= 0.01
Critical Tol= 0.01
Num of Std Step Trials= 20
Max Error Tol= 0.3
Flow Tol Ratio= 0.001
Split Flow NTrial= 30
Split Flow Tol= 0.02
Split Flow Ratio= 0.02
Log Output Level= 0
Friction Slope Method= 1
Unsteady Friction Slope Method= 2
Unsteady Bridges Friction Slope Method= 1
Parabolic Critical Depth
Global Vel Dist=  1 , 1 , 1
Global Log Level= 0
CheckData=True
Encroach Param= -1, 0, 0, 0
BEGIN DESCRIPTION:
Multiple Run
END DESCRIPTION:

--- UNT 124 IN UKCR.f01 (steady flow) ---

Flow Title=Multiple
Number of Profiles=7
Profile Names=10-year,25-year,50-year,1pct_min,100-year,1pct_plu,500-year
River Rch & RM= UNT 124 IN UKCR,Reach-1,5918
     683     939    1155    1043    1411    1908    2116
River Rch & RM= UNT 124 IN UKCR,Reach-1,4111
     796    1101    1357    1228    1660    2245    2498
Boundary for River Rch & Prof#=UNT 124 IN UKCR,Reach-1,1
Up Type=0
Dn Type=3
Dn Slope=0.005
Boundary for River Rch & Prof#=UNT 124 IN UKCR,Reach-1,2
Up Type=0
Dn Type=3
Dn Slope=0.005
Boundary for River Rch & Prof#=UNT 124 IN UKCR,Reach-1,3
Up Type=0
Dn Type=3
Dn Slope=0.005
Boundary for River Rch & Prof#=UNT 124 IN UKCR,Reach-1,4
Up Type=0
Dn Type=3
Dn Slope=0.005
Boundary for River Rch & Prof#=UNT 124 IN UKCR,Reach-1,5
Up Type=0
Dn Type=3
Dn Slope=0.005
Boundary for River Rch & Prof#=UNT 124 IN UKCR,Reach-1,6
Up Type=0
Dn Type=3
Dn Slope=0.005
Boundary for River Rch & Prof#=UNT 124 IN UKCR,Reach-1,7
Up Type=0
Dn Type=3
Dn Slope=0.005

--- UNT 124 IN UKCR.g01 (geometry) ---

Geom Title=Existing Conditions

River Reach=UNT 124 IN UKCR,Reach-1
Reach XY= 30
      3651792.50     10603706.00      3651896.75     10603575.00
      3651793.50     10603379.00      3651755.75     10603202.00
      3651656.25     10603010.00      3651734.25     10602899.00
      3651688.00     10602866.00      3651686.25     10602829.00
      3651729.75     10602833.00      3651771.50     10602801.00
      3651847.25     10602587.00      3651966.00     10602474.00
      3652085.75     10602309.00      3652119.75     10602073.00
      3652294.00     10601660.00      3652431.25     10601169.00
      3652836.25     10600529.00      3653301.00     10600138.00
      3653337.50     10600001.00      3653649.00     10599791.00
      3653737.75     10599760.00      3653781.00     10599637.00
      3653810.25     10599611.00      3653879.00     10599613.00
      3653872.00     10599536.00      3653944.25     10599466.00
      3653953.25     10599421.00      3653881.50     10599363.00
      3653874.25     10599240.00      3653718.25     10598727.00

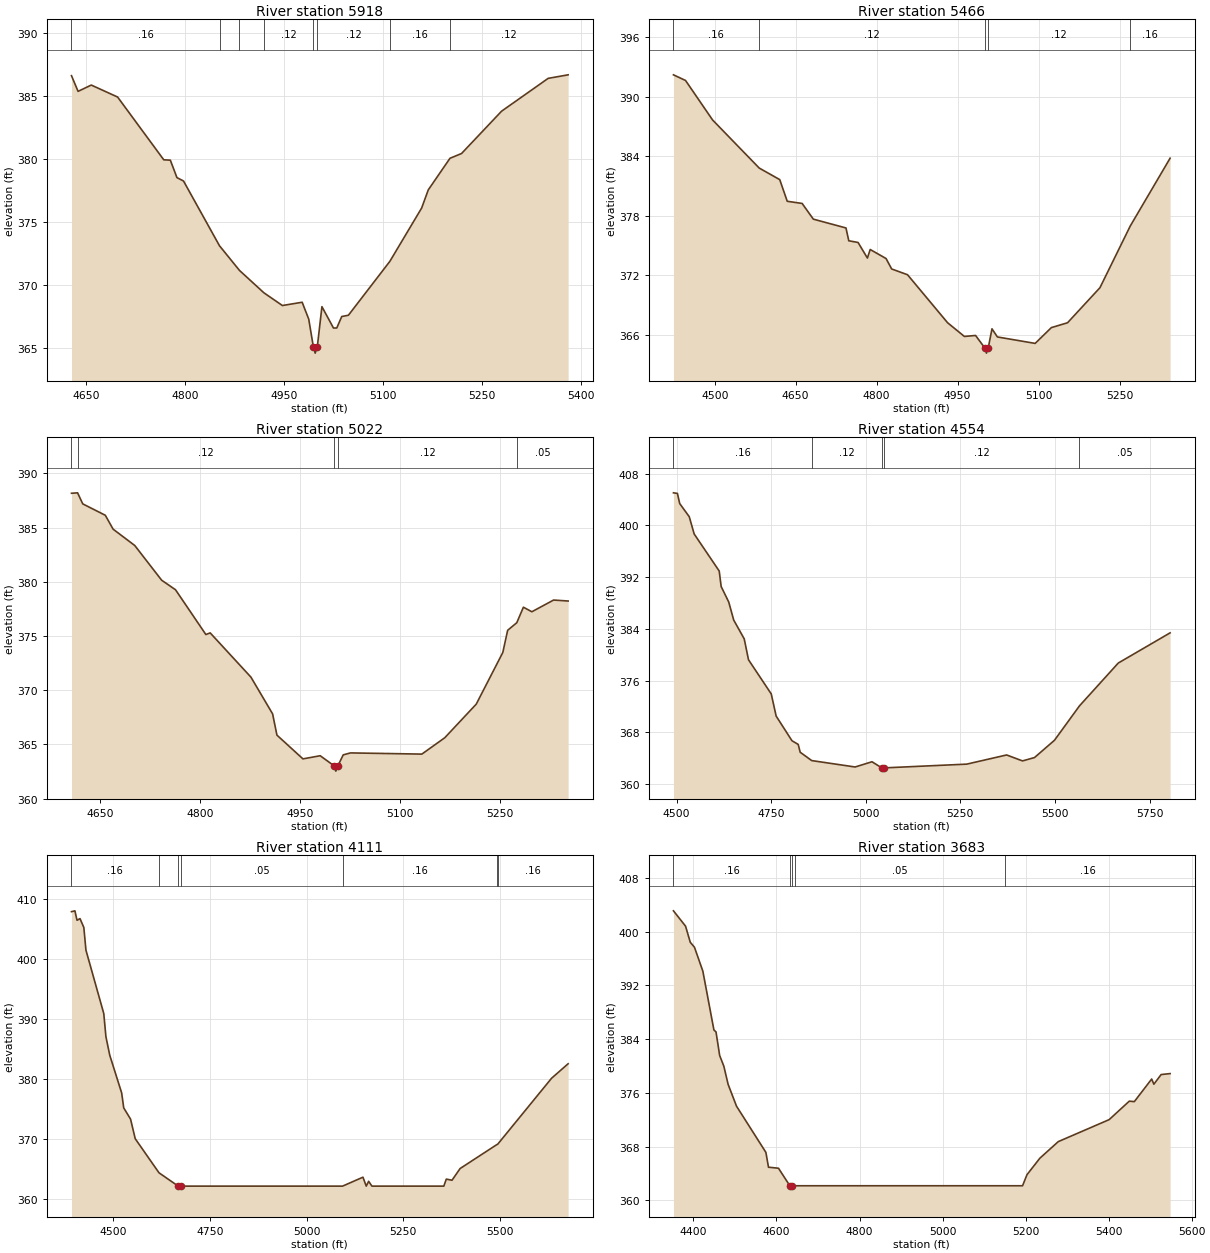
Type RM Length L Ch R = 1,5918,452,452,452
BEGIN DESCRIPTION:
UNT 124 IN UKCR 13.0
END DESCRIPTION:
XS GIS Cut Line= 3
      3652249.62     10603510.19      3651849.61     10603510.19
      3651499.58     10603560.19
#Sta/Elev= 30
  4627.4  386.58  4637.4  385.34  4657.4  385.84  4697.4  384.89  4767.4  379.92
  4777.4  379.89  4787.4  378.51  4797.4  378.24  4852.0  373.11  4882.3  371.16
  4919.3  369.39  4947.4  368.38  4977.4  368.64  4987.4  367.30  4994.4  365.11
  4997.2  364.61  5000.4  365.11  5007.4  368.29  5024.9  366.60  5029.9  366.60
  5037.5  367.51  5047.6  367.61  5110.5  371.88  5158.7  376.10  5168.8  377.54
  5201.7  380.04  5219.3  380.42  5280.0  383.77  5350.7  386.37  5381.0  386.65
#Mann=8,-1,0
  4627.4    0.16       0  4852.0    0.12       0  4882.3    0.16       0
  4919.3    0.12       0  4994.4    0.07       0  5000.4    0.12       0
  5110.5    0.16       0  5201.7    0.12       0
Bank Sta=4994.4,5000.4
Exp/Cntr=0.3,0.1

Type RM Length L Ch R = 1,5466,444,444,444
BEGIN DESCRIPTION:
UNT 124 IN UKCR 12.0
END DESCRIPTION:
XS GIS Cut Line= 3
      3652249.60     10602960.19      3651699.61     10603110.19
      3651349.59     10603110.19
#Sta/Elev= 30
  4423.6  392.20  4446.0  391.63  4496.1  387.65  4582.4  382.81  4620.5  381.64
  4634.4  379.46  4662.0  379.24  4682.7  377.66  4743.2  376.77  4748.4  375.48
  4765.6  375.31  4782.9  373.74  4788.1  374.60  4817.5  373.69  4827.8  372.64
  4857.2  372.06  4931.5  367.22  4962.6  365.84  4983.3  365.94  5000.7  364.66
  5003.4  364.16  5006.7  364.66  5013.7  366.61  5023.7  365.79  5093.7  365.14
  5123.7  366.73  5153.7  367.22  5213.7  370.75  5269.9  376.97  5343.7  383.80
#Mann=5,-1,0
  4423.6    0.16       0  4582.4    0.12       0  5000.7    0.07       0
  5006.7    0.12       0  5269.9    0.16       0
Bank Sta=5000.7,5006.7
Exp/Cntr=0.3,0.1

Type RM Length L Ch R = 1,5022,468,468,468
BEGIN DESCRIPTION:
UNT 124 IN UKCR 11.0
END DESCRIPTION:
XS GIS Cut Line= 3
      3652149.58     10602910.18      3651799.61     10602810.19
      3651449.58     10602660.17
#Sta/Elev= 30
  4606.9  388.16  4616.0  388.20  4623.8  387.18  4657.6  386.13  4669.3  384.85
  4701.8  383.34  4742.1  380.14  4762.9  379.26  4808.4  375.13  4814.9  375.28
  4876.0  371.20  4908.5  367.81  4915.0  365.85  4954.0  363.66  4979.9  363.95
  5000.5  363.03  5003.3  362.53  5006.5  363.03  5014.4  364.03  5025.3  364.21
  5132.3  364.10  5166.7  365.61  5213.9  368.71  5253.7  373.47  5261.0  375.52
  5274.7  376.22  5284.6  377.65  5297.3  377.23  5329.9  378.31  5351.7  378.22
#Mann=5,-1,0
  4606.9    0.16       0  4616.0    0.12       0  5000.5    0.07       0
  5006.5    0.12       0  5274.7    0.05       0
Bank Sta=5000.5,5006.5
Exp/Cntr=0.3,0.1

Type RM Length L Ch R = 1,4554,443,443,443
BEGIN DESCRIPTION:
UNT 124 IN UKCR 10.0
END DESCRIPTION:
XS GIS Cut Line= 3
      3652499.57     10602560.18      3651999.61     10602410.19
      3651249.65     10602660.17
#Sta/Elev= 30
  4491.9  405.03  4502.3  404.94  4508.4  403.37  4533.6  401.34  4546.7  398.66
  4612.8  392.94  4618.0  390.54  4638.0  388.14  4651.1  385.36  4678.9  382.45
  4690.2  379.22  4750.3  373.94  4763.3  370.51  4805.1  366.70  4821.6  366.13
  4826.8  364.92  4857.3  363.63  4972.1  362.64  5016.5  363.45  5042.5  362.50
  5045.2  362.00  5048.5  362.50  5266.9  363.08  5372.3  364.50  5414.4  363.58
  5446.1  364.10  5498.8  366.77  5564.9  372.09  5667.4  378.71  5804.4  383.38
#Mann=5,-1,0
  4491.9    0.16       0  4857.3    0.12       0  5042.5    0.07       0
  5048.5    0.12       0  5564.9    0.05       0
Bank Sta=5042.5,5048.5
Exp/Cntr=0.3,0.1

Type RM Length L Ch R = 1,4111,428,428,428
BEGIN DESCRIPTION:
UNT 124 IN UKCR 9.0
END DESCRIPTION:
XS GIS Cut Line= 3
      3652699.64     10602260.20      3652149.61     10602010.19
      3651749.59     10601460.16
#Sta/Elev= 30
  4392.2  407.90  4401.0  408.04  4406.5  406.47  4414.2  406.74  4424.1  405.27
  4429.6  401.48  4475.7  390.92  4481.2  387.08  4491.1  383.99  4521.9  377.70
  4527.3  375.20  4544.9  373.34  4557.0  370.07  4618.5  364.39  4668.2  362.17
  4671.0  361.67  4674.2  362.17  5093.2  362.17  5145.9  363.66  5154.4  362.17
  5160.6  362.97  5169.1  362.17  5355.0  362.17  5361.5  363.34  5376.2  363.15
  5397.1  365.10  5491.7  369.07  5494.3  369.15  5633.6  380.14  5676.5  382.56
#Mann=7,-1,0
  4392.2    0.16       0  4618.5    0.05       0  4668.2   0.033       0
  4674.2    0.05       0  5093.2    0.16       0  5491.7    0.12       0
  5494.3    0.16       0
Bank Sta=4668.2,4674.2
Exp/Cntr=0.3,0.1

Type RM Length L Ch R = 1,3683,431,431,431
BEGIN DESCRIPTION:
UNT 124 IN UKCR 8.0
END DESCRIPTION:
XS GIS Cut Line= 3
      3652949.63     10601710.19      3652299.61     10601610.19
      3651799.60     10601410.18
#Sta/Elev= 30
  4351.9  403.08  4381.0  400.80  4392.4  398.40  4402.5  397.66  4422.7  394.10
  4449.3  385.36  4454.4  385.06  4463.2  381.55  4473.3  379.95  4483.5  377.27
  4503.7  374.02  4574.5  367.14  4580.8  364.93  4604.9  364.78  4632.2  362.17
  4635.0  361.67  4638.2  362.17  4644.9  362.17  5149.6  362.17  5192.7  362.17
  5203.4  363.82  5234.4  366.27  5278.8  368.74  5401.3  372.01  5449.8  374.76
  5461.9  374.69  5503.7  378.05  5509.0  377.28  5526.5  378.72  5548.1  378.86
#Mann=5,-1,0
  4351.9    0.16       0  4632.2   0.033       0  4638.2    0.16       0
  4644.9    0.05       0  5149.6    0.16       0
Bank Sta=4632.2,4638.2
Exp/Cntr=0.3,0.1

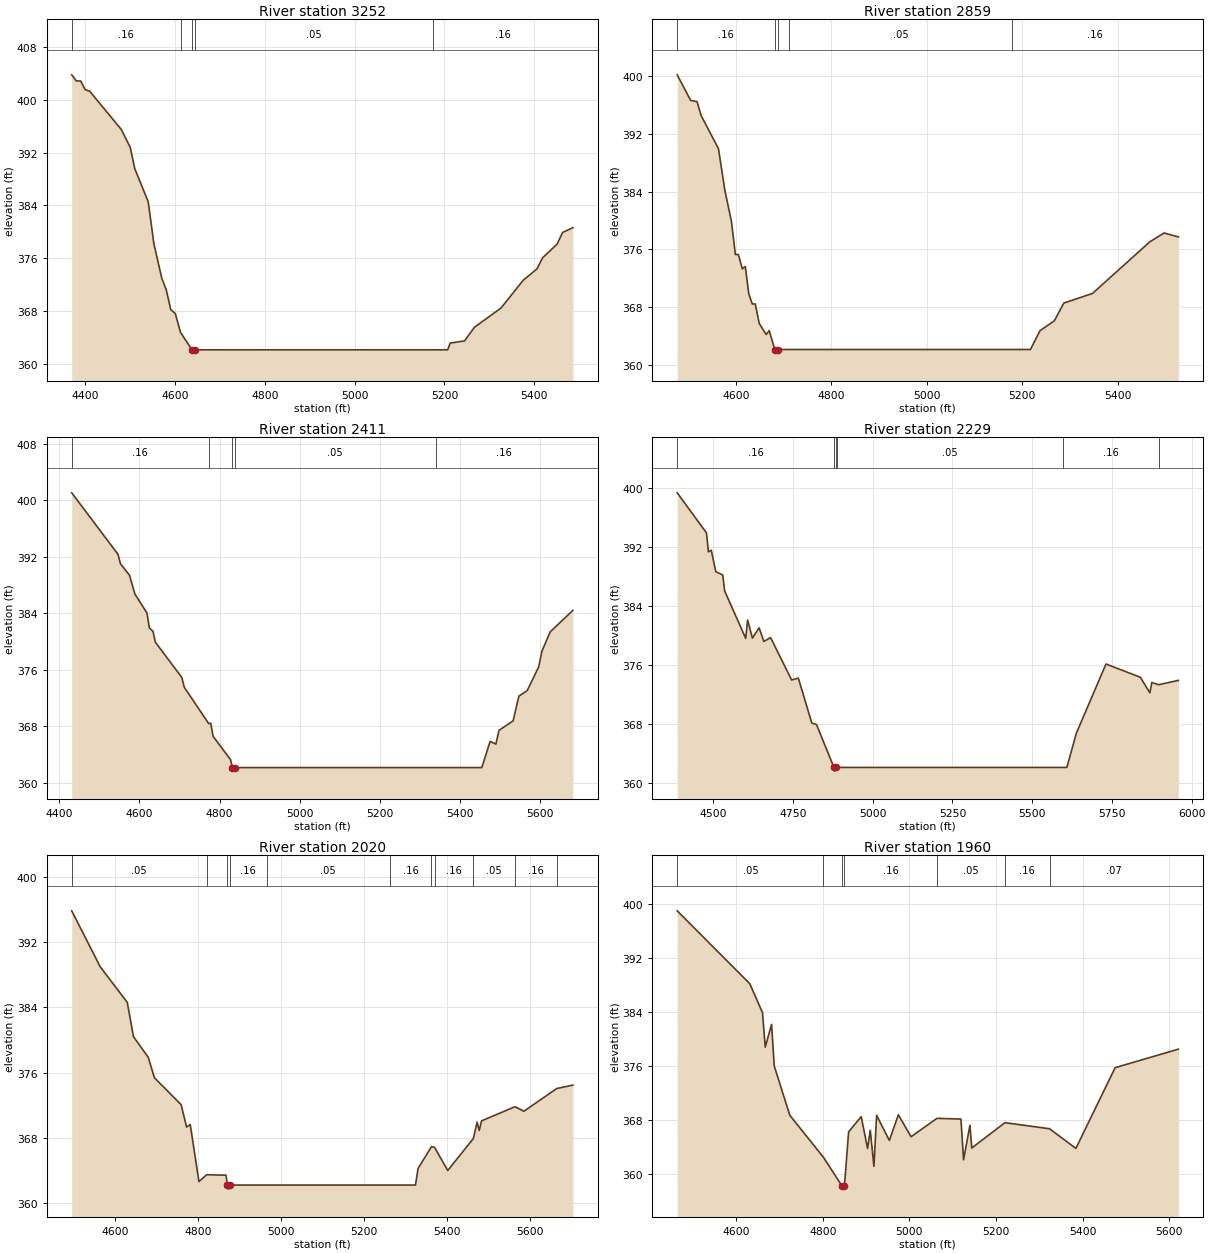
Type RM Length L Ch R = 1,3252,393,393,393
BEGIN DESCRIPTION:
UNT 124 IN UKCR 7.0
END DESCRIPTION:
XS GIS Cut Line= 3
      3653049.57     10601260.18      3652449.61     10601210.19
      3651999.62     10600960.20
#Sta/Elev= 30
  4369.5  403.76  4379.5  402.85  4389.5  402.82  4399.6  401.51  4409.6  401.28
  4479.8  395.51  4499.9  392.79  4509.9  389.59  4540.0  384.55  4552.6  378.21
  4570.1  373.02  4580.2  371.23  4590.2  368.25  4600.3  367.65  4611.9  364.82
  4637.4  362.17  4640.1  361.67  4643.4  362.17  5174.4  362.17  5207.2  362.17
  5212.9  363.19  5244.9  363.52  5266.7  365.57  5326.2  368.50  5375.4  372.68
  5406.2  374.41  5418.8  376.09  5450.9  378.14  5463.4  379.92  5486.3  380.65
#Mann=5,-1,0
  4369.5    0.16       0  4611.9    0.05       0  4637.4   0.033       0
  4643.4    0.05       0  5174.4    0.16       0
Bank Sta=4637.4,4643.4
Exp/Cntr=0.3,0.1

Type RM Length L Ch R = 1,2859,448,448,448
BEGIN DESCRIPTION:
UNT 124 IN UKCR 6.0
END DESCRIPTION:
XS GIS Cut Line= 3
      3653049.58     10601160.16      3652649.61     10600860.19
      3652099.57     10600860.19
#Sta/Elev= 30
  4477.1  400.14  4505.2  396.61  4518.7  396.43  4527.1  394.52  4563.5  389.94
  4577.1  384.10  4590.6  379.92  4598.9  375.31  4605.2  375.30  4613.5  373.32
  4619.8  373.64  4627.1  369.84  4634.4  368.47  4640.6  368.47  4648.9  365.78
  4663.5  364.24  4669.8  364.79  4681.4  362.17  4684.1  361.67  4687.4  362.17
  4712.3  362.17  5178.9  362.17  5217.1  362.17  5237.1  364.77  5267.1  366.13
  5287.1  368.59  5347.1  369.92  5467.1  377.05  5497.1  378.28  5527.1  377.73
#Mann=5,-1,0
  4477.1    0.16       0  4681.4   0.033       0  4687.4    0.16       0
  4712.3    0.05       0  5178.9    0.16       0
Bank Sta=4681.4,4687.4
Exp/Cntr=0.3,0.1

Type RM Length L Ch R = 1,2411,182,182,182
BEGIN DESCRIPTION:
UNT 124 IN UKCR 5.0
END DESCRIPTION:
XS GIS Cut Line= 3
      3653199.63     10600960.23      3652899.61     10600510.19
      3652349.62     10600060.20
#Sta/Elev= 30
  4430.9  401.04  4546.6  392.33  4552.6  391.01  4575.2  389.38  4588.7  386.71
  4618.7  384.05  4624.7  381.94  4633.8  381.45  4639.8  379.91  4705.9  374.91
  4711.9  373.54  4772.9  368.40  4778.0  368.45  4784.0  366.59  4827.6  363.29
  4832.1  362.17  4834.8  361.67  4838.1  362.17  5339.3  362.17  5454.9  362.17
  5475.7  365.88  5490.0  365.49  5497.9  367.44  5533.1  368.78  5547.5  372.28
  5568.3  373.06  5597.0  376.43  5604.9  378.61  5625.7  381.37  5682.4  384.42
#Mann=5,-1,0
  4430.9    0.16       0  4772.9    0.05       0  4832.1   0.033       0
  4838.1    0.05       0  5339.3    0.16       0
Bank Sta=4832.1,4838.1
Exp/Cntr=0.3,0.1

Type RM Length L Ch R = 1,2229,209,209,209
BEGIN DESCRIPTION:
Mapping XS 6e5f8a7d
END DESCRIPTION:
XS GIS Cut Line= 3
      3653356.35     10600880.61      3652918.83     10600229.53
      3652476.14     10599578.52
#Sta/Elev= 30
  4386.8  399.39  4478.6  393.96  4484.6  391.39  4493.6  391.61  4507.8  388.70
  4529.6  388.26  4535.6  386.09  4601.6  379.66  4607.6  382.15  4622.6  379.70
  4643.6  381.09  4658.6  379.25  4679.6  379.77  4745.6  374.02  4766.6  374.28
  4809.0  368.18  4823.6  367.99  4878.3  362.17  4881.0  361.67  4884.3  362.17
  4889.1  362.17  5595.8  362.17  5608.7  362.17  5638.6  366.82  5731.4  376.19
  5839.2  374.39  5869.0  372.28  5875.1  373.68  5896.3  373.38  5958.5  373.97
#Mann=6,-1,0
  4386.8    0.16       0  4878.3   0.033       0  4884.3    0.16       0
  4889.1    0.05       0  5595.8    0.16       0  5896.3    0.08       0
Bank Sta=4878.3,4884.3
Exp/Cntr=0.3,0.1

Type RM Length L Ch R = 1,2020,60,60,60
BEGIN DESCRIPTION:
Mapping XS a472513b
END DESCRIPTION:
XS GIS Cut Line= 3
      3653460.51     10600646.22      3653059.45     10600073.28
      3652960.68     10599574.23
#Sta/Elev= 30
  4495.6  395.87  4564.2  389.00  4629.5  384.62  4644.4  380.41  4680.1  377.87
  4694.9  375.36  4759.3  372.05  4772.5  369.30  4781.3  369.61  4802.2  362.60
  4820.8  363.44  4867.6  363.38  4870.7  362.17  4873.4  361.67  4876.7  362.17
  4965.7  362.17  5262.0  362.17  5324.2  362.17  5330.6  364.23  5362.8  366.88
  5370.1  366.81  5402.0  363.96  5463.6  367.88  5472.8  369.89  5477.9  368.88
  5483.5  370.06  5564.3  371.80  5585.5  371.24  5665.1  374.04  5703.7  374.45
#Mann=11,-1,0
  4495.6    0.05       0  4820.8    0.16       0  4870.7   0.033       0
  4876.7    0.16       0  4965.7    0.05       0  5262.0    0.16       0
  5362.8    0.07       0  5370.1    0.16       0  5463.6    0.05       0
  5564.3    0.16       0  5665.1    0.07       0
Bank Sta=4870.7,4876.7
Exp/Cntr=0.3,0.1

Type RM Length L Ch R = 1,1960,47,47,47
BEGIN DESCRIPTION:
Mapping XS f3872ea5
END DESCRIPTION:
XS GIS Cut Line= 4
      3653533.42     10600630.58      3653132.37     10600078.49
      3653085.49     10599969.11      3653043.84     10599615.03
#Sta/Elev= 30
  4463.5  398.99  4631.2  388.21  4660.6  383.92  4666.8  378.82  4681.5  382.19
  4687.7  376.04  4723.5  368.77  4801.4  362.53  4843.9  358.33  4846.6  357.83
  4849.9  358.33  4859.5  366.30  4888.6  368.55  4903.3  363.84  4909.5  366.54
  4918.0  361.19  4924.2  368.75  4953.6  365.03  4974.4  368.82  5003.8  365.58
  5063.6  368.30  5119.0  368.19  5125.1  362.17  5139.8  367.28  5144.0  363.91
  5220.7  367.66  5323.7  366.76  5384.6  363.85  5475.2  375.79  5621.4  378.53
#Mann=7,-1,0
  4463.5    0.05       0  4801.4    0.16       0  4843.9    0.07       0
  4849.9    0.16       0  5063.6    0.05       0  5220.7    0.16       0
  5323.7    0.07       0
Bank Sta=4843.9,4849.9
Exp/Cntr=0.3,0.1

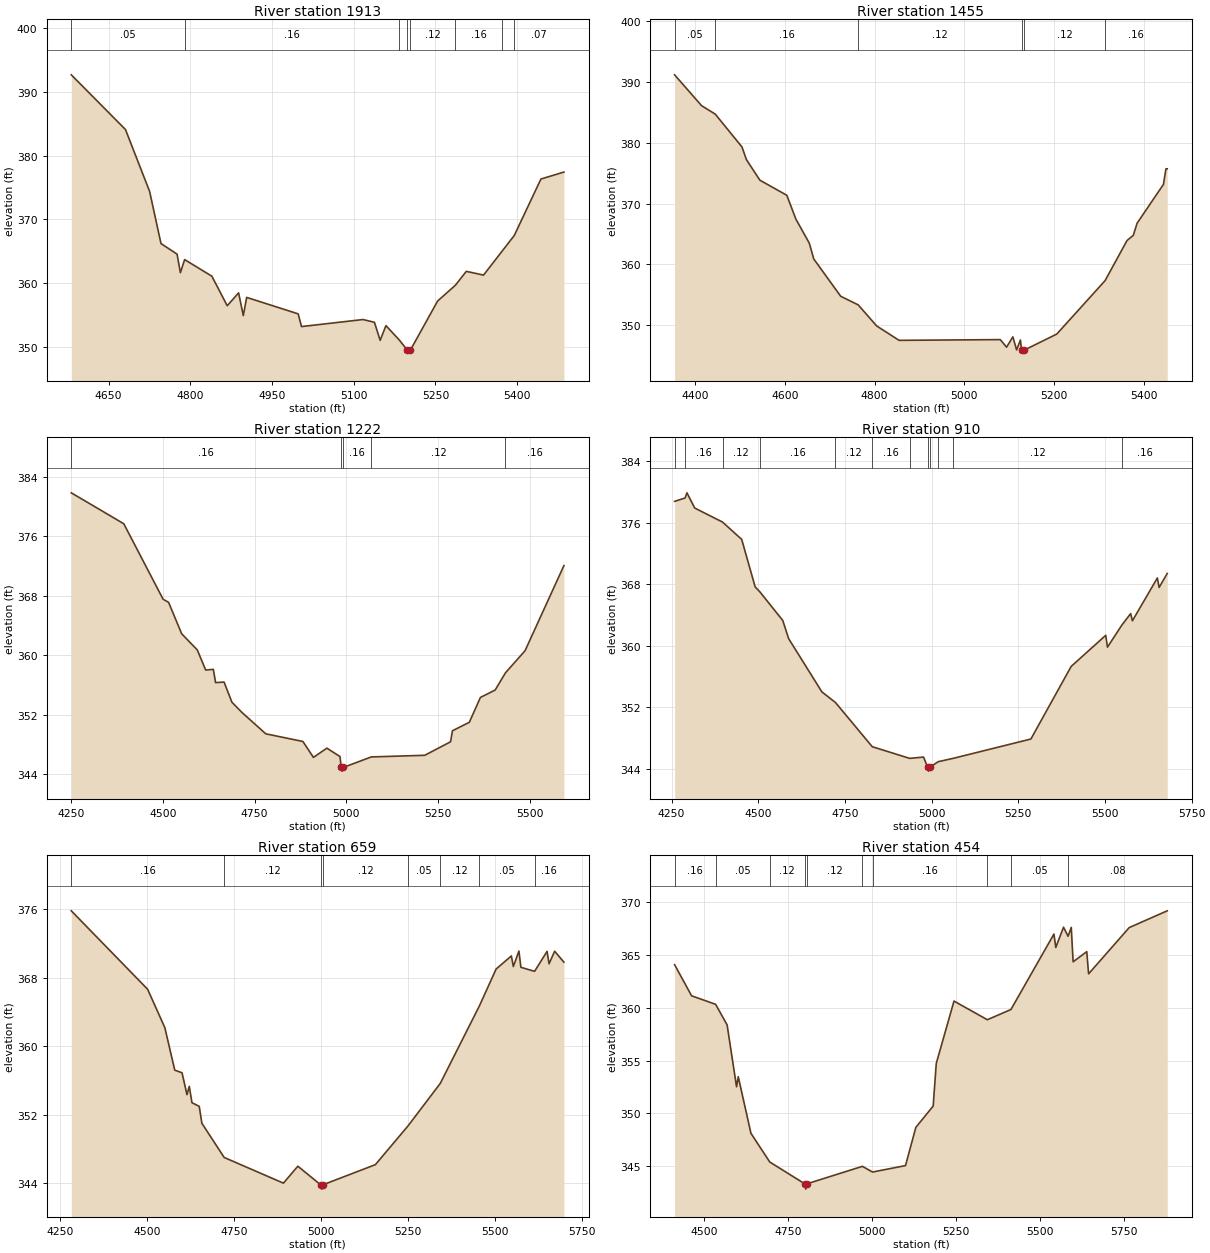
Type RM Length L Ch R = 1,1913,458,458,458
BEGIN DESCRIPTION:
UNT 124 IN UKCR 4.0
END DESCRIPTION:
XS GIS Cut Line= 3
      3653499.60     10600510.18      3653249.61     10600160.19
      3653099.59     10599710.14
#Sta/Elev= 30
  4581.4  392.64  4680.9  384.07  4725.2  374.38  4746.1  366.21  4775.6  364.56
  4781.7  361.65  4789.5  363.70  4839.5  361.10  4867.7  356.47  4888.6  358.49
  4897.2  354.93  4903.4  357.78  4998.0  355.20  5004.1  353.21  5116.9  354.31
  5138.0  353.88  5148.5  351.05  5159.1  353.36  5183.2  351.15  5198.2  349.55
  5201.0  349.05  5204.2  349.55  5254.0  357.21  5286.7  359.69  5306.7  361.86
  5338.3  361.27  5372.4  365.02  5394.7  367.47  5443.7  376.32  5485.9  377.41
#Mann=8,-1,0
  4581.4    0.05       0  4789.5    0.16       0  5183.2    0.12       0
  5198.2    0.07       0  5204.2    0.12       0  5286.7    0.16       0
  5372.4    0.12       0  5394.7    0.07       0
Bank Sta=5198.2,5204.2
Exp/Cntr=0.3,0.1

Type RM Length L Ch R = 1,1455,233,233,233
BEGIN DESCRIPTION:
UNT 124 IN UKCR 3.0
END DESCRIPTION:
XS GIS Cut Line= 3
      3653549.61     10600510.16      3653549.61     10599860.19
      3653149.60     10599660.18
#Sta/Elev= 30
  4354.5  391.14  4414.5  386.08  4445.1  384.68  4504.5  379.30  4514.5  377.21
  4544.5  373.83  4604.5  371.35  4624.5  367.46  4654.5  363.49  4664.5  360.89
  4724.5  354.76  4763.4  353.35  4804.5  349.89  4854.5  347.52  5079.9  347.64
  5093.9  346.40  5107.9  348.09  5116.3  345.95  5124.7  347.58  5127.3  345.92
  5130.0  345.42  5133.3  345.92  5205.7  348.55  5313.3  357.33  5362.2  363.92
  5376.2  364.78  5384.6  366.76  5443.3  373.14  5448.9  375.70  5451.7  375.70
#Mann=6,-1,0
  4354.5    0.05       0  4445.1    0.16       0  4763.4    0.12       0
  5127.3    0.07       0  5133.3    0.12       0  5313.3    0.16       0
Bank Sta=5127.3,5133.3
Exp/Cntr=0.3,0.1

Type RM Length L Ch R = 1,1222,312,312,312
BEGIN DESCRIPTION:
Mapping XS 240bb634
END DESCRIPTION:
XS GIS Cut Line= 3
      3654361.55     10600177.46      3653674.03     10599698.28
      3653175.05     10599615.11
#Sta/Elev= 30
  4249.8  381.84  4393.0  377.68  4500.3  367.52  4515.2  367.11  4550.9  362.88
  4593.5  360.71  4616.4  358.00  4637.3  358.09  4643.4  356.31  4666.6  356.38
  4687.9  353.68  4715.4  352.29  4780.4  349.42  4881.6  348.39  4910.4  346.25
  4947.0  347.49  4982.9  346.36  4986.0  344.90  4988.7  344.40  4992.0  344.90
  5068.2  346.31  5214.0  346.53  5284.5  348.35  5289.6  349.83  5335.6  350.97
  5366.0  354.32  5406.1  355.31  5434.3  357.63  5487.7  360.60  5593.7  372.05
#Mann=5,-1,0
  4249.8    0.16       0  4986.0    0.07       0  4992.0    0.16       0
  5068.2    0.12       0  5434.3    0.16       0
Bank Sta=4986,4992
Exp/Cntr=0.3,0.1

Type RM Length L Ch R = 1,910,251,251,251
BEGIN DESCRIPTION:
Mapping XS f021a4e5
END DESCRIPTION:
XS GIS Cut Line= 3
      3654538.65     10599859.75      3653809.45     10599505.57
      3653205.24     10599588.91
#Sta/Elev= 30
  4258.9  378.80  4289.3  379.24  4294.5  379.91  4317.0  377.93  4397.2  376.10
  4452.4  373.85  4491.3  367.66  4505.2  367.00  4570.8  363.30  4587.8  360.93
  4683.6  354.00  4722.9  352.61  4828.9  346.86  4936.9  345.34  4976.9  345.51
  4988.6  344.18  4991.3  343.68  4994.6  344.18  5019.3  344.91  5062.9  345.35
  5286.4  347.86  5402.5  357.31  5502.2  361.36  5507.2  359.82  5548.5  362.68
  5574.1  364.19  5579.1  363.25  5651.1  368.83  5656.1  367.59  5679.5  369.41
#Mann=12,-1,0
  4258.9    0.05       0  4289.3    0.16       0  4397.2    0.12       0
  4505.2    0.16       0  4722.9    0.12       0  4828.9    0.16       0
  4936.9    0.12       0  4988.6    0.07       0  4994.6    0.12       0
  5019.3    0.16       0  5062.9    0.12       0  5548.5    0.16       0
Bank Sta=4988.6,4994.6
Exp/Cntr=0.3,0.1

Type RM Length L Ch R = 1,659,205,205,205
BEGIN DESCRIPTION:
UNT 124 IN UKCR 2.0
END DESCRIPTION:
XS GIS Cut Line= 5
      3654496.94     10599531.60      3654205.28     10599281.61
      3653783.41     10599385.78      3653387.58     10599474.32
      3653220.92     10599568.06
#Sta/Elev= 30
  4282.5  375.82  4501.9  366.65  4551.3  362.17  4579.8  357.20  4600.7  356.90
  4614.9  354.34  4621.5  355.31  4629.2  353.40  4650.1  352.97  4657.7  351.00
  4721.8  347.00  4892.0  344.00  4933.5  345.98  4999.1  343.80  5001.8  343.30
  5005.1  343.80  5156.3  346.16  5250.5  350.71  5342.8  355.66  5455.0  364.70
  5503.2  369.02  5547.0  370.55  5552.7  369.31  5568.7  371.12  5574.4  369.22
  5613.7  368.75  5649.6  371.08  5655.3  369.63  5671.3  371.10  5698.0  369.82
#Mann=8,-1,0
  4282.5    0.16       0  4721.8    0.12       0  4999.1    0.07       0
  5005.1    0.12       0  5250.5    0.05       0  5342.8    0.12       0
  5455.0    0.05       0  5613.7    0.16       0
Bank Sta=4999.1,5005.1
Exp/Cntr=0.3,0.1

Type RM Length L Ch R = 1,454,310,310,310
BEGIN DESCRIPTION:
Mapping XS d3371a04
END DESCRIPTION:
XS GIS Cut Line= 5
      3654423.99     10599057.66      3654179.24     10599094.11
      3653726.12     10599187.86      3653455.28     10599255.57
      3653023.79     10599453.12
#Sta/Elev= 30
  4413.3  364.09  4463.8  361.14  4535.3  360.33  4569.4  358.38  4597.4  352.52
  4602.5  353.47  4640.2  348.11  4696.1  345.39  4800.3  343.32  4803.1  342.82
  4806.3  343.32  4971.4  344.98  5001.6  344.44  5099.5  345.05  5130.2  348.67
  5181.7  350.69  5190.9  354.73  5243.6  360.64  5342.7  358.87  5412.8  359.84
  5540.6  366.99  5546.1  365.72  5569.1  367.64  5582.6  366.78  5592.1  367.62
  5597.6  364.36  5638.1  365.32  5643.6  363.22  5764.2  367.60  5877.2  369.19
#Mann=10,-1,0
  4413.3    0.16       0  4535.3    0.05       0  4696.1    0.12       0
  4800.3    0.07       0  4806.3    0.12       0  4971.4    0.08       0
  5001.6    0.16       0  5342.7    0.08       0  5412.8    0.05       0
  5582.6    0.08       0
Bank Sta=4800.3,4806.3
Exp/Cntr=0.3,0.1

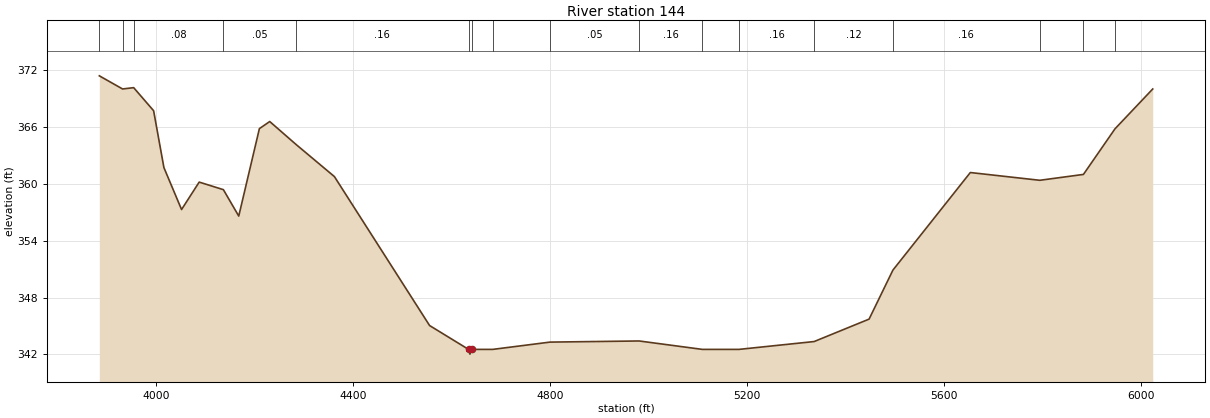
Type RM Length L Ch R = 1,144,0,0,0
BEGIN DESCRIPTION:
UNT 124 IN UKCR 1.0
END DESCRIPTION:
XS GIS Cut Line= 5
      3654772.96     10599229.51      3654397.99     10598969.11
      3653835.49     10598838.90      3653668.83     10598896.19
      3652934.49     10599463.87
#Sta/Elev= 30
  3885.3  371.43  3932.5  370.04  3955.0  370.18  3995.5  367.74  4016.4  361.73
  4052.2  357.30  4088.0  360.20  4137.1  359.40  4168.3  356.61  4210.2  365.85
  4231.2  366.60  4284.3  364.19  4362.5  360.78  4555.7  345.04  4634.8  342.52
  4637.6  342.02  4640.8  342.52  4683.8  342.52  4800.0  343.29  4981.0  343.41
  5109.5  342.52  5183.6  342.52  5336.3  343.35  5447.8  345.72  5496.2  350.90
  5653.3  361.21  5794.3  360.39  5882.9  361.01  5947.0  365.83  6023.6  370.04
#Mann=17,-1,0
  3885.3    0.16       0  3932.5    0.05       0  3955.0    0.08       0
  4137.1    0.05       0  4284.3    0.16       0  4634.8    0.07       0
  4640.8    0.16       0  4683.8    0.12       0  4800.0    0.05       0
  4981.0    0.16       0  5109.5    0.05       0  5183.6    0.16       0
  5336.3    0.12       0  5496.2    0.16       0  5794.3    0.08       0
  5882.9    0.16       0  5947.0    0.08       0
Bank Sta=4634.8,4640.8
Exp/Cntr=0.3,0.1

Chan Stop Cuts=-1