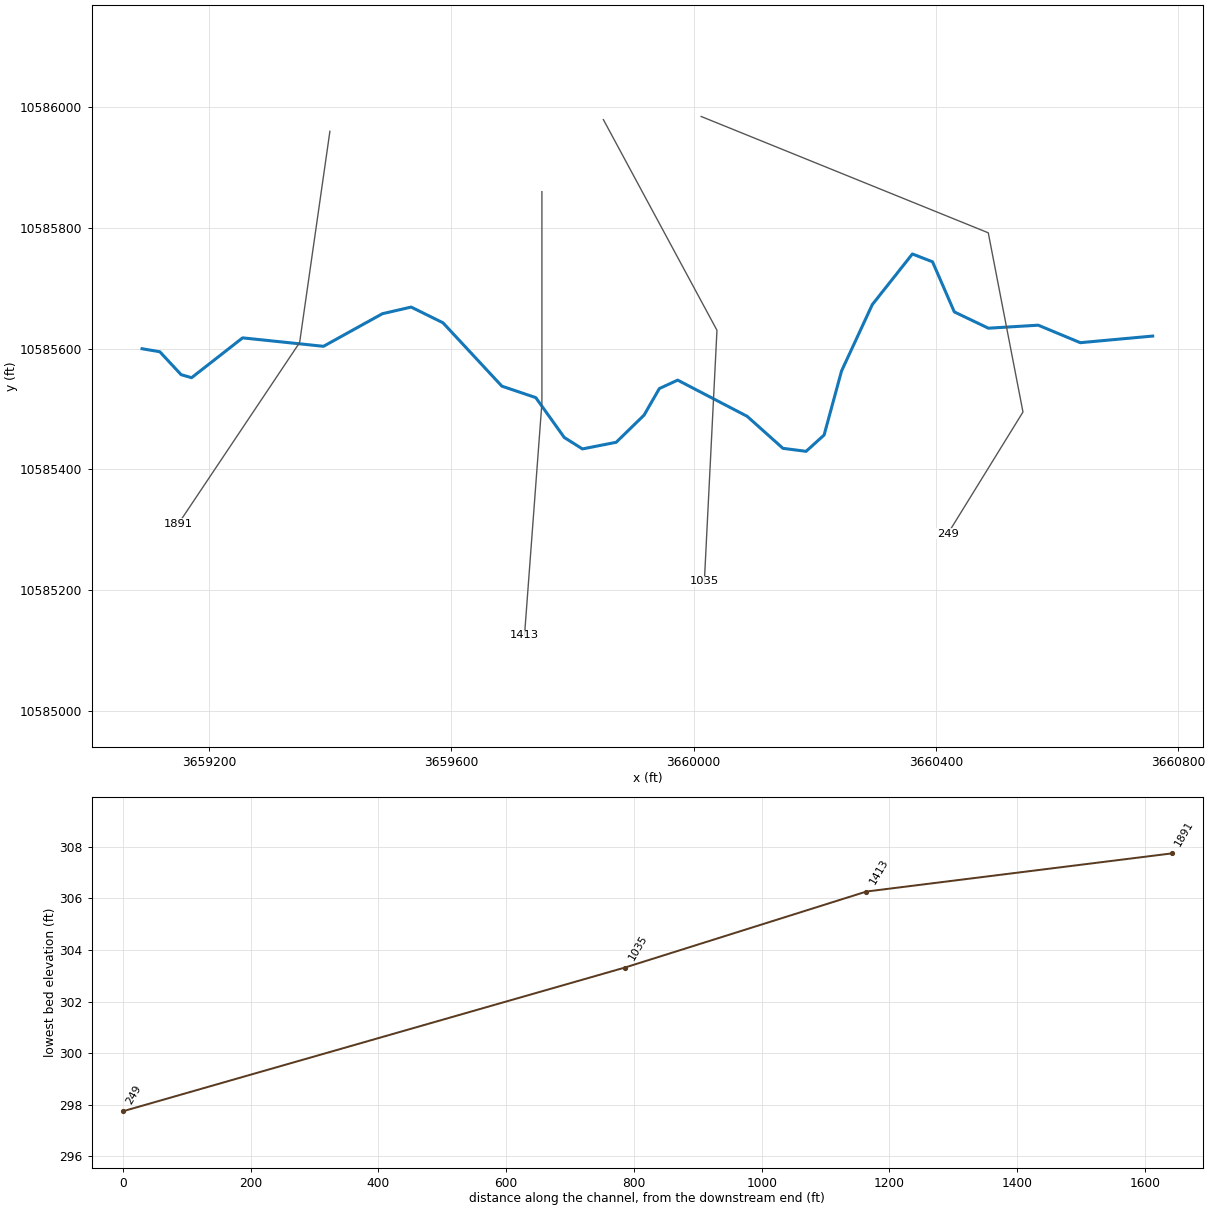
--- UNT 130 IN UKCR.prj (project) ---

Proj Title=UNT 130 IN UKCR Base Level Engineering
Current Plan=p01
Default Exp/Contr=0.3,0.1
English Units
Geom File=g01
Flow File=f01
Plan File=p01
BEGIN DESCRIPTION:
UNT 130 IN UKCR
END DESCRIPTION:

--- UNT 130 IN UKCR.p01 (plan) ---

Plan Title=Multiple Run
Short Identifier=Multiple
Geom File=g01
Flow File=f01
Subcritical Flow
K Sum by GR= 0
Std Step Tol= 0.01
Critical Tol= 0.01
Num of Std Step Trials= 20
Max Error Tol= 0.3
Flow Tol Ratio= 0.001
Split Flow NTrial= 30
Split Flow Tol= 0.02
Split Flow Ratio= 0.02
Log Output Level= 0
Friction Slope Method= 1
Unsteady Friction Slope Method= 2
Unsteady Bridges Friction Slope Method= 1
Parabolic Critical Depth
Global Vel Dist=  1 , 1 , 1
Global Log Level= 0
CheckData=True
Encroach Param= -1, 0, 0, 0
BEGIN DESCRIPTION:
Multiple Run
END DESCRIPTION:

--- UNT 130 IN UKCR.f01 (steady flow) ---

Flow Title=Multiple
Number of Profiles=7
Profile Names=10-year,25-year,50-year,1pct_min,100-year,1pct_plu,500-year
River Rch & RM= UNT 130 IN UKCR,Reach-1,1891
     445     592     712     630     852    1152    1222
Boundary for River Rch & Prof#=UNT 130 IN UKCR,Reach-1,1
Up Type=0
Dn Type=3
Dn Slope=0.005
Boundary for River Rch & Prof#=UNT 130 IN UKCR,Reach-1,2
Up Type=0
Dn Type=3
Dn Slope=0.005
Boundary for River Rch & Prof#=UNT 130 IN UKCR,Reach-1,3
Up Type=0
Dn Type=3
Dn Slope=0.005
Boundary for River Rch & Prof#=UNT 130 IN UKCR,Reach-1,4
Up Type=0
Dn Type=3
Dn Slope=0.005
Boundary for River Rch & Prof#=UNT 130 IN UKCR,Reach-1,5
Up Type=0
Dn Type=3
Dn Slope=0.005
Boundary for River Rch & Prof#=UNT 130 IN UKCR,Reach-1,6
Up Type=0
Dn Type=3
Dn Slope=0.005
Boundary for River Rch & Prof#=UNT 130 IN UKCR,Reach-1,7
Up Type=0
Dn Type=3
Dn Slope=0.005

--- UNT 130 IN UKCR.g01 (geometry) ---

Geom Title=Existing Conditions

River Reach=UNT 130 IN UKCR,Reach-1
Reach XY= 30
      3659089.50     10585600.00      3659118.75     10585595.00
      3659154.00     10585557.00      3659171.25     10585552.00
      3659255.50     10585618.00      3659389.00     10585604.00
      3659486.25     10585658.00      3659533.75     10585669.00
      3659586.25     10585643.00      3659683.50     10585538.00
      3659739.50     10585519.00      3659786.50     10585453.00
      3659816.50     10585434.00      3659872.25     10585445.00
      3659918.25     10585490.00      3659943.50     10585534.00
      3659973.75     10585548.00      3660088.50     10585488.00
      3660147.50     10585435.00      3660185.75     10585430.00
      3660215.50     10585457.00      3660244.25     10585563.00
      3660295.00     10585673.00      3660361.25     10585757.00
      3660394.50     10585744.00      3660430.50     10585661.00
      3660486.75     10585634.00      3660569.00     10585639.00
      3660638.50     10585610.00      3660758.00     10585621.00

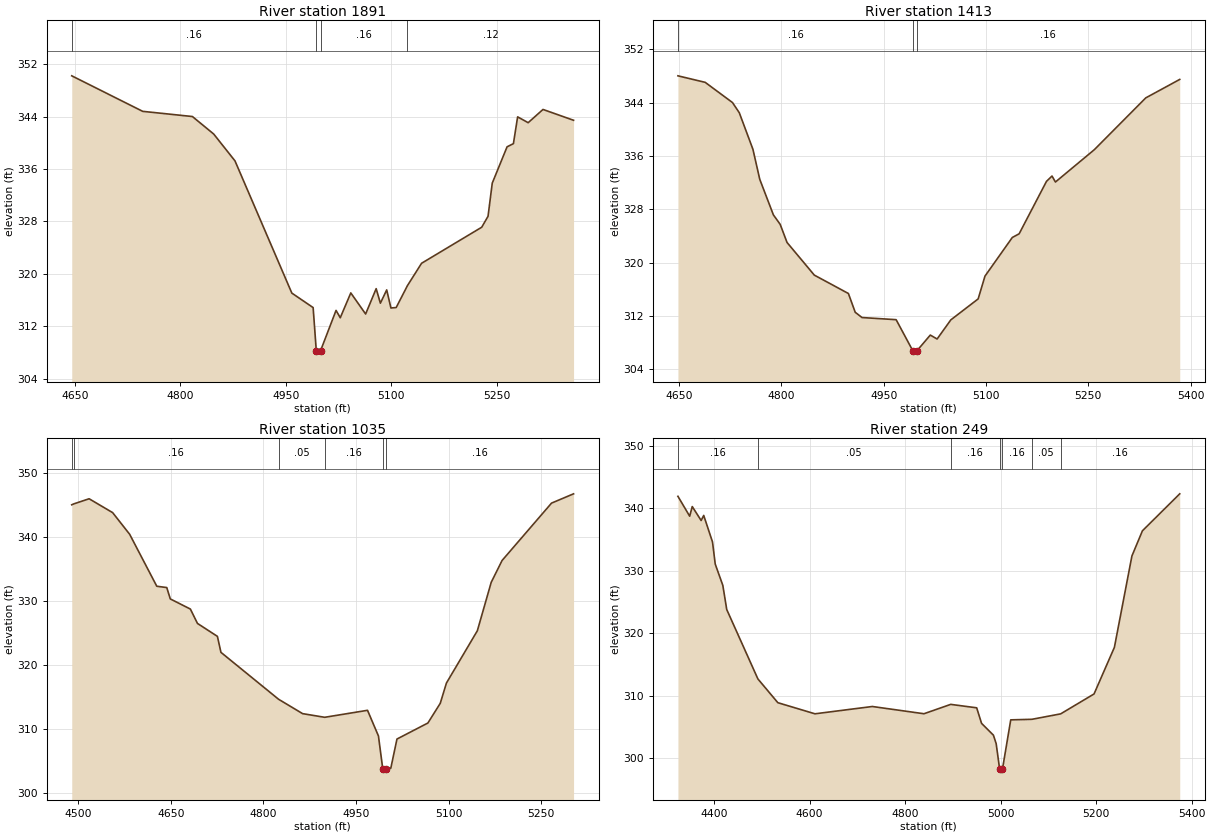
Type RM Length L Ch R = 1,1891,478,478,478
BEGIN DESCRIPTION:
UNT 130 IN UKCR 4.0
END DESCRIPTION:
XS GIS Cut Line= 3
      3659399.61     10585960.20      3659349.61     10585610.19
      3659149.62     10585310.21
#Sta/Elev= 30
  4645.3  350.21  4746.3  344.79  4817.0  344.00  4847.3  341.33  4877.6  337.23
  4958.5  317.06  4988.8  314.85  4993.3  308.25  4996.1  307.75  4999.3  308.25
  5021.4  314.42  5027.4  313.30  5042.4  317.09  5063.5  313.87  5078.5  317.74
  5084.5  315.52  5093.5  317.55  5099.5  314.79  5107.0  314.86  5123.0  318.20
  5143.1  321.61  5228.7  327.11  5237.7  328.78  5243.7  333.84  5264.8  339.38
  5273.8  339.86  5279.8  343.95  5294.8  343.06  5315.9  345.08  5359.4  343.43
#Mann=4,-1,0
  4645.3    0.16       0  4993.3    0.07       0  4999.3    0.16       0
  5123.0    0.12       0
Bank Sta=4993.3,4999.3
Exp/Cntr=0.3,0.1

Type RM Length L Ch R = 1,1413,378,378,378
BEGIN DESCRIPTION:
UNT 130 IN UKCR 3.0
END DESCRIPTION:
XS GIS Cut Line= 3
      3659749.61     10585860.21      3659749.61     10585510.19
      3659720.91     10585125.38
#Sta/Elev= 30
  4648.2  348.04  4688.2  347.06  4728.2  344.03  4738.2  342.50  4758.2  337.01
  4768.2  332.51  4788.2  327.17  4798.2  325.74  4808.2  323.03  4848.2  318.13
  4898.2  315.37  4908.2  312.55  4918.2  311.76  4968.2  311.44  4992.7  306.77
  4995.5  306.27  4998.7  306.77  5018.3  309.13  5028.3  308.54  5048.4  311.41
  5088.5  314.56  5098.5  317.98  5138.6  323.78  5148.6  324.33  5188.7  332.20
  5196.8  333.00  5201.8  332.10  5258.9  336.96  5334.3  344.73  5384.1  347.50
#Mann=3,-1,0
  4648.2    0.16       0  4992.7    0.07       0  4998.7    0.16       0
Bank Sta=4992.7,4998.7
Exp/Cntr=0.3,0.1

Type RM Length L Ch R = 1,1035,786,786,786
BEGIN DESCRIPTION:
UNT 130 IN UKCR 2.0
END DESCRIPTION:
XS GIS Cut Line= 3
      3659851.11     10585979.54      3660038.62     10585630.57
      3660017.82     10585214.54
#Sta/Elev= 30
  4489.6  345.01  4492.9  345.15  4517.7  345.95  4555.8  343.79  4583.4  340.41
  4627.3  332.31  4643.5  332.10  4649.2  330.33  4681.7  328.75  4693.2  326.51
  4725.5  324.49  4731.2  322.00  4824.6  314.68  4863.5  312.44  4899.3  311.87
  4968.6  312.96  4986.3  308.96  4993.3  303.82  4996.0  303.32  4999.3  303.82
  5006.3  303.93  5016.3  308.48  5066.4  310.98  5086.4  314.05  5096.4  317.21
  5146.5  325.37  5168.9  332.91  5186.5  336.32  5266.6  345.27  5302.3  346.72
#Mann=6,-1,0
  4489.6     0.1       0  4492.9    0.16       0  4824.6    0.05       0
  4899.3    0.16       0  4993.3    0.07       0  4999.3    0.16       0
Bank Sta=4993.3,4999.3
Exp/Cntr=0.3,0.1

Type RM Length L Ch R = 1,249,0,0,0
BEGIN DESCRIPTION:
UNT 130 IN UKCR 1.0
END DESCRIPTION:
XS GIS Cut Line= 4
      3660012.58     10585984.73      3660486.53     10585792.03
      3660543.83     10585495.15      3660419.82     10585293.64
#Sta/Elev= 30
  4324.5  341.91  4349.1  338.73  4354.5  340.27  4373.1  338.04  4378.5  338.85
  4396.9  334.60  4402.6  331.06  4418.5  327.65  4426.7  323.78  4491.9  312.67
  4533.7  308.86  4611.4  307.08  4731.5  308.25  4839.6  307.09  4895.6  308.59
  4950.0  308.04  4960.2  305.55  4985.0  303.66  4990.8  302.30  4998.0  298.24
  5000.7  297.74  5004.0  298.24  5021.3  306.11  5065.7  306.20  5125.8  307.07
  5195.7  310.26  5238.3  317.72  5275.0  332.36  5297.0  336.39  5375.1  342.31
#Mann=7,-1,0
  4324.5    0.16       0  4491.9    0.05       0  4895.6    0.16       0
  4998.0    0.07       0  5004.0    0.16       0  5065.7    0.05       0
  5125.8    0.16       0
Bank Sta=4998,5004
Exp/Cntr=0.3,0.1

Chan Stop Cuts=-1