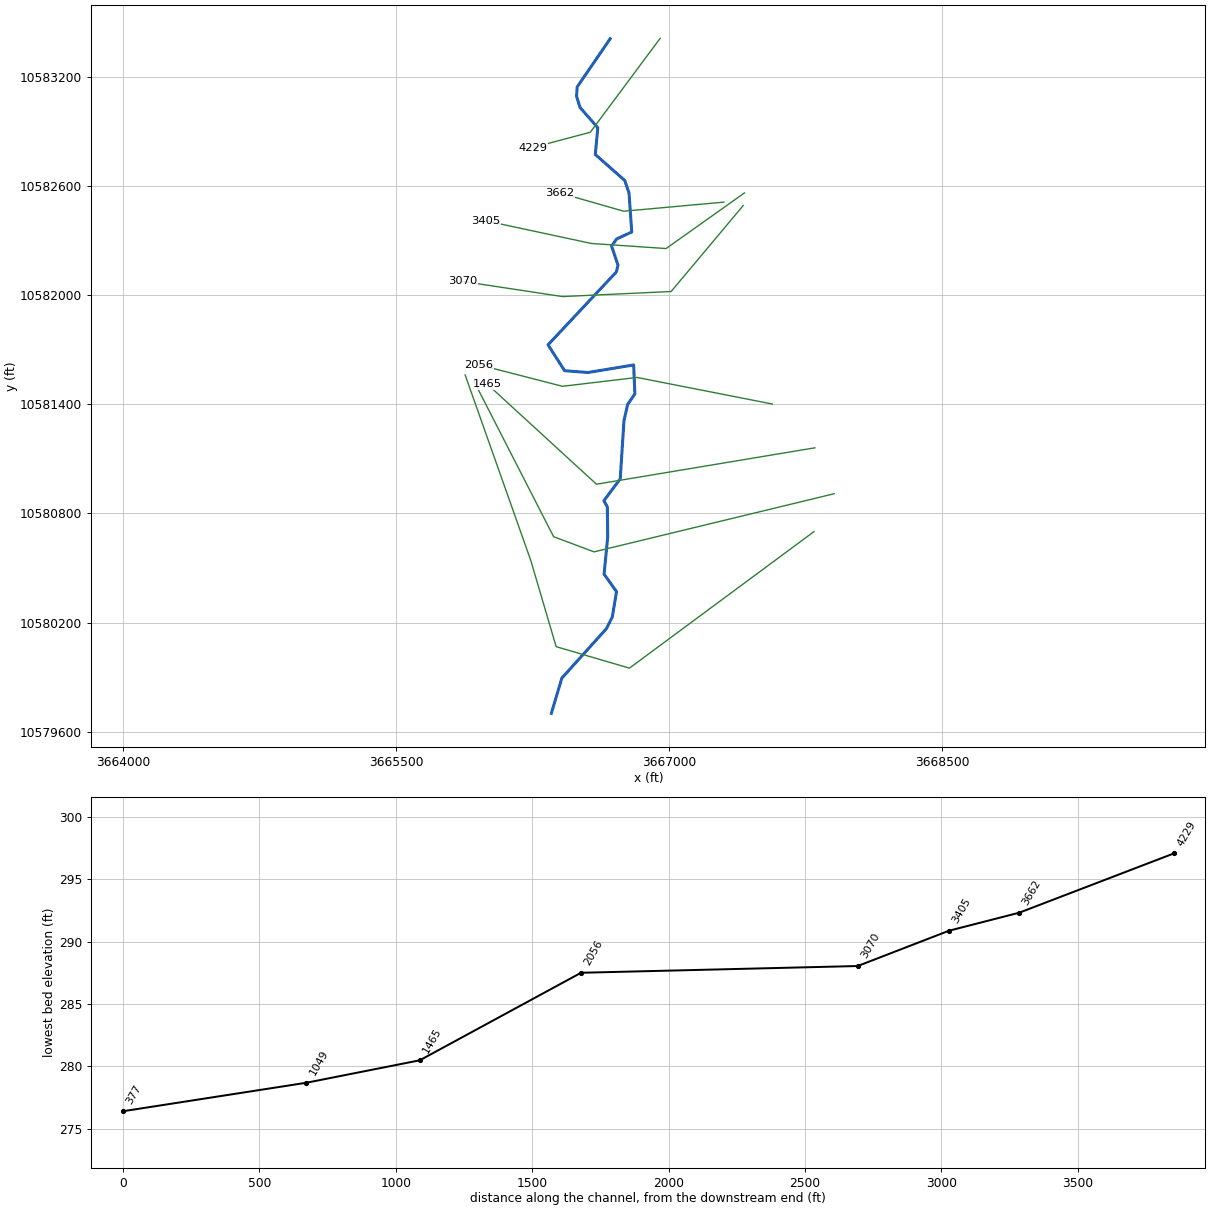
--- UNT 133 IN UKCR.prj (project) ---

Proj Title=UNT 133 IN UKCR Base Level Engineering
Current Plan=p01
Default Exp/Contr=0.3,0.1
English Units
Geom File=g01
Flow File=f01
Plan File=p01
Y Axis Title=Elevation
X Axis Title(PF)=Main Channel Distance
X Axis Title(XS)=Station
BEGIN DESCRIPTION:
UNT 133 IN UKCR
END DESCRIPTION:
DSS Export Rating Curves= 0
DSS Export Rating Curve Sorted= 0
DSS Export Volume Flow Curves= 0
DXF OffsetX= 0
DXF OffsetY= 0
DXF ScaleX= 1
DXF ScaleY= 10

--- UNT 133 IN UKCR.p01 (plan) ---

Plan Title=Multiple Run
Program Version=4.10
Short Identifier=Multiple
Geom File=g01
Flow File=f01
Subcritical Flow
K Sum by GR= 0
Std Step Tol= 0.01
Critical Tol= 0.01
Num of Std Step Trials= 20
Max Error Tol= 0.3
Flow Tol Ratio= 0.001
Split Flow NTrial= 30
Split Flow Tol= 0.02
Split Flow Ratio= 0.02
Log Output Level= 0
Friction Slope Method= 1
Unsteady Friction Slope Method= 2
Unsteady Bridges Friction Slope Method= 1
Parabolic Critical Depth
Global Vel Dist= 1 , 1 , 1
Global Log Level= 0
CheckData=True
Encroach Param=-1 ,0,0, 0
BEGIN DESCRIPTION:
Multiple Run
END DESCRIPTION:
Computation Interval=1HOUR
Output Interval=1HOUR
Run HTab= 0
Run UNet= 0
Run PostProcess= 0
Run WQNet= 0
UNET Theta= 1
UNET Theta Warmup= 1
UNET ZTol= 0.02
UNET ZSATol= 0.05
UNET MxIter= 20
UNET MaxInSteps= 0
UNET DtIC= 0
UNET DtMin= 0
UNET MaxCRTS= 20
UNET WFStab= 2
UNET SFStab= 1
UNET WFX= 1
UNET SFX= 1
UNET DSS MLevel= 4
UNET DZMax Abort= 100
UNET Convert EG Bridges= 0
UNET Use Existing IB Tables=-1
UNET Froude Reduction=False
UNET Froude Limit= 1
UNET Froude Power= 10
UNET Time Slicing=0,0, 5
UNET Junction Losses=0
Instantaneous Interval=1HOUR
Write IC File= 0
Write IC File at Sim End=0
Echo Input=False
Echo Parameters=False
Echo Output=False
Write Detailed= 0
WQ AD Non Conservative
WQ ULTIMATE=-1
WQ Max Comp Step=1HOUR
WQ Output Interval=15MIN
WQ Output Selected Increments= 0
WQ Output face flow=0
WQ Output face velocity=0
WQ Output face area=0
WQ Output face dispersion=0
WQ Output cell volume=0
WQ Output cell surface area=0
WQ Output cell continuity=0
WQ Output cumulative cell continuity=0
WQ Output face conc=0
WQ Output face dconc_dx=0
WQ Output face courant=0
WQ Output face peclet=0
WQ Output face adv mass=0
WQ Output face disp mass=0
WQ Output cell mass=0
WQ Output cell source sink temp=0
WQ Output cell source sink nsm=0
WQ Output MaxMinRange=-1
WQ Daily Max Min Mean=-1
WQ Daily Range=0
WQ Daily Time=0
WQ Create Restart=0
WQ Fixed Restart=0
WQ System Summary=0
WQ Use Fixed Temperature=0
Sorting and Armoring Iterations= 10
XS Update Threshold= 0.02
Hydraulics Update Threshold= 0.02
Energy Slope Method= 1
Volume Change Method= 0
XS Weighting Method= 0
Number of US Weighted Cross Sections= 1
Number of DS Weighted Cross Sections= 1
Upstream XS Weight=0.25
Main XS Weight=0.5
Downstream XS Weight=0.25
Number of DS XS's Weighted with US Boundary= 1
Upstream Boundary Weight= 1
Weight of XSs Associated with US Boundary= 0
Number of US XS's Weighted with DS Boundary= 1
Downstream Boundary Weight= 0.5
Weight of XSs Associated with DS Boundary= 0.5
Sediment Output Level= 4
Mass or Volume Output= 0
Output Increment Type= 1
Profile and TS Output Increment= 10
XS Output Flag= 0
XS Output Increment= 10
Disregard all LS=0
Disregard all Conn=0
Disregard all Breaches=0
Disregard all Pumps=0

--- UNT 133 IN UKCR.f01 (steady flow) ---

Flow Title=Multiple
Number of Profiles=7
Profile Names=10-year,25-year,50-year,1pct_min,100-year,1pct_plu,500-year
River Rch & RM= UNT 133 IN UKCR,Reach-1,4229
     158     190     213     175     236     320     293
Boundary for River Rch & Prof#=UNT 133 IN UKCR,Reach-1,1
Up Type=0
Dn Type=3
Dn Slope=0.005
Boundary for River Rch & Prof#=UNT 133 IN UKCR,Reach-1,2
Up Type=0
Dn Type=3
Dn Slope=0.005
Boundary for River Rch & Prof#=UNT 133 IN UKCR,Reach-1,3
Up Type=0
Dn Type=3
Dn Slope=0.005
Boundary for River Rch & Prof#=UNT 133 IN UKCR,Reach-1,4
Up Type=0
Dn Type=3
Dn Slope=0.005
Boundary for River Rch & Prof#=UNT 133 IN UKCR,Reach-1,5
Up Type=0
Dn Type=3
Dn Slope=0.005
Boundary for River Rch & Prof#=UNT 133 IN UKCR,Reach-1,6
Up Type=0
Dn Type=3
Dn Slope=0.005
Boundary for River Rch & Prof#=UNT 133 IN UKCR,Reach-1,7
Up Type=0
Dn Type=3
Dn Slope=0.005

--- UNT 133 IN UKCR.g01 (geometry) ---

Geom Title=Existing Conditions
Program Version=4.10

River Reach=UNT 133 IN UKCR ,Reach-1
Reach XY= 30
        3666675.       10583408.       3666493.5       10583143.
      3666490.25       10583091.       3666509.5       10583030.
        3666607.       10582919.      3666593.25       10582772.
      3666755.25       10582629.       3666778.5       10582560.
       3666793.5       10582346.        3666711.       10582308.
      3666682.75       10582269.        3666718.       10582164.
      3666709.25       10582127.       3666333.5       10581726.
       3666424.5       10581584.       3666552.5       10581574.
      3666803.92     10581615.45       3666810.6     10581456.75
      3666771.03     10581398.39      3666750.71     10581309.35
      3666730.22     10580989.45      3666640.36     10580869.31
      3666659.25       10580836.       3666661.5       10580671.
       3666641.5       10580466.      3666709.75       10580370.
      3666686.75       10580231.      3666654.75       10580167.
       3666409.5       10579895.       3666351.5       10579701.

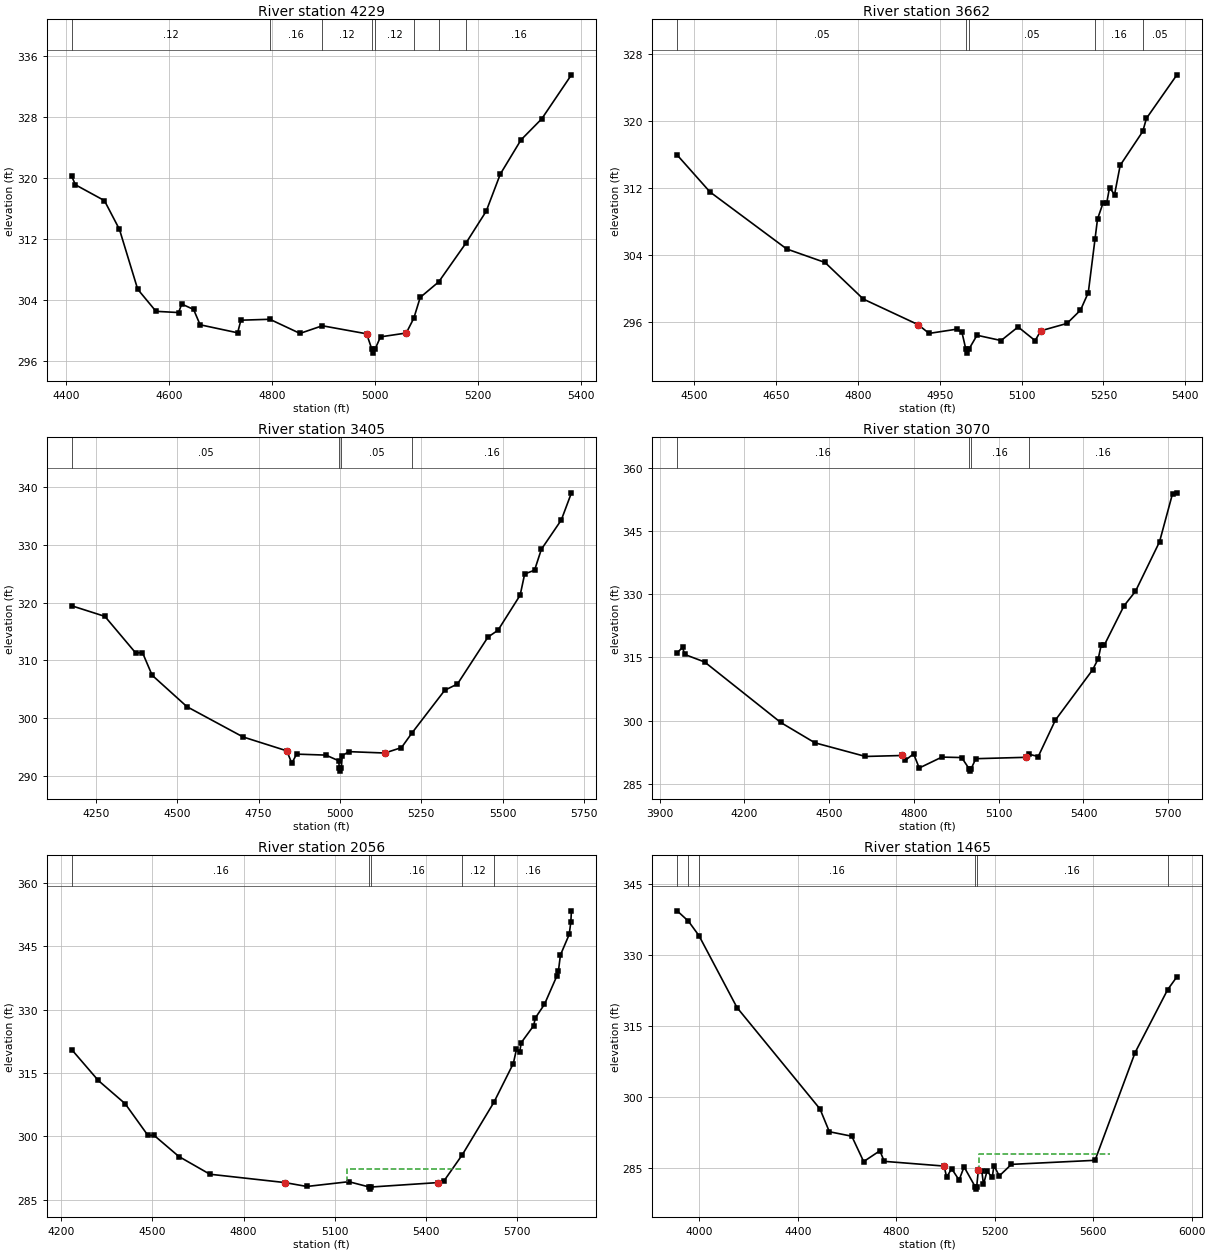
Type RM Length L Ch R = 1 ,4229    ,567,567,567
BEGIN DESCRIPTION:
UNT 133 IN UKCR 7.0
END DESCRIPTION:
XS GIS Cut Line= 3
      3666949.59     10583410.17      3666565.53     10582894.02
      3666249.62     10582810.19
#Sta/Elev= 30
  4410.9  320.22  4418.2  319.09  4474.5  317.02  4503.7  313.25  4539.1  305.42
  4574.6  302.53  4618.4  302.37  4624.6  303.48  4647.6  302.78  4660.2  300.77
  4733.1  299.72  4739.4  301.37  4795.6  301.49  4854.1  299.64  4897.5  300.64
  4983.4  299.59  4993.7  297.56  4996.5  297.06  4999.7  297.56  5010.5  299.19
  5060.4  299.69  5075.1  301.63  5087.5  304.35  5123.5  306.39  5176.4  311.47
  5215.6  315.63    5243  320.49  5283.2  324.97  5323.4  327.72  5381.1  333.48
#Mann= 8 ,-1 , 0
  4410.9     .12       0  4795.6     .16       0  4897.5     .12       0
  4993.7     .07       0  4999.7     .12       0  5075.1     .16       0
  5123.5     .05       0  5176.4     .16       0
Bank Sta=4983.4,5060.4
XS Rating Curve= 0 ,0
Exp/Cntr=0.3,0.1

Type RM Length L Ch R = 1 ,3662    ,257,257,257
BEGIN DESCRIPTION:
UNT 133 IN UKCR 6.0
END DESCRIPTION:
XS GIS Cut Line= 3
      3667299.66     10582510.19      3666749.61     10582460.19
      3666399.63     10582560.18
#Sta/Elev= 30
  4468.5  315.92  4528.8  311.51  4669.4  304.72  4739.7  303.11  4809.9  298.75
  4910.4   295.7  4930.4  294.66  4980.7  295.16  4990.7  294.78  4997.7  292.81
  5000.5  292.31  5003.7  292.81  5018.3  294.44  5062.4  293.81  5093.6  295.43
  5124.8   293.8  5135.2  294.97  5183.3  295.85    5208  297.43  5222.3  299.52
  5234.6  305.88  5239.2  308.28  5249.6  310.24  5256.1  310.21  5261.3  312.04
  5270.4  311.19  5280.8  314.69  5322.2  318.73  5328.9  320.28  5384.8  325.47
#Mann= 5 ,-1 , 0
  4468.5     .05       0  4997.7     .03       0  5003.7     .05       0
  5234.6     .16       0  5322.2     .05       0
Bank Sta=4910.4,5135.2
XS Rating Curve= 0 ,0
Exp/Cntr=0.3,0.1

Type RM Length L Ch R = 1 ,3405    ,335,335,335
BEGIN DESCRIPTION:
Mapping XS e4450db6
END DESCRIPTION:
XS GIS Cut Line= 4
      3667412.73     10582560.68      3666982.19     10582255.13
      3666572.47     10582282.91      3665989.11     10582407.92
#Sta/Elev= 30
  4175.8  319.46  4277.8  317.63  4372.5   311.3  4393.4  311.36    4423  307.45
    4530  302.01  4702.2  296.78  4836.6  294.38    4852  292.23  4866.7  293.81
  4956.9  293.64  4996.1  292.66  4998.1  291.37  5000.9  290.87  5004.1  291.37
    5007  293.53  5027.1  294.24  5137.8     294  5188.9  294.94  5220.1  297.39
  5321.9  304.86  5360.8  305.93  5454.5  314.04  5485.5  315.24  5553.4  321.29
  5567.3  324.96  5597.7  325.61  5618.5  329.22  5679.8  334.29    5711  338.99
#Mann= 4 ,-1 , 0
  4175.8     .05       0  4998.1     .03       0  5004.1     .05       0
  5220.1     .16       0
Bank Sta=4836.6,5137.8
XS Rating Curve= 0 ,0
Exp/Cntr=0.3,0.1

Type RM Length L Ch R = 1 ,3070    ,1014,1014,1014
BEGIN DESCRIPTION:
UNT 133 IN UKCR 5.0
END DESCRIPTION:
XS GIS Cut Line= 4
      3667405.79     10582491.22      3667009.97     10582019.02
      3666412.75     10581991.25      3665864.36     10582074.55
#Sta/Elev= 30
  3962.1  316.12  3981.3  317.38    3989  315.72  4059.3  313.94  4328.8  299.58
  4449.6  294.76  4628.7  291.52  4758.8  291.75  4768.8  290.57  4798.9  292.14
  4818.9  288.78    4899  291.37    4969  291.26  4996.1  288.54  4998.8  288.04
  5002.1  288.54  5019.1  290.99  5198.4  291.32    5207  292.06    5240   291.5
  5300.7  300.15  5432.2  312.05  5452.4  314.71  5462.5  317.86  5473.2  317.86
  5543.4  327.25  5583.9  330.68  5669.2  342.44  5715.4  353.91  5730.8  354.07
#Mann= 4 ,-1 , 0
  3962.1     .16       0  4996.1     .03       0  5002.1     .16       0
    5207     .16       0
Bank Sta=4758.8,5198.4
XS Rating Curve= 0 ,0
Exp/Cntr=0.3,0.1

Type RM Length L Ch R = 1 ,2056    ,591,591,591
BEGIN DESCRIPTION:
UNT 133 IN UKCR 4.0
END DESCRIPTION:
XS GIS Cut Line= 4
       3667565.5     10581400.97      3666822.47      10581546.8
      3666412.75     10581498.19      3665954.51     10581616.22
#Sta/Elev= 30
  4234.6  320.58  4322.1  313.25  4410.5  307.74  4485.2  300.24  4505.6  300.24
  4587.1  295.23    4689  291.03  4935.1  289.06  5007.6  288.13  5145.7  289.26
  5213.2     288    5216   287.5  5219.2     288  5438.6  289.05  5459.3  289.52
  5519.2  295.69  5622.4  308.04  5686.5  317.27  5696.8  320.61  5707.1  319.89
  5712.7  322.23  5753.4  326.24  5758.7  328.04  5788.9   331.3  5829.6     338
  5834.8  339.24  5841.4  342.98  5870.3  347.87  5875.5  350.81  5877.6  353.45
#Mann= 5 ,-1 , 0
  4234.6     .16       0  5213.2     .03       0  5219.2     .16       0
  5519.2     .12       0  5622.4     .16       0
#XS Ineff= 1 ,-1
 5139.89 5520.34  292.27
Permanent Ineff=
       F
Bank Sta=4935.1,5438.6
XS Rating Curve= 0 ,0
Exp/Cntr=0.3,0.1

Type RM Length L Ch R = 1 ,1465    ,416,416,416
BEGIN DESCRIPTION:
UNT 133 IN UKCR 3.0
END DESCRIPTION:
XS GIS Cut Line= 3
      3667799.57     10581160.18      3666599.61     10580960.19
      3665999.57     10581510.22
#Sta/Elev= 30
  3909.8   339.4  3955.7  337.21  3998.5  334.15  4153.1  318.92  4490.2  297.46
  4528.2  292.64  4619.4  291.69  4667.6  286.32  4733.5  288.61  4751.2  286.37
  4994.5  285.37  5004.7     283  5024.9  284.82  5055.3  282.42  5075.6   285.2
  5120.8  280.99  5123.5  280.49  5126.8  280.99  5133.4  284.44  5147.6  284.37
  5154.4  281.48  5168.6  284.26  5190.1     283  5196.9  285.49  5218.5  283.28
  5267.8  285.73  5607.6  286.59  5770.4   309.4  5902.6  322.71  5940.3  325.44
#Mann= 6 ,-1 , 0
  3909.8     .05       0  3955.7      .1       0  3998.5     .16       0
  5120.8     .03       0  5126.8     .16       0  5902.6     .16       0
#XS Ineff= 1 ,-1
 5134.94 5667.61  287.83
Permanent Ineff=
       F
Bank Sta=4994.5,5133.4
XS Rating Curve= 0 ,0
Exp/Cntr=0.3,0.1

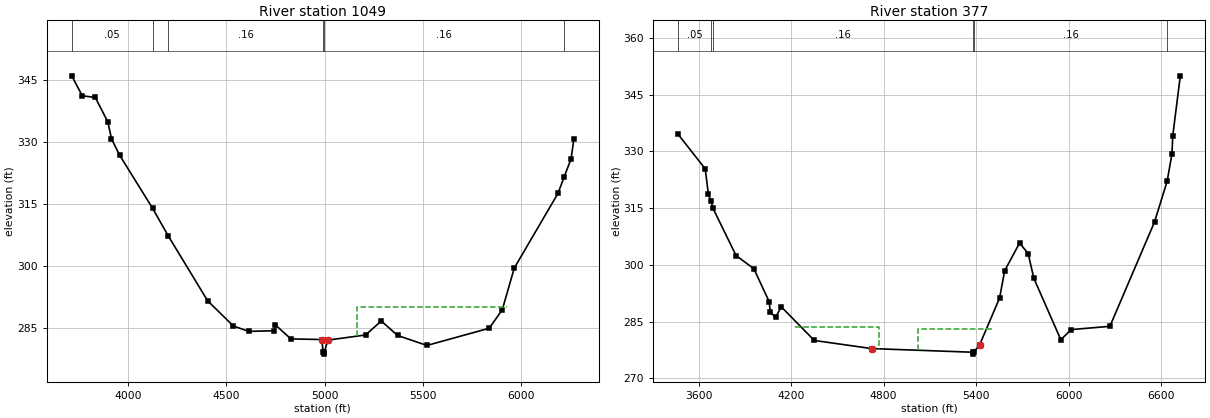
Type RM Length L Ch R = 1 ,1049    ,672,672,672
BEGIN DESCRIPTION:
UNT 133 IN UKCR 2.0
END DESCRIPTION:
XS GIS Cut Line= 4
       3667905.8     10580907.91      3666586.36     10580588.47
      3666364.14      10580671.8      3665926.86     10581525.54
#Sta/Elev= 30
  3713.4  345.98  3766.8  341.15  3832.9  340.76  3897.4  334.79  3915.3  330.77
  3956.4  326.83  4124.1  313.98  4204.9  307.22  4404.5  291.59  4535.1   285.5
  4613.6  284.19  4744.2  284.35  4749.4  285.75  4827.9  282.37  4985.3  282.22
  4992.2  279.19  4994.9  278.69  4998.2  279.19  5016.2  282.08  5207.8  283.32
  5287.9   286.7  5370.7  283.21    5520  280.79  5836.9  284.95  5903.5  289.42
  5964.5  299.51  6186.6  317.54  6218.3  321.56  6253.2  325.87  6267.5  330.65
#Mann= 6 ,-1 , 0
  3713.4     .05       0  4124.1      .1       0  4204.9     .16       0
  4992.2     .03       0  4998.2     .16       0  6218.3     .16       0
#XS Ineff= 1 ,-1
 5163.64 5925.57290.1785
Permanent Ineff=
       F
Bank Sta=4985.3,5016.2
XS Rating Curve= 0 ,0
Exp/Cntr=0.3,0.1

Type RM Length L Ch R = 1 ,377     ,0,0,0
BEGIN DESCRIPTION:
UNT 133 IN UKCR 1.0
END DESCRIPTION:
XS GIS Cut Line= 5
      3667794.68     10580699.57       3666780.8     10579949.58
      3666378.03     10580067.63      3666239.14     10580539.86
      3665878.03      10581560.7
#Sta/Elev= 30
  3467.9  334.49  3642.8   325.4  3663.6  318.62  3679.8     317  3693.2  314.96
  3843.2  302.46    3958  299.01  4058.2  290.23  4064.4  287.49  4099.9  286.12
  4135.4  288.94  4350.4  280.02  4721.9  277.88  5377.7  276.91  5380.5  276.41
  5383.7  276.91  5422.4  278.87  5551.7  291.24  5585.1  298.49  5681.5  305.79
  5736.8  303.01  5774.2  296.44  5948.9  280.21  6016.1   282.9  6267.2  283.76
  6556.5  311.35  6638.5  322.14  6669.5  329.33  6674.8  334.14  6723.8  349.99
#Mann= 6 ,-1 , 0
  3467.9     .05       0  3679.8      .1       0  3693.2     .16       0
  5377.7     .03       0  5383.7     .16       0  6638.5     .16       0
#XS Ineff= 2 ,-1
 4227.27 4772.73  283.59    5025 5513.64  283.08
Permanent Ineff=
       F       F
Bank Sta=4721.9,5422.4
XS Rating Curve= 0 ,0
Exp/Cntr=0.3,0.1

Chan Stop Cuts=-1
Use User Specified Reach Order=0
Composite Channel Slope=5