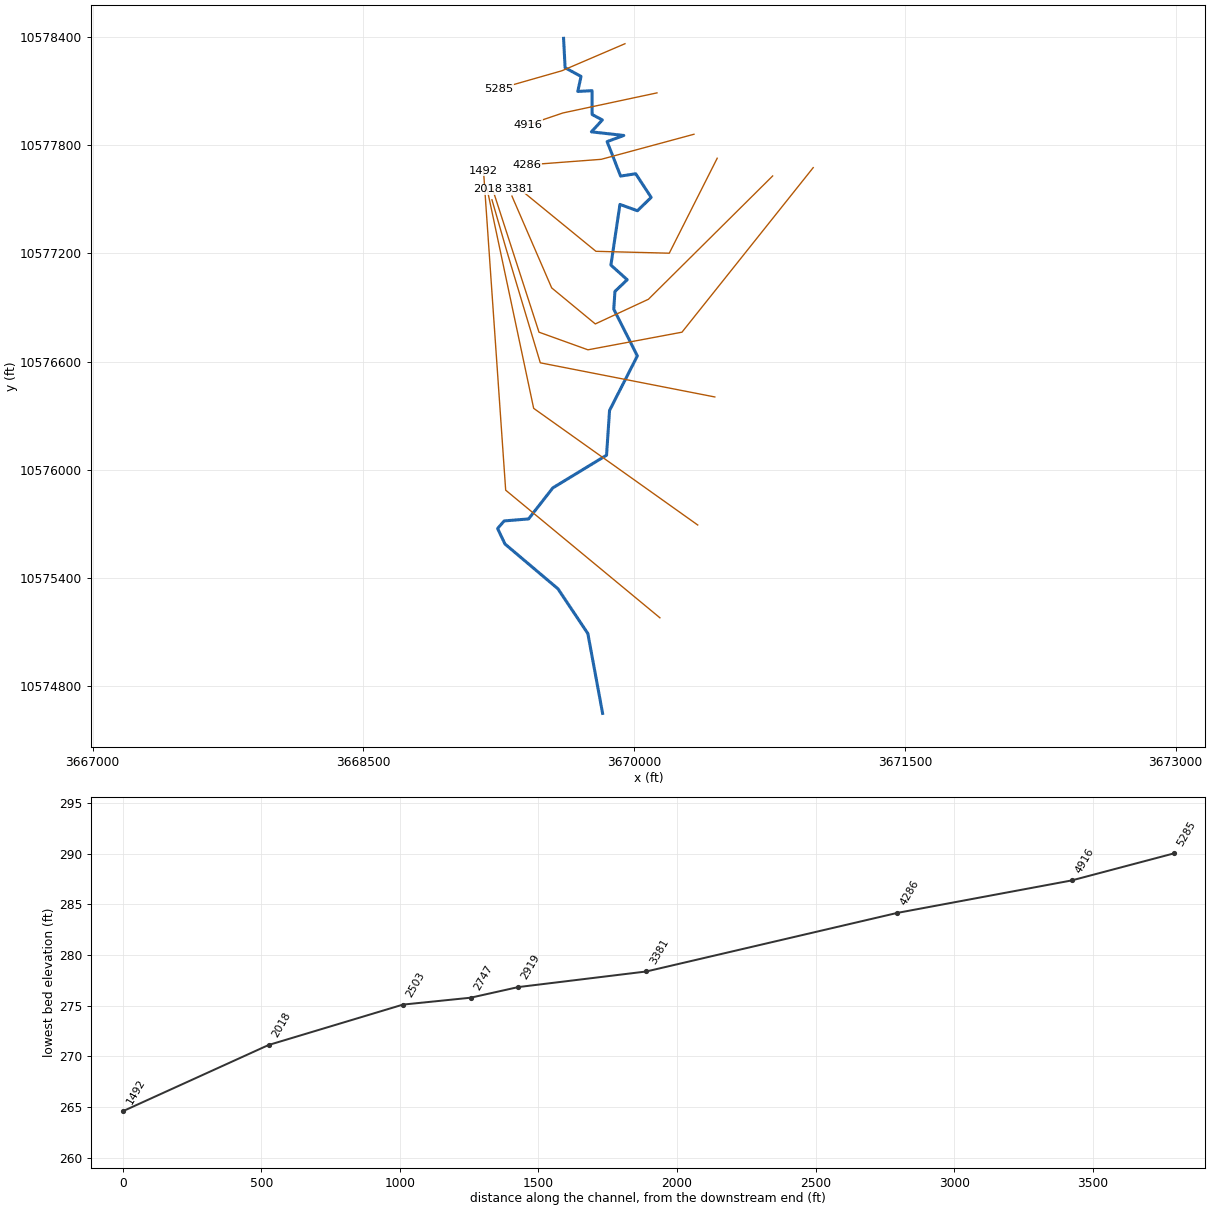
--- UNT 136 IN UKCR.prj (project) ---

Proj Title=UNT 136 IN UKCR Base Level Engineering
Current Plan=p01
Default Exp/Contr=0.3,0.1
English Units
Geom File=g01
Flow File=f01
Plan File=p01
Y Axis Title=Elevation
X Axis Title(PF)=Main Channel Distance
X Axis Title(XS)=Station
BEGIN DESCRIPTION:
UNT 136 IN UKCR
END DESCRIPTION:
DSS Export Rating Curves= 0
DSS Export Rating Curve Sorted= 0
DSS Export Volume Flow Curves= 0
DXF OffsetX= 0
DXF OffsetY= 0
DXF ScaleX= 1
DXF ScaleY= 10

--- UNT 136 IN UKCR.p01 (plan) ---

Plan Title=Multiple Run
Short Identifier=Multiple
Geom File=g01
Flow File=f01
Subcritical Flow
K Sum by GR= 0
Std Step Tol= 0.01
Critical Tol= 0.01
Num of Std Step Trials= 20
Max Error Tol= 0.3
Flow Tol Ratio= 0.001
Split Flow NTrial= 30
Split Flow Tol= 0.02
Split Flow Ratio= 0.02
Log Output Level= 0
Friction Slope Method= 1
Unsteady Friction Slope Method= 2
Unsteady Bridges Friction Slope Method= 1
Parabolic Critical Depth
Global Vel Dist=  1 , 1 , 1
Global Log Level= 0
CheckData=True
Encroach Param= -1, 0, 0, 0
BEGIN DESCRIPTION:
Multiple Run
END DESCRIPTION:

--- UNT 136 IN UKCR.f01 (steady flow) ---

Flow Title=Multiple
Number of Profiles=7
Profile Names=10-year,25-year,50-year,1pct_min,100-year,1pct_plu,500-year
River Rch & RM= UNT 136 IN UKCR,Reach-1,5285
     368     487     584     515     697     942     996
Boundary for River Rch & Prof#=UNT 136 IN UKCR,Reach-1,1
Up Type=0
Dn Type=3
Dn Slope=0.005
Boundary for River Rch & Prof#=UNT 136 IN UKCR,Reach-1,2
Up Type=0
Dn Type=3
Dn Slope=0.005
Boundary for River Rch & Prof#=UNT 136 IN UKCR,Reach-1,3
Up Type=0
Dn Type=3
Dn Slope=0.005
Boundary for River Rch & Prof#=UNT 136 IN UKCR,Reach-1,4
Up Type=0
Dn Type=3
Dn Slope=0.005
Boundary for River Rch & Prof#=UNT 136 IN UKCR,Reach-1,5
Up Type=0
Dn Type=3
Dn Slope=0.005
Boundary for River Rch & Prof#=UNT 136 IN UKCR,Reach-1,6
Up Type=0
Dn Type=3
Dn Slope=0.005
Boundary for River Rch & Prof#=UNT 136 IN UKCR,Reach-1,7
Up Type=0
Dn Type=3
Dn Slope=0.005

--- UNT 136 IN UKCR.g01 (geometry) ---

Geom Title=Existing Conditions
Program Version=4.10

River Reach=UNT 136 IN UKCR ,Reach-1
Reach XY= 30
       3669609.5       10578390.        3669618.       10578227.
      3669706.25       10578179.      3669688.25       10578096.
      3669767.25       10578100.      3669767.75       10577968.
      3669824.25       10577938.       3669763.5       10577872.
      3669943.25       10577852.      3669850.75       10577818.
       3669925.5       10577627.        3670009.       10577640.
      3670094.75       10577509.      3670018.75       10577435.
      3669921.75       10577470.      3669871.75       10577134.
        3669962.       10577053.        3669894.       10576988.
       3669887.5       10576890.      3670018.25       10576631.
      3669864.25       10576329.       3669847.5       10576081.
        3669550.       10575900.       3669415.5       10575728.
       3669280.5       10575717.        3669244.       10575675.
        3669285.       10575589.       3669578.5       10575341.
        3669744.       10575093.      3669825.75       10574651.

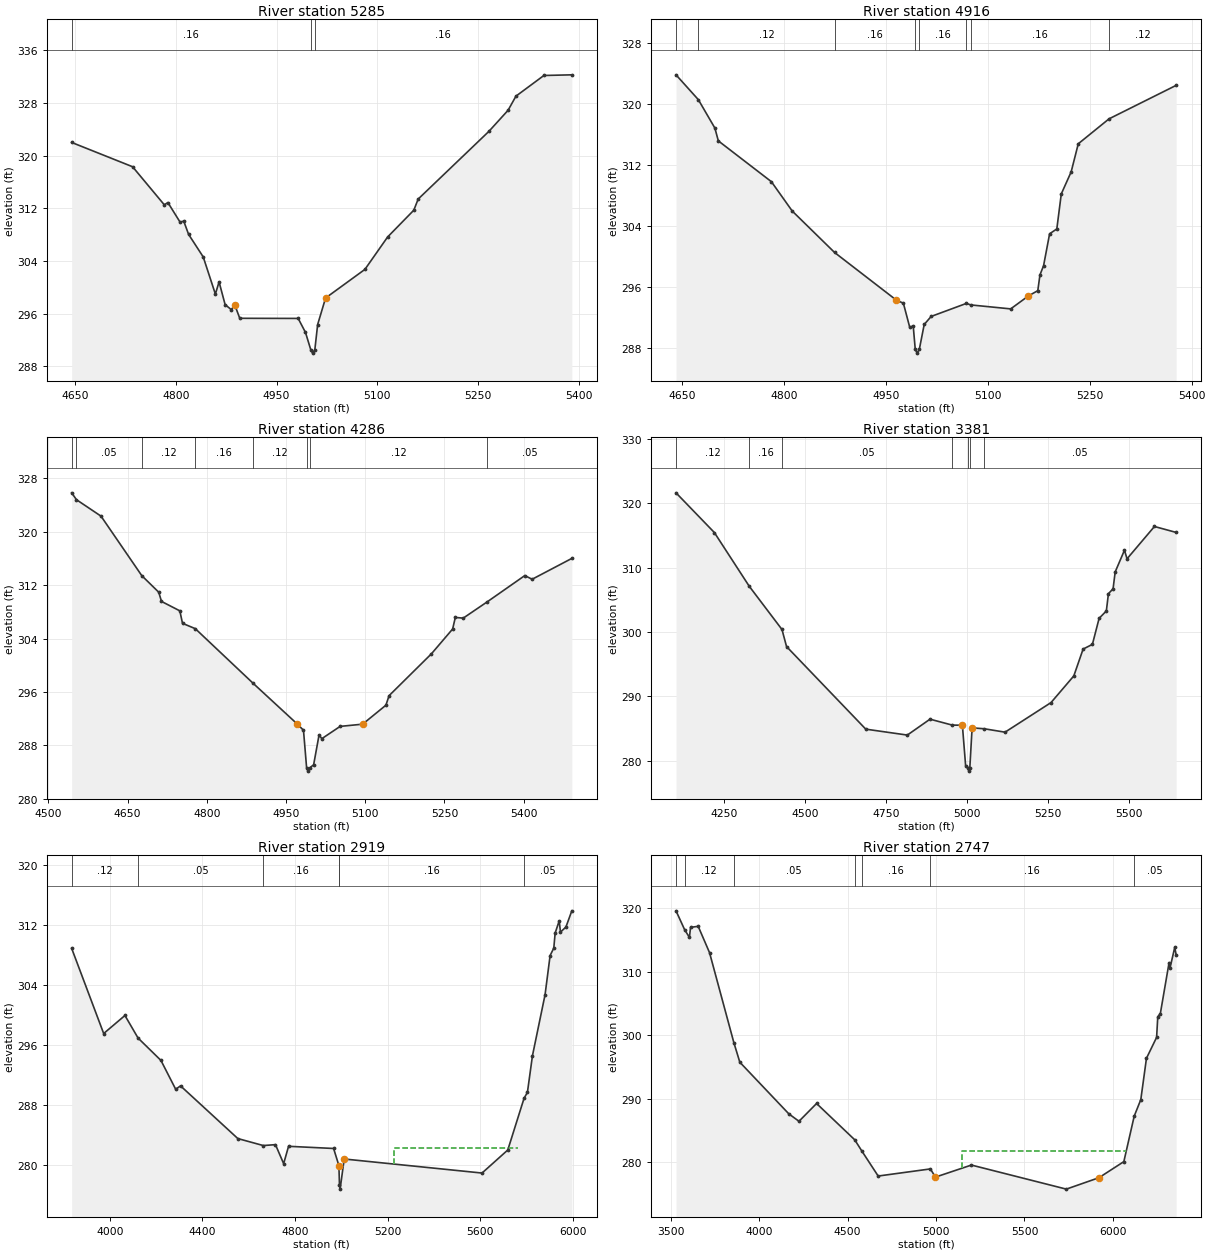
Type RM Length L Ch R = 1 ,5285    ,369,369,369
BEGIN DESCRIPTION:
UNT 136 IN UKCR 4.0
END DESCRIPTION:
XS GIS Cut Line= 3
      3669949.65     10578360.21      3669599.61     10578210.19
      3669249.65      10578110.2
#Sta/Elev= 30
  4644.8  322.03  4735.5  318.34  4782.7  312.56  4788.1   312.9  4806.2  309.93
  4811.7  310.08  4818.9  308.07  4840.7  304.64  4858.8     299  4864.3  300.85
  4873.3   297.4  4882.4  296.64  4887.8  297.32  4895.1  295.32  4982.1   295.3
    4993  293.17  5000.9  290.53  5003.6  290.03  5006.9  290.53  5011.1  294.37
  5022.9   298.4  5081.5  302.75  5115.3  307.67  5154.3  311.74  5160.8  313.43
  5266.1  323.71  5294.7  326.92  5306.4  329.06    5348   332.2  5389.6   332.3
#Mann= 3 ,-1 , 0
  4644.8     .16       0  5000.9     .07       0  5006.9     .16       0
Bank Sta=4887.8,5022.9
XS Rating Curve= 0 ,0
Exp/Cntr=0.3,0.1

Type RM Length L Ch R = 1 ,4916    ,630,630,630
BEGIN DESCRIPTION:
UNT 136 IN UKCR 3.0
END DESCRIPTION:
XS GIS Cut Line= 3
      3670126.96     10578087.88      3669606.12     10577976.77
      3669413.18     10577911.31
#Sta/Elev= 30
  4640.9  323.85  4673.8  320.59  4698.1  316.87  4703.2  315.19  4781.3  309.84
    4812  305.99  4874.3  300.56  4965.4   294.3  4975.6  293.91    4985  290.74
  4990.1  290.93  4993.1  287.86  4995.8  287.36  4999.1  287.86  5006.3  291.12
  5016.5  292.17  5068.4  293.88  5074.9  293.68  5133.6  293.16  5159.7  294.86
  5173.5  295.55  5176.7  297.62    5182  298.82  5190.9  303.01  5201.5  303.64
  5208.1  308.24  5222.6  311.12  5233.1  314.81  5278.4  318.08  5377.2  322.47
#Mann= 8 ,-1 , 0
  4640.9     .16       0  4673.8     .12       0  4874.3     .16       0
  4993.1     .07       0  4999.1     .16       0  5068.4     .12       0
  5074.9     .16       0  5278.4     .12       0
Bank Sta=4965.4,5159.7
XS Rating Curve= 0 ,0
Exp/Cntr=0.3,0.1

Type RM Length L Ch R = 1 ,4286    ,905,905,905
BEGIN DESCRIPTION:
UNT 136 IN UKCR 2.0
END DESCRIPTION:
XS GIS Cut Line= 3
      3670331.77      10577858.7      3669817.93     10577719.82
      3669404.69     10577688.57
#Sta/Elev= 30
  4544.3  325.82  4553.4  324.79  4599.8  322.33    4677  313.42  4709.1  310.94
  4714.3  309.56    4749  308.15  4754.1  306.28  4778.3  305.48  4887.5  297.32
  4971.2  291.21  4983.1  290.27    4989  284.65  4991.7  284.15    4995  284.65
  5002.3   285.1  5012.6  289.58  5017.8  289.01  5052.5  290.85    5095  291.18
  5139.1  294.02  5145.1  295.45  5225.3  301.72  5265.4  305.43  5270.5  307.16
  5285.5  307.06  5331.1  309.51    5402  313.43  5415.9  312.88    5491     316
#Mann= 8 ,-1 , 0
  4544.3     .16       0  4553.4     .05       0    4677     .12       0
  4778.3     .16       0  4887.5     .12       0    4989     .07       0
    4995     .12       0  5331.1     .05       0
Bank Sta=4971.2,5095
XS Rating Curve= 0 ,0
Exp/Cntr=0.3,0.1

Type RM Length L Ch R = 1 ,3381    ,462,462,462
BEGIN DESCRIPTION:
Mapping XS 76303f5d
END DESCRIPTION:
XS GIS Cut Line= 4
      3670460.64     10577725.94      3670195.01      10577199.9
      3669788.76     10577210.32      3669363.15     10577558.07
#Sta/Elev= 30
  4101.1   321.6  4219.6  315.43  4327.3  307.09  4428.5  300.37  4442.6  297.72
  4687.4  284.89  4815.8  283.97  4885.9  286.44  4954.5  285.52  4985.9   285.5
  4995.9  279.22  5002.9  278.87  5005.7  278.37  5008.9  278.87  5015.9  285.09
  5053.5  284.95  5117.7  284.42  5259.8  289.02  5330.2  293.16  5358.9  297.33
  5387.6  298.06  5408.4  302.11  5430.7  303.25  5437.1  305.93  5451.5   306.7
    5458  309.31  5486.7  312.69  5494.6  311.35  5579.3  316.37  5646.4  315.45
#Mann= 7 ,-1 , 0
  4101.1     .12       0  4327.3     .16       0  4428.5     .05       0
  4954.5     .16       0  5002.9     .07       0  5008.9     .16       0
  5053.5     .05       0
Bank Sta=4985.9,5015.9
XS Rating Curve= 0 ,0
Exp/Cntr=0.3,0.1

Type RM Length L Ch R = 1 ,2919    ,172,172,172
BEGIN DESCRIPTION:
Mapping XS dfee9983
END DESCRIPTION:
XS GIS Cut Line= 5
      3670767.69     10577627.67      3670079.49     10576944.72
      3669785.29     10576808.13      3669543.63     10577007.76
      3669323.45     10577516.27
#Sta/Elev= 30
    3835  308.87  3973.3  297.54  4065.2  299.94  4121.9  296.94  4220.8  293.96
  4284.4  290.13  4305.6  290.57  4553.1  283.56  4663.2  282.63  4715.8  282.75
  4751.1  280.22  4772.3  282.53    4967  282.24  4989.9  279.96  4992.4  277.33
  4995.1  276.83  5012.8  280.84  5608.5  278.97  5719.8  282.04  5790.3  288.94
  5804.6   289.7  5826.4  294.59  5880.9  302.71  5902.7  307.92  5918.6  308.91
  5924.5  310.92    5942  312.53  5947.5  311.04    5971  311.71  5996.5  313.87
#Mann= 6 ,-1 , 0
    3835     .12       0  4121.9     .05       0  4663.2     .16       0
  4989.9     .05       0  4992.4     .16       0  5790.3     .05       0
#XS Ineff= 1 ,-1
 5230.11  5764.2  282.35
Permanent Ineff=
       F
Bank Sta=4989.9,5012.8
XS Rating Curve= 0 ,0
Exp/Cntr=0.3,0.1

Type RM Length L Ch R = 1 ,2747    ,244,244,244
BEGIN DESCRIPTION:
UNT 136 IN UKCR 1.5
END DESCRIPTION:
XS GIS Cut Line= 5
      3670992.38     10577673.83      3670265.41      10576762.4
      3669744.58     10576664.74      3669473.31      10576762.4
      3669212.92     10577565.27
#Sta/Elev= 30
  3529.6  319.59  3577.8  316.65  3605.4   315.4  3611.8  316.99    3655  317.15
  3719.1  313.01  3856.8  298.83  3890.4  295.76  4167.5  287.63    4225  286.46
  4324.4  289.26    4540  283.55  4580.6  281.77  4672.7  277.84    4968  278.96
  4996.4  277.67  5199.9  279.57  5736.6  275.78  5921.3  277.58  6061.9  280.11
  6120.6  287.28  6157.8  289.87  6189.8  296.38  6247.2  299.67  6253.7  302.91
  6268.3  303.42  6317.7  311.44  6322.9  310.58  6349.7  313.84  6357.7  312.66
#Mann= 7 ,-1 , 0
  3529.6     .07       0  3577.8     .12       0  3856.8     .05       0
    4540     .12       0  4580.6     .16       0    4968     .16       0
  6120.6     .05       0
#XS Ineff= 1 ,-1
  5148.3 6077.27  281.79
Permanent Ineff=
       F
Bank Sta=4996.4,5921.3
XS Rating Curve= 0 ,0
Exp/Cntr=0.3,0.1

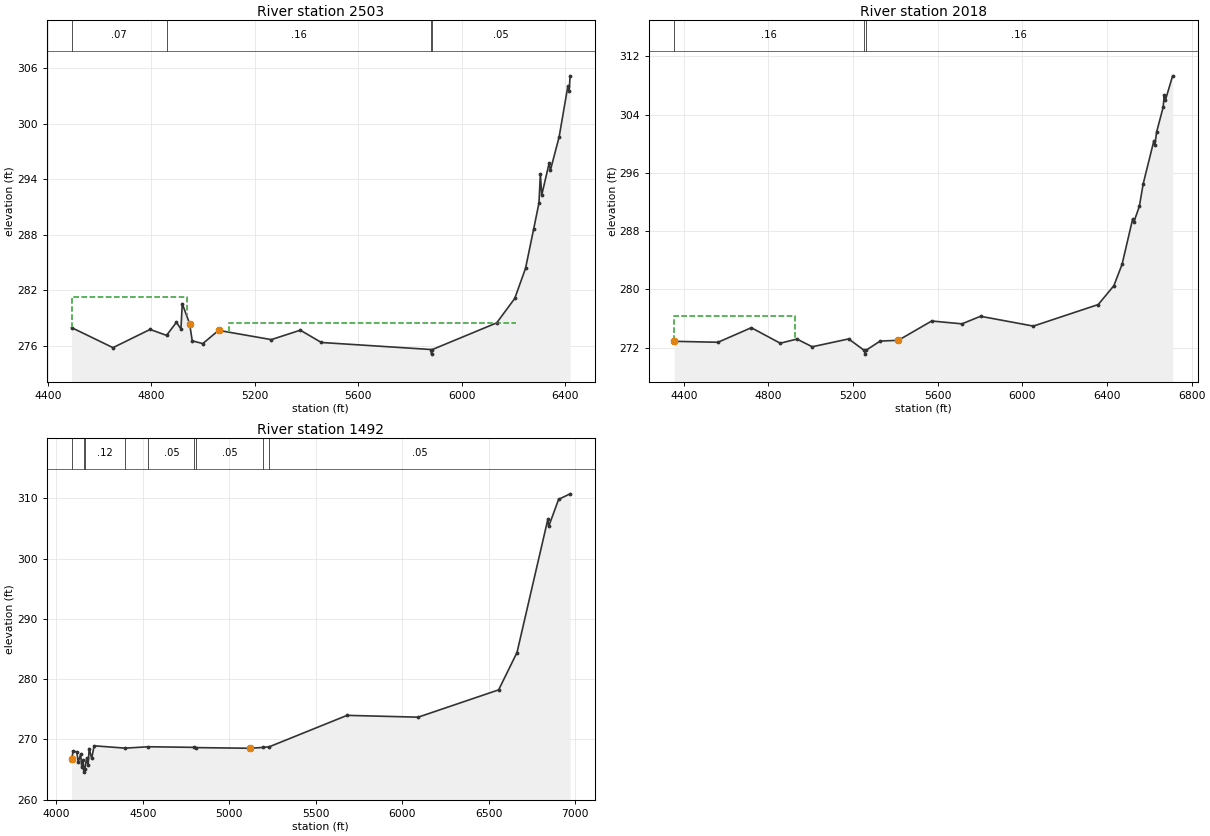
Type RM Length L Ch R = 1 ,2503    ,485,485,485
BEGIN DESCRIPTION:
Mapping XS bccb07de
END DESCRIPTION:
XS GIS Cut Line= 4
      3670447.25      10576403.6      3669480.59     10576592.73
      3669291.46     10577223.15      3669212.82     10577495.77
#Sta/Elev= 30
  4491.7  277.97  4651.7   275.8    4795  277.77  4858.7  277.13  4896.9  278.54
  4914.4  277.82  4919.5  280.55  4947.8  278.41    4958  276.54  4998.8  276.24
  5059.9  277.67  5263.7  276.67  5375.8  277.69  5457.3  276.36  5880.4   275.6
  5883.1   275.1  5886.4   275.6  6134.9  278.48  6204.6  281.12  6246.3  284.38
  6277.5  288.59  6298.3  291.45  6303.7  294.59  6308.9   292.3  6337.4  295.73
  6342.6     295  6376.2  298.59  6409.9  304.07  6415.1   303.6  6418.6   305.2
#Mann= 4 ,-1 , 0
  4491.7     .07       0  4858.7     .16       0  5880.4     .03       0
  5886.4     .05       0
#XS Ineff= 2 ,-1
 4453.12 4938.92  281.25 5099.43 6208.81  278.46
Permanent Ineff=
       F       F
Bank Sta=4947.8,5059.9
XS Rating Curve= 0 ,0
Exp/Cntr=0.3,0.1

Type RM Length L Ch R = 1 ,2018    ,526,526,526
BEGIN DESCRIPTION:
Mapping XS ddaf3c91
END DESCRIPTION:
XS GIS Cut Line= 3
      3670352.67     10575694.38      3669443.81     10576340.57
       3669186.4     10577554.11
#Sta/Elev= 30
  4354.4  272.87  4561.7  272.74  4719.2  274.74  4855.7  272.61  4934.8  273.18
    5007  272.12  5179.1   273.2  5253.6  271.61  5256.3  271.11  5259.6  271.61
  5327.9   272.9    5414  273.01  5571.4  275.66  5714.5  275.27  5802.2  276.31
  6051.9  274.96  6358.5  277.92  6432.4  280.51    6471  283.43  6521.5  289.71
  6526.6  289.24  6552.8   291.4  6571.1  294.52  6620.8  300.34  6625.9   299.8
  6634.5  301.64  6665.2  305.01  6670.4  306.65  6675.5  305.96  6710.1  309.34
#Mann= 3 ,-1 , 0
  4354.4     .16       0  5253.6     .03       0  5259.6     .16       0
#XS Ineff= 1 ,-1
 4327.27 4925.57  276.34
Permanent Ineff=
       F
Bank Sta=4354.4,5414
XS Rating Curve= 0 ,0
Exp/Cntr=0.3,0.1

Type RM Length L Ch R = 1 ,1492    ,0,0,0
BEGIN DESCRIPTION:
UNT 136 IN UKCR 1.0
END DESCRIPTION:
XS GIS Cut Line= 3
      3670143.18     10575180.43      3669288.78     10575887.31
      3669165.92     10577656.44
#Sta/Elev= 30
  4088.1  266.71  4097.4  268.07  4118.7  267.91  4126.1  266.22  4140.4  267.52
  4146.9  265.36  4154.7   266.5  4158.2  265.07    4161  264.57  4164.2  265.07
  4175.5   266.9  4183.4  265.67  4189.9  268.48  4204.2  266.84  4218.5  268.94
  4397.7  268.55  4532.3  268.78  4797.6  268.68  4808.9  268.64  5119.9  268.53
  5195.5  268.67  5232.2  268.79  5681.1  273.99    6092  273.69  6557.2  278.22
  6663.4  284.42  6841.9  306.54  6846.9  305.36    6904  309.83  6970.4  310.75
#Mann= 9 ,-1 , 0
  4088.1     .12       0  4158.2     .03       0  4164.2     .12       0
  4397.7     .07       0  4532.3     .05       0  4797.6     .07       0
  4808.9     .05       0  5195.5     .07       0  5232.2     .05       0
Bank Sta=4088.1,5119.9
XS Rating Curve= 0 ,0
Exp/Cntr=0.3,0.1

Chan Stop Cuts=-1
Use User Specified Reach Order=0
Composite Channel Slope=5