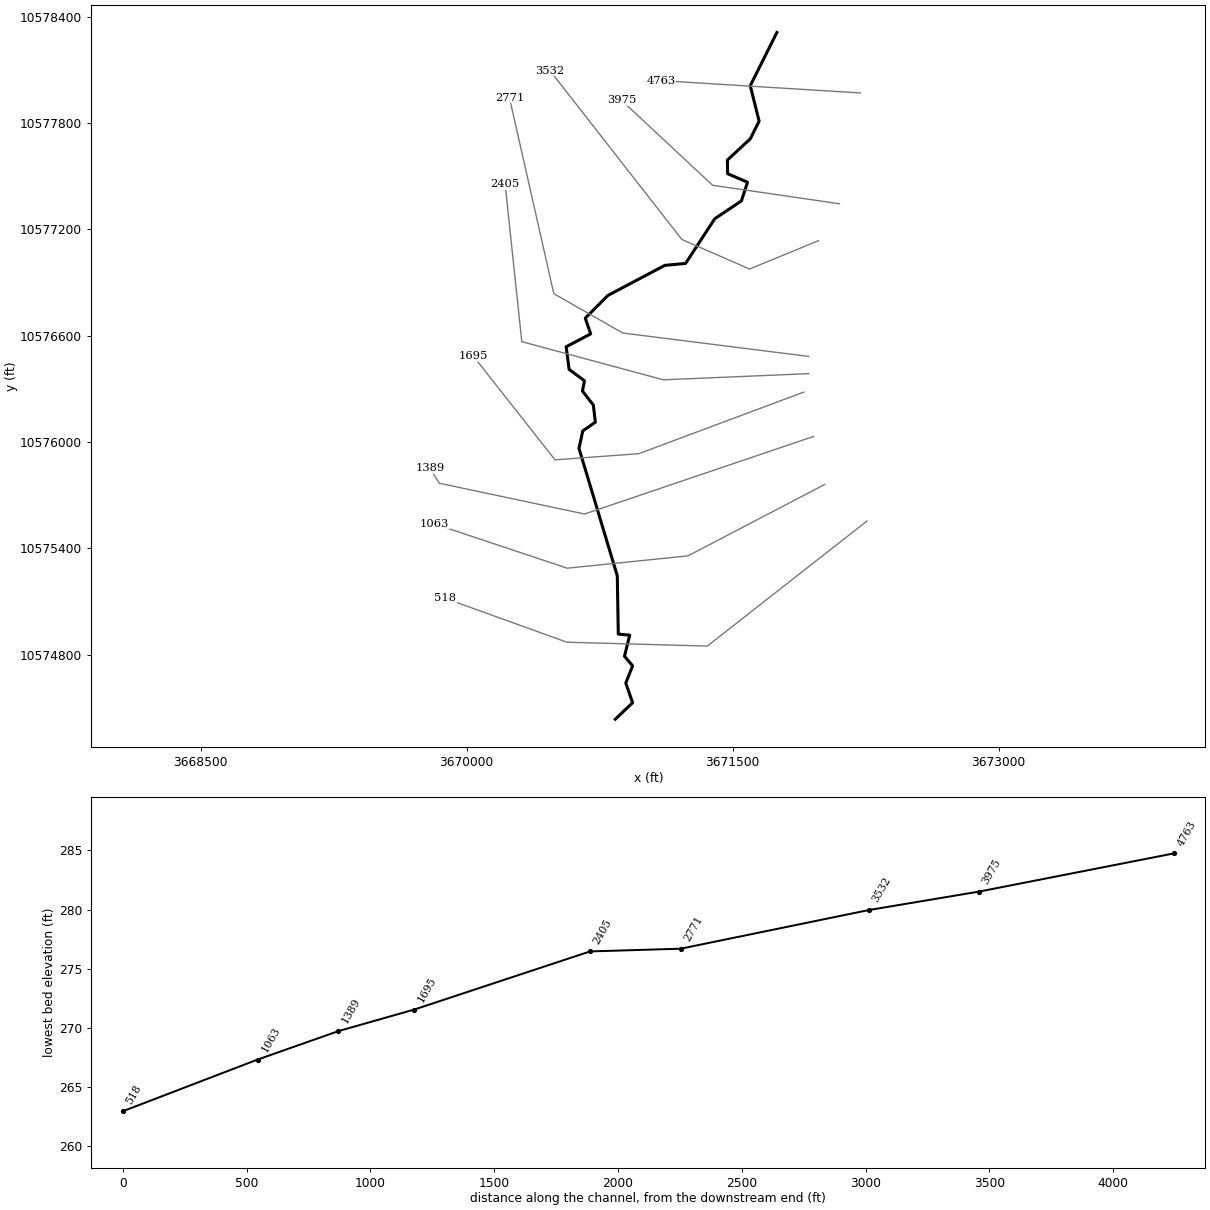
--- UNT 138 IN UKCR.prj (project) ---

Proj Title=UNT 138 IN UKCR Base Level Engineering
Current Plan=p01
Default Exp/Contr=0.3,0.1
English Units
Geom File=g01
Flow File=f01
Plan File=p01
Y Axis Title=Elevation
X Axis Title(PF)=Main Channel Distance
X Axis Title(XS)=Station
BEGIN DESCRIPTION:
UNT 138 IN UKCR
END DESCRIPTION:
DSS Export Rating Curves= 0
DSS Export Rating Curve Sorted= 0
DSS Export Volume Flow Curves= 0
DXF OffsetX= 0
DXF OffsetY= 0
DXF ScaleX= 1
DXF ScaleY= 10

--- UNT 138 IN UKCR.p01 (plan) ---

Plan Title=Multiple Run
Program Version=4.10
Short Identifier=Multiple
Geom File=g01
Flow File=f01
Subcritical Flow
K Sum by GR= 0
Std Step Tol= 0.01
Critical Tol= 0.01
Num of Std Step Trials= 20
Max Error Tol= 0.3
Flow Tol Ratio= 0.001
Split Flow NTrial= 30
Split Flow Tol= 0.02
Split Flow Ratio= 0.02
Log Output Level= 0
Friction Slope Method= 1
Unsteady Friction Slope Method= 2
Unsteady Bridges Friction Slope Method= 1
Parabolic Critical Depth
Global Vel Dist= 1 , 1 , 1
Global Log Level= 0
CheckData=True
Encroach Param=-1 ,0,0, 0
BEGIN DESCRIPTION:
Multiple Run
END DESCRIPTION:
Computation Interval=1HOUR
Output Interval=1HOUR
Run HTab= 0
Run UNet= 0
Run PostProcess= 0
Run WQNet= 0
UNET Theta= 1
UNET Theta Warmup= 1
UNET ZTol= 0.02
UNET ZSATol= 0.05
UNET MxIter= 20
UNET MaxInSteps= 0
UNET DtIC= 0
UNET DtMin= 0
UNET MaxCRTS= 20
UNET WFStab= 2
UNET SFStab= 1
UNET WFX= 1
UNET SFX= 1
UNET DSS MLevel= 4
UNET DZMax Abort= 100
UNET Convert EG Bridges= 0
UNET Use Existing IB Tables=-1
UNET Froude Reduction=False
UNET Froude Limit= 1
UNET Froude Power= 10
UNET Time Slicing=0,0, 5
UNET Junction Losses=0
Instantaneous Interval=1HOUR
Write IC File= 0
Write IC File at Sim End=0
Echo Input=False
Echo Parameters=False
Echo Output=False
Write Detailed= 0
WQ AD Non Conservative
WQ ULTIMATE=-1
WQ Max Comp Step=1HOUR
WQ Output Interval=15MIN
WQ Output Selected Increments= 0
WQ Output face flow=0
WQ Output face velocity=0
WQ Output face area=0
WQ Output face dispersion=0
WQ Output cell volume=0
WQ Output cell surface area=0
WQ Output cell continuity=0
WQ Output cumulative cell continuity=0
WQ Output face conc=0
WQ Output face dconc_dx=0
WQ Output face courant=0
WQ Output face peclet=0
WQ Output face adv mass=0
WQ Output face disp mass=0
WQ Output cell mass=0
WQ Output cell source sink temp=0
WQ Output cell source sink nsm=0
WQ Output MaxMinRange=-1
WQ Daily Max Min Mean=-1
WQ Daily Range=0
WQ Daily Time=0
WQ Create Restart=0
WQ Fixed Restart=0
WQ System Summary=0
WQ Use Fixed Temperature=0
Sorting and Armoring Iterations= 10
XS Update Threshold= 0.02
Hydraulics Update Threshold= 0.02
Energy Slope Method= 1
Volume Change Method= 0
XS Weighting Method= 0
Number of US Weighted Cross Sections= 1
Number of DS Weighted Cross Sections= 1
Upstream XS Weight=0.25
Main XS Weight=0.5
Downstream XS Weight=0.25
Number of DS XS's Weighted with US Boundary= 1
Upstream Boundary Weight= 1
Weight of XSs Associated with US Boundary= 0
Number of US XS's Weighted with DS Boundary= 1
Downstream Boundary Weight= 0.5
Weight of XSs Associated with DS Boundary= 0.5
Sediment Output Level= 4
Mass or Volume Output= 0
Output Increment Type= 1
Profile and TS Output Increment= 10
XS Output Flag= 0
XS Output Increment= 10
Disregard all LS=0
Disregard all Conn=0
Disregard all Breaches=0
Disregard all Pumps=0

--- UNT 138 IN UKCR.f01 (steady flow) ---

Flow Title=Multiple
Number of Profiles=7
Profile Names=10-year,25-year,50-year,1pct_min,100-year,1pct_plu,500-year
River Rch & RM= UNT 138 IN UKCR,Reach-1,4763
     357     469     558     488     661     893     929
Boundary for River Rch & Prof#=UNT 138 IN UKCR,Reach-1,1
Up Type=0
Dn Type=3
Dn Slope=0.005
Boundary for River Rch & Prof#=UNT 138 IN UKCR,Reach-1,2
Up Type=0
Dn Type=3
Dn Slope=0.005
Boundary for River Rch & Prof#=UNT 138 IN UKCR,Reach-1,3
Up Type=0
Dn Type=3
Dn Slope=0.005
Boundary for River Rch & Prof#=UNT 138 IN UKCR,Reach-1,4
Up Type=0
Dn Type=3
Dn Slope=0.005
Boundary for River Rch & Prof#=UNT 138 IN UKCR,Reach-1,5
Up Type=0
Dn Type=3
Dn Slope=0.005
Boundary for River Rch & Prof#=UNT 138 IN UKCR,Reach-1,6
Up Type=0
Dn Type=3
Dn Slope=0.005
Boundary for River Rch & Prof#=UNT 138 IN UKCR,Reach-1,7
Up Type=0
Dn Type=3
Dn Slope=0.005

--- UNT 138 IN UKCR.g01 (geometry) ---

Geom Title=Existing Conditions
Program Version=4.10

River Reach=UNT 138 IN UKCR ,Reach-1
Reach XY= 30
      3671749.61     10578310.19      3671599.61     10578010.19
      3671649.61     10577810.19      3671599.61     10577710.19
      3671470.75      10577591.1      3671471.79     10577514.02
      3671584.29     10577465.58      3671549.61     10577360.19
      3671399.61     10577260.19      3671234.82     10577007.77
      3671117.63     10576996.83       3670796.5       10576827.
      3670668.92     10576698.92      3670699.61     10576610.19
      3670561.28     10576537.81      3670577.95     10576410.03
       3670664.5       10576346.        3670653.       10576288.
       3670714.5       10576209.      3670725.75       10576112.
        3670655.       10576063.       3670633.5       10575965.
      3670849.61     10575245.66      3670855.25       10574917.
      3670919.75       10574911.      3670890.25       10574792.
        3670936.       10574738.       3670897.5       10574641.
        3670936.       10574530.       3670838.5       10574437.

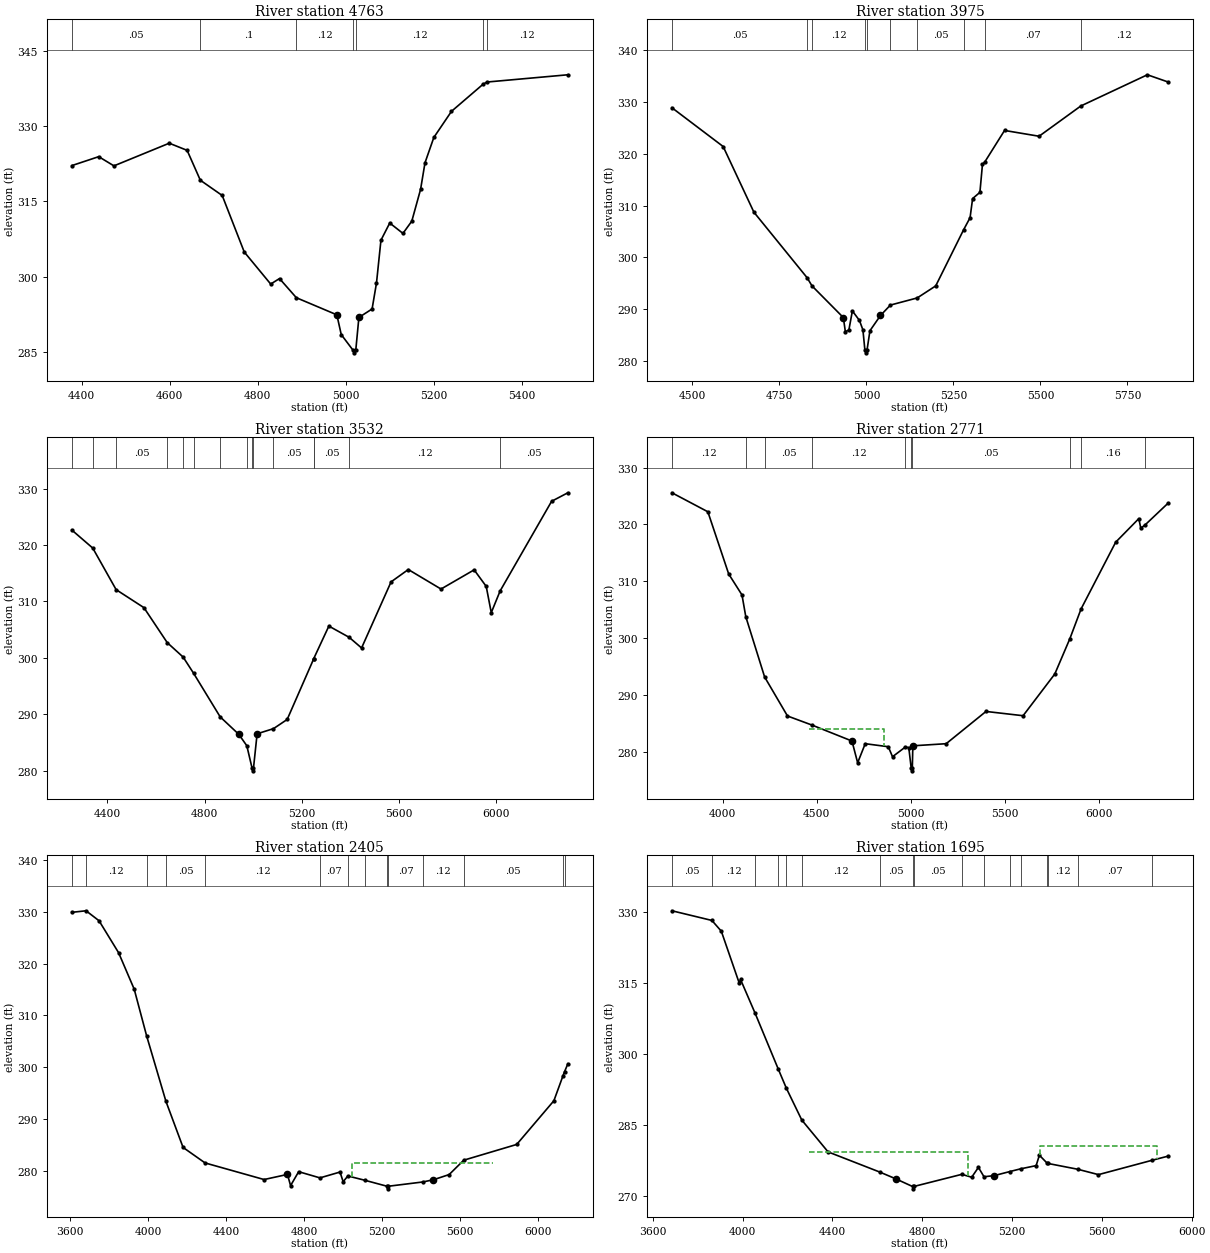
Type RM Length L Ch R = 1 ,4763    ,788,788,788
BEGIN DESCRIPTION:
UNT 138 IN UKCR 8.0
END DESCRIPTION:
XS GIS Cut Line= 2
      3672220.73     10577969.32      3671095.67     10578038.77
#Sta/Elev= 30
  4377.7  322.17  4438.9  323.96  4473.5  322.12  4599.2  326.65  4639.8  325.22
  4669.8  319.25  4719.5   316.2  4769.6   304.9  4829.7  298.49  4849.7  299.59
    4888  295.76    4980  292.34    4990  288.39    5017  285.24  5019.8  284.74
    5023  285.24  5030.1  291.82  5060.1  293.51  5070.1  298.71  5080.2  307.25
  5100.2  310.69  5130.2  308.62  5150.3  311.06  5170.3  317.43  5180.3  322.73
  5200.4   327.8  5240.5  333.02  5312.4  338.45  5321.2  338.88  5504.9  340.33
#Mann= 7 ,-1 , 0
  4377.7     .05       0  4669.8      .1       0    4888     .12       0
    5017     .07       0    5023     .12       0  5312.4      .1       0
  5321.2     .12       0
Bank Sta=4980,5030.1
XS Rating Curve= 0 ,0
Exp/Cntr=0.3,0.1

Type RM Length L Ch R = 1 ,3975    ,443,443,443
BEGIN DESCRIPTION:
UNT 138 IN UKCR 7.0
END DESCRIPTION:
XS GIS Cut Line= 3
      3672102.67     10577344.32      3671387.37     10577448.49
      3670873.46     10577927.68
#Sta/Elev= 30
  4441.1  328.92  4588.3  321.42  4676.6  308.72  4829.4  296.05  4843.7  294.45
  4933.6  288.34  4939.4  285.62  4949.5  285.92  4959.6  289.62  4979.8  287.79
  4989.9  285.95  4995.6  282.01  4998.4  281.51  5001.6  282.01  5010.1  285.79
  5040.4  288.74  5068.9  290.75  5145.9  292.13  5199.1  294.46  5279.1   305.3
  5297.8  307.65  5305.1  311.35  5326.1  312.56  5333.4  317.96  5339.9  318.41
  5396.9  324.53  5496.1  323.41    5616  329.26  5807.3   335.3  5866.6  333.91
#Mann= 10 ,-1 , 0
  4441.1     .05       0  4829.4      .1       0  4843.7     .12       0
  4995.6     .07       0  5001.6     .12       0  5068.9     .16       0
  5145.9     .05       0  5279.1     .12       0  5339.9     .07       0
    5616     .12       0
Bank Sta=4933.6,5040.4
XS Rating Curve= 0 ,0
Exp/Cntr=0.3,0.1

Type RM Length L Ch R = 1 ,3532    ,761,761,761
BEGIN DESCRIPTION:
UNT 138 IN UKCR 6.0
END DESCRIPTION:
XS GIS Cut Line= 4
      3671984.64     10577136.01      3671595.71     10576976.27
      3671213.76     10577142.93      3670470.68     10578094.36
#Sta/Elev= 30
  4252.9  322.67  4339.4  319.46  4435.7  312.09  4550.2   308.9  4646.2   302.7
  4711.9  300.13  4754.8  297.27  4864.5  289.53  4941.1  286.44  4974.3  284.41
  4995.8  280.46  4998.5  279.96  5001.8  280.46  5016.7  286.53  5084.1  287.44
  5140.6  289.07  5249.6  299.79  5249.9  299.85  5312.4  305.63    5396  303.64
  5447.2  301.75  5568.8  313.47  5639.8  315.66  5774.6   312.2  5911.1   315.6
  5960.9  312.67  5981.7  308.01  6018.3  311.87  6230.4  327.76  6297.3  329.27
#Mann= 15 ,-1 , 0
  4252.9     .05       0  4339.4     .16       0  4435.7     .05       0
  4646.2     .16       0  4711.9     .05       0  4754.8     .16       0
  4864.5     .12       0  4974.3     .16       0  4995.8     .07       0
  5001.8     .16       0  5084.1     .05       0  5249.6     .12       0
  5249.9     .05       0    5396     .12       0  6018.3     .05       0
Bank Sta=4941.1,5016.7
XS Rating Curve= 0 ,0
Exp/Cntr=0.3,0.1

Type RM Length L Ch R = 1 ,2771    ,366,366,366
BEGIN DESCRIPTION:
UNT 138 IN UKCR 5.0
END DESCRIPTION:
XS GIS Cut Line= 4
      3671928.99     10576483.22      3670880.43     10576615.16
      3670491.54     10576837.38      3670241.55      10577941.5
#Sta/Elev= 30
  3729.9  325.57  3920.8  322.23  4031.6  311.29  4102.2  307.61  4122.4  303.79
  4222.5  293.19  4344.1  286.33  4476.3  284.71  4686.8  281.93    4717  278.11
  4757.3  281.46  4879.8  280.93  4902.4  279.17  4970.3  280.87  4988.8  280.78
  5001.6  277.19  5004.4  276.69  5007.6  277.19  5010.4  281.09  5187.5  281.46
  5399.2  287.13  5596.4  286.38  5764.9  293.71  5844.8   299.9  5904.6  305.15
  6088.5  316.88  6211.6  321.03    6222  319.34  6246.5  319.97  6366.7  323.73
#Mann= 10 ,-1 , 0
  3729.9     .12       0  4122.4     .16       0  4222.5     .05       0
  4476.3     .12       0  4970.3     .05       0  5001.6     .03       0
  5007.6     .05       0  5844.8     .12       0  5904.6     .16       0
  6246.5     .05       0
#XS Ineff= 1 ,-1
 4457.95 4858.52  284.07
Permanent Ineff=
       F
Bank Sta=4686.8,5010.4
XS Rating Curve= 0 ,0
Exp/Cntr=0.3,0.1

Type RM Length L Ch R = 1 ,2405    ,710,710,710
BEGIN DESCRIPTION:
Mapping XS f7bea754
END DESCRIPTION:
XS GIS Cut Line= 4
      3671929.07     10576385.99       3671109.6     10576351.27
      3670310.98     10576566.55      3670216.95     10577454.76
#Sta/Elev= 30
  3610.2  329.96  3683.3  330.26  3749.8  328.33  3849.9  322.15  3929.9  315.09
  3993.7  306.03  4092.5  293.38  4180.2  284.47  4292.9  281.47    4595  278.26
  4714.8  279.25  4730.7  277.08  4772.2  279.78  4881.2  278.58  4983.9  279.71
    5000  277.83  5024.1  278.95  5111.9  278.11  5224.9  276.96  5227.6  276.46
  5230.9  276.96  5408.2  277.79  5462.3  278.22  5542.8  279.22  5617.4     282
  5888.8  285.05  6079.3  293.51  6125.8  298.33    6134  299.14  6150.7  300.65
#Mann= 14 ,-1 , 0
  3610.2     .05       0  3683.3     .12       0  3993.7     .16       0
  4092.5     .05       0  4292.9     .12       0  4881.2     .07       0
  5024.1     .12       0  5111.9     .07       0  5224.9     .07       0
  5230.9     .07       0  5408.2     .12       0  5617.4     .05       0
  6125.8     .16       0    6134     .05       0
#XS Ineff= 1 ,-1
 5047.73 5768.75  281.53
Permanent Ineff=
       F
Bank Sta=4714.8,5462.3
XS Rating Curve= 0 ,0
Exp/Cntr=0.3,0.1

Type RM Length L Ch R = 1 ,1695    ,306,306,306
BEGIN DESCRIPTION:
UNT 138 IN UKCR 4.0
END DESCRIPTION:
XS GIS Cut Line= 4
      3671901.27     10576281.83      3670970.71      10575934.6
      3670498.48     10575899.88      3670038.66     10576483.59
#Sta/Elev= 30
  3684.8  330.26  3862.8  328.22  3904.7  325.95    3985  314.93  3990.3  315.76
  4055.1  308.65  4159.1  296.76  4194.7  292.77  4263.2  286.08  4380.3  279.35
  4610.7  275.09  4681.1  273.68  4756.4  272.05  4759.1  271.55  4762.4  272.05
    4976  274.61  5020.1     274  5050.1  276.08  5074.9   274.1  5120.3  274.34
  5189.3  275.19  5237.6  275.77  5307.1  276.45  5321.6  278.65  5357.4  276.91
  5358.7  276.92    5492  275.69  5584.8  274.55  5822.9  277.57  5894.6  278.45
#Mann= 17 ,-1 , 0
  3684.8     .05       0  3862.8     .12       0  4055.1     .16       0
  4159.1     .05       0  4194.7     .16       0  4263.2     .12       0
  4610.7     .05       0  4756.4     .07       0  4762.4     .05       0
    4976     .12       0  5074.9     .07       0  5189.3     .05       0
  5237.6     .07       0  5357.4     .05       0  5358.7     .12       0
    5492     .07       0  5822.9     .05       0
#XS Ineff= 2 ,-1
 4296.88 5002.84   279.4 5322.44 5845.17  280.56
Permanent Ineff=
       F       F
Bank Sta=4681.1,5120.3
XS Rating Curve= 0 ,0
Exp/Cntr=0.3,0.1

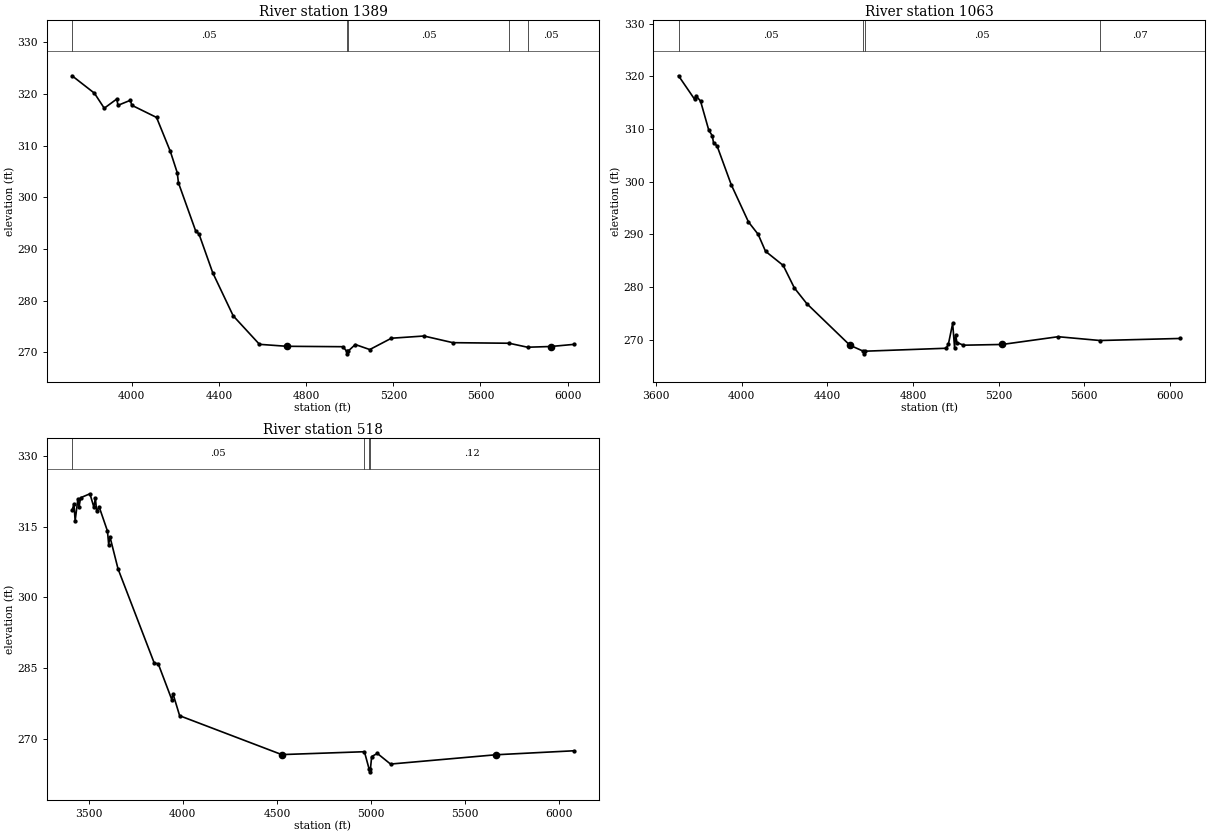
Type RM Length L Ch R = 1 ,1389    ,326,326,326
BEGIN DESCRIPTION:
UNT 138 IN UKCR 3.0
END DESCRIPTION:
XS GIS Cut Line= 4
       3671956.8     10576031.82      3670665.15     10575594.32
      3669845.71     10575767.93      3669791.59     10575853.61
#Sta/Elev= 30
  3725.8  323.53  3828.4  320.16  3873.5  317.25  3931.1  319.04  3936.4  317.81
  3993.9   318.8  3999.2  317.84  4113.5  315.47  4176.8  308.89  4208.5  304.77
  4213.9  302.83    4293  293.51  4308.2  292.92    4371  285.45  4465.3  277.08
  4585.7  271.57  4711.4  271.19  4968.7  271.11  4985.9  270.23  4988.7  269.73
  4991.9  270.23  5025.6  271.53  5091.9  270.56  5191.2  272.75  5340.5  273.18
  5473.4  271.89  5731.3  271.78    5816  271.01  5922.6  271.15  6028.5  271.56
#Mann= 5 ,-1 , 0
  3725.8     .05       0  4985.9     .03       0  4991.9     .05       0
  5731.3     .07       0    5816     .05       0
Bank Sta=4711.4,5922.6
XS Rating Curve= 0 ,0
Exp/Cntr=0.3,0.1

Type RM Length L Ch R = 1 ,1063    ,545,545,545
BEGIN DESCRIPTION:
UNT 138 IN UKCR 2.0
END DESCRIPTION:
XS GIS Cut Line= 4
      3672019.29     10575760.97      3671248.48     10575358.21
      3670567.93     10575288.77      3669817.97     10575538.75
#Sta/Elev= 30
  3704.5  320.11  3779.6  315.65  3785.3  316.34  3807.3  315.31  3845.9  309.77
  3862.1  308.73  3867.9   307.4  3884.4  306.81  3950.6  299.45  4031.3  292.36
  4076.5  290.01  4110.8   286.8  4193.5  284.11  4245.7  279.83  4303.9  276.85
  4505.2  268.96  4567.7  267.83  4570.5  267.33  4573.7  267.83    4955  268.39
  4965.1  269.14  4985.2   273.1  4994.1   268.5  4999.1  270.85  5005.3  269.48
  5035.4  268.97  5216.4  269.11  5477.9  270.58  5673.8  269.86  6048.8  270.25
#Mann= 4 ,-1 , 0
  3704.5     .05       0  4567.7     .03       0  4573.7     .05       0
  5673.8     .07       0
Bank Sta=4505.2,5216.4
XS Rating Curve= 0 ,0
Exp/Cntr=0.3,0.1

Type RM Length L Ch R = 1 ,518     ,0,0,0
BEGIN DESCRIPTION:
UNT 138 IN UKCR 1.0
END DESCRIPTION:
XS GIS Cut Line= 4
      3672258.06     10575554.85      3671357.43     10574849.53
      3670565.32     10574871.23       3669878.9     10575118.95
#Sta/Elev= 30
  3411.3  318.45  3421.3  319.81  3427.7  316.25  3442.1  320.83  3448.5  319.21
  3456.6  321.13  3506.3  321.97  3527.1  319.13  3535.2  321.03  3541.6  318.39
  3556.1  319.09  3599.4  314.05  3605.8  311.19  3612.6  312.85  3655.5  306.04
  3848.1  286.02  3868.9  285.91  3941.2  278.29  3947.6  279.52  3982.8  274.87
  4525.3  266.62  4964.6  267.23  4990.2  263.46    4993  262.96  4996.2  263.46
  5003.2   266.2  5033.2  266.87  5103.3  264.61    5662  266.58  6077.4  267.43
#Mann= 4 ,-1 , 0
  3411.3     .05       0  4964.6     .12       0  4990.2     .07       0
  4996.2     .12       0
Bank Sta=4525.3,5662
XS Rating Curve= 0 ,0
Exp/Cntr=0.3,0.1

Chan Stop Cuts=-1
Use User Specified Reach Order=0
Composite Channel Slope=5