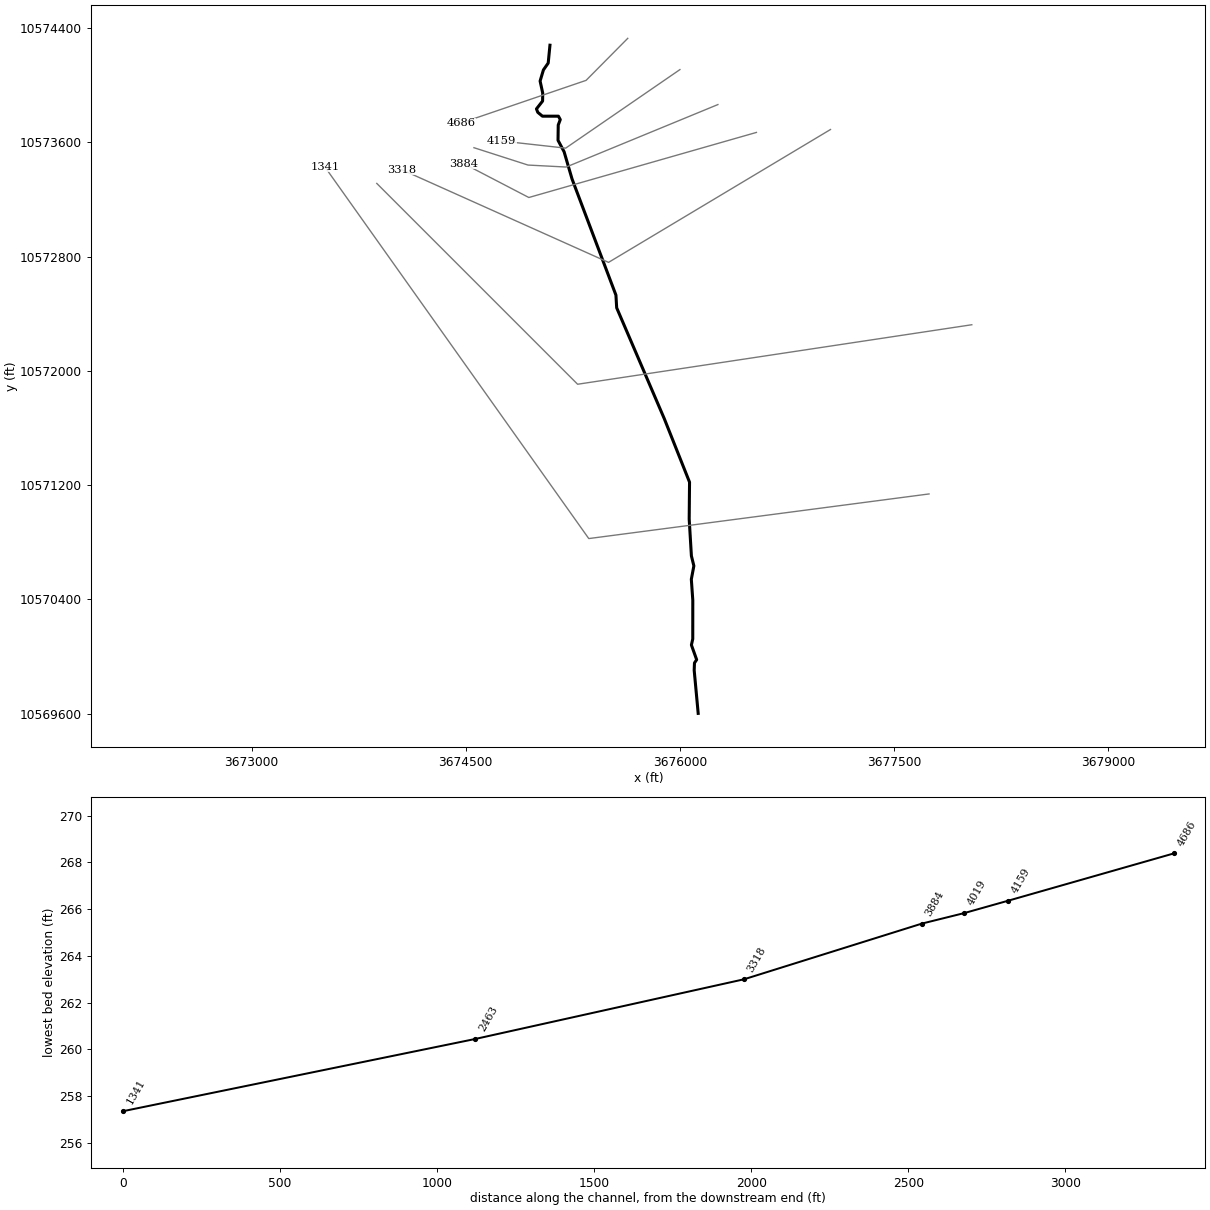
--- UNT 139 IN UKCR.prj (project) ---

Proj Title=UNT 139 IN UKCR Base Level Engineering
Current Plan=p01
Default Exp/Contr=0.3,0.1
English Units
Geom File=g01
Flow File=f01
Plan File=p01
BEGIN DESCRIPTION:
UNT 139 IN UKCR
END DESCRIPTION:

--- UNT 139 IN UKCR.p01 (plan) ---

Plan Title=Multiple Run
Short Identifier=Multiple
Geom File=g01
Flow File=f01
Subcritical Flow
K Sum by GR= 0
Std Step Tol= 0.01
Critical Tol= 0.01
Num of Std Step Trials= 20
Max Error Tol= 0.3
Flow Tol Ratio= 0.001
Split Flow NTrial= 30
Split Flow Tol= 0.02
Split Flow Ratio= 0.02
Log Output Level= 0
Friction Slope Method= 1
Unsteady Friction Slope Method= 2
Unsteady Bridges Friction Slope Method= 1
Parabolic Critical Depth
Global Vel Dist=  1 , 1 , 1
Global Log Level= 0
CheckData=True
Encroach Param= -1, 0, 0, 0
BEGIN DESCRIPTION:
Multiple Run
END DESCRIPTION:

--- UNT 139 IN UKCR.f01 (steady flow) ---

Flow Title=Multiple
Number of Profiles=7
Profile Names=10-year,25-year,50-year,1pct_min,100-year,1pct_plu,500-year
River Rch & RM= UNT 139 IN UKCR,Reach-1,4686
     858    1192    1475    1339    1810    2448    2741
Boundary for River Rch & Prof#=UNT 139 IN UKCR,Reach-1,1
Up Type=0
Dn Type=3
Dn Slope=0.005
Boundary for River Rch & Prof#=UNT 139 IN UKCR,Reach-1,2
Up Type=0
Dn Type=3
Dn Slope=0.005
Boundary for River Rch & Prof#=UNT 139 IN UKCR,Reach-1,3
Up Type=0
Dn Type=3
Dn Slope=0.005
Boundary for River Rch & Prof#=UNT 139 IN UKCR,Reach-1,4
Up Type=0
Dn Type=3
Dn Slope=0.005
Boundary for River Rch & Prof#=UNT 139 IN UKCR,Reach-1,5
Up Type=0
Dn Type=3
Dn Slope=0.005
Boundary for River Rch & Prof#=UNT 139 IN UKCR,Reach-1,6
Up Type=0
Dn Type=3
Dn Slope=0.005
Boundary for River Rch & Prof#=UNT 139 IN UKCR,Reach-1,7
Up Type=0
Dn Type=3
Dn Slope=0.005

--- UNT 139 IN UKCR.g01 (geometry) ---

Geom Title=Existing Conditions

River Reach=UNT 139 IN UKCR,Reach-1
Reach XY= 30
      3675089.50     10574281.00      3675077.25     10574156.00
      3675043.75     10574108.00      3675020.50     10574030.00
      3675038.75     10573946.00      3675038.00     10573890.00
      3674995.00     10573835.00      3675004.25     10573811.00
      3675036.75     10573784.00      3675148.75     10573784.00
      3675161.75     10573760.00      3675147.50     10573722.00
      3675146.00     10573615.00      3675188.50     10573535.00
      3675244.25     10573344.00      3675551.50     10572531.00
      3675556.75     10572442.00      3675890.00     10571666.00
      3676067.00     10571221.00      3676064.50     10570963.00
      3676080.00     10570705.00      3676097.25     10570635.00
      3676079.50     10570541.00      3676089.75     10570395.00
      3676089.50     10570123.00      3676080.00     10570081.00
      3676116.75     10569978.00      3676101.50     10569955.00
      3676099.50     10569904.00      3676127.50     10569602.00

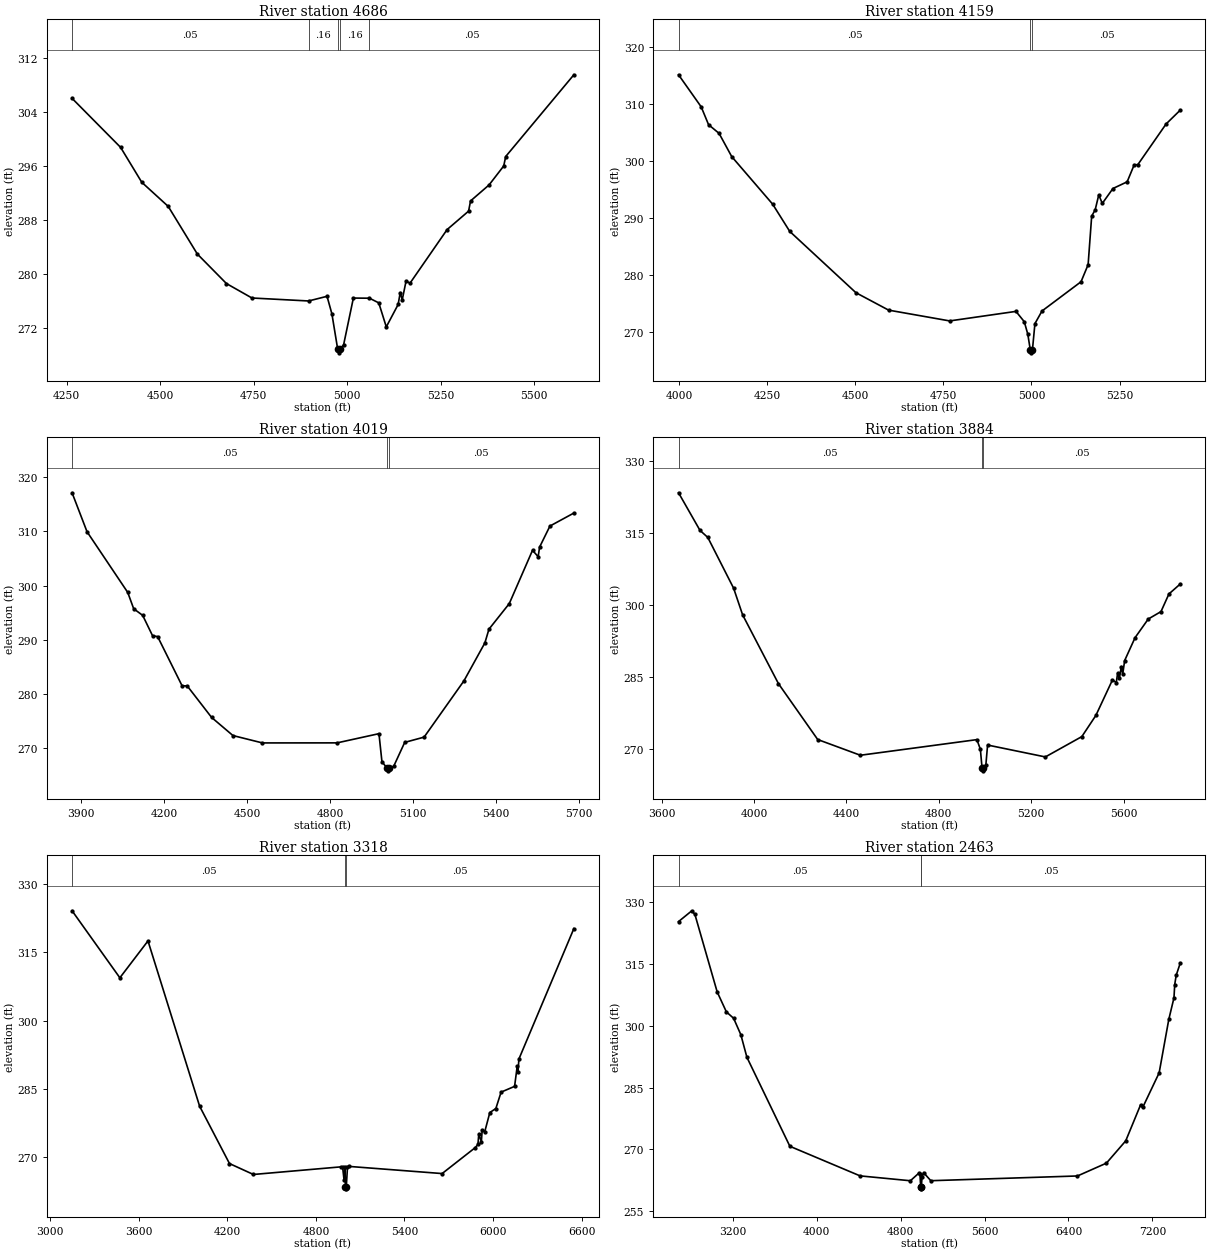
Type RM Length L Ch R = 1,4686,527,527,527
BEGIN DESCRIPTION:
UNT 139 IN UKCR 6.0
END DESCRIPTION:
XS GIS Cut Line= 3
      3675634.27     10574329.12      3675342.60     10574034.84
      3674465.02     10573735.37
#Sta/Elev= 30
  4264.4  306.06  4394.2  298.80  4450.8  293.63  4521.5  290.06  4599.3  283.01
  4677.1  278.64  4745.3  276.50  4896.7  276.06  4946.1  276.75  4959.1  274.15
  4974.7  268.88  4977.5  268.38  4980.7  268.88  4990.4  269.57  5016.5  276.49
  5059.5  276.47  5084.4  275.78  5104.5  272.22  5136.2  275.54  5141.8  277.31
  5147.1  276.22  5157.4  279.01  5167.9  278.69  5267.1  286.63  5324.5  289.36
  5329.8  290.87  5379.3  293.24  5418.5  296.05  5423.8  297.45  5606.0  309.55
#Mann=5,-1,0
  4264.4    0.05       0  4896.7    0.16       0  4974.7    0.07       0
  4980.7    0.16       0  5059.5    0.05       0
Bank Sta=4974.7,4980.7
Exp/Cntr=0.3,0.1

Type RM Length L Ch R = 1,4159,140,140,140
BEGIN DESCRIPTION:
UNT 139 IN UKCR 5.0
END DESCRIPTION:
XS GIS Cut Line= 3
      3675999.61     10574110.19      3675199.61     10573560.19
      3674749.60     10573610.19
#Sta/Elev= 30
  3998.7  315.06  4063.0  309.44  4083.9  306.32  4113.7  304.80  4149.6  300.73
  4265.7  292.40  4314.2  287.63  4502.0  276.89  4594.7  273.84  4767.9  271.95
  4956.0  273.62  4979.6  271.81  4989.6  269.62  4996.7  266.86  4999.5  266.36
  5002.7  266.86  5009.8  271.48  5029.9  273.69  5140.6  278.81  5160.7  281.80
  5170.8  290.30  5180.8  291.42  5190.9  294.02  5200.9  292.53  5231.1  295.14
  5271.4  296.31  5291.5  299.30  5301.6  299.31  5382.0  306.45  5422.3  308.88
#Mann=3,-1,0
  3998.7    0.05       0  4996.7    0.03       0  5002.7    0.05       0
Bank Sta=4996.7,5002.7
Exp/Cntr=0.3,0.1

Type RM Length L Ch R = 1,4019,135,135,135
BEGIN DESCRIPTION:
Mapping XS c94181bc
END DESCRIPTION:
XS GIS Cut Line= 4
      3676265.65     10573865.35      3675203.11     10573427.83
      3674935.75     10573441.72      3674557.30     10573563.24
#Sta/Elev= 30
  3867.0  317.14  3921.1  309.95  4068.2  298.76  4089.8  295.74  4122.3  294.52
  4158.2  290.74  4176.3  290.61  4264.8  281.52  4283.4  281.50  4371.4  275.69
  4448.7  272.34  4555.3  270.98  4825.2  270.99  4976.6  272.69  4987.4  267.51
  5006.1  266.33  5008.8  265.83  5012.1  266.33  5029.6  266.64  5069.7  271.08
  5139.8  272.05  5283.8  282.43  5359.6  289.44  5374.3  291.97  5447.8  296.69
  5531.8  306.52  5552.2  305.35  5557.5  307.13  5594.8  311.00  5681.3  313.40
#Mann=3,-1,0
  3867.0    0.05       0  5006.1    0.03       0  5012.1    0.05       0
Bank Sta=5006.1,5012.1
Exp/Cntr=0.3,0.1

Type RM Length L Ch R = 1,3884,566,566,566
BEGIN DESCRIPTION:
UNT 139 IN UKCR 4.0
END DESCRIPTION:
XS GIS Cut Line= 3
      3676535.34     10573670.26      3674941.56     10573214.53
      3674485.85     10573451.50
#Sta/Elev= 30
  3673.6  323.37  3766.4  315.53  3800.2  314.06  3911.9  303.47  3950.9  297.91
  4106.0  283.56  4275.8  271.91  4460.4  268.63  4964.6  271.89  4979.7  269.87
  4987.1  265.88  4989.8  265.38  4993.1  265.88  5003.6  266.70  5010.9  270.76
  5260.9  268.28  5418.7  272.52  5479.4  276.93  5551.3  284.35  5567.8  283.78
  5573.5  285.73  5581.4  284.75  5589.9  287.14  5595.6  285.54  5604.0  288.38
  5649.0  293.15  5706.1  297.04  5761.2  298.59  5795.6  302.27  5844.9  304.36
#Mann=3,-1,0
  3673.6    0.05       0  4987.1    0.03       0  4993.1    0.05       0
Bank Sta=4987.1,4993.1
Exp/Cntr=0.3,0.1

Type RM Length L Ch R = 1,3318,855,855,855
BEGIN DESCRIPTION:
UNT 139 IN UKCR 3.0
END DESCRIPTION:
XS GIS Cut Line= 3
      3677054.04     10573690.68      3675499.61     10572760.19
      3674049.58     10573410.20
#Sta/Elev= 30
  3147.1  324.16  3471.0  309.42  3661.6  317.53  4011.7  281.16  4213.9  268.56
  4376.0  266.16  4967.6  267.83  4980.7  267.74  4990.8  264.86  4996.3  267.71
  4999.6  263.50  5002.3  263.00  5005.6  263.50  5013.5  267.72  5024.9  267.93
  5655.0  266.36  5880.1  272.08  5897.8  272.77  5903.3  274.98  5921.0  273.39
  5926.5  275.96  5944.2  275.60  5978.3  279.78  6019.2  280.67  6054.6  284.27
  6146.1  285.54  6163.8  289.94  6169.3  288.68  6175.2  291.54  6547.8  320.24
#Mann=3,-1,0
  3147.1    0.05       0  4999.6    0.03       0  5005.6    0.05       0
Bank Sta=4999.6,5005.6
Exp/Cntr=0.3,0.1

Type RM Length L Ch R = 1,2463,1122,1122,1122
BEGIN DESCRIPTION:
UNT 139 IN UKCR 2.0
END DESCRIPTION:
XS GIS Cut Line= 3
      3678043.60     10572323.49      3675283.21     10571906.82
      3673876.95     10573313.08
#Sta/Elev= 30
  2685.1  325.21  2811.6  327.83  2840.8  326.97  3053.2  308.17  3140.9  303.33
  3209.8  301.78  3278.7  297.80  3336.4  292.33  3745.8  270.76  4414.6  263.59
  4893.8  262.41  4974.7  264.26  4984.8  264.11  4992.0  260.95  4994.7  260.45
  4998.0  260.95  5005.1  263.38  5019.5  264.39  5088.4  262.42  6485.8  263.57
  6761.5  266.68  6945.4  272.08  7086.8  280.80  7108.0  280.22  7263.6  288.55
  7355.5  301.49  7405.0  306.75  7412.1  309.95  7426.2  312.21  7465.5  315.20
#Mann=3,-1,0
  2685.1    0.05       0  4992.0    0.03       0  4998.0    0.05       0
Bank Sta=4992,4998
Exp/Cntr=0.3,0.1

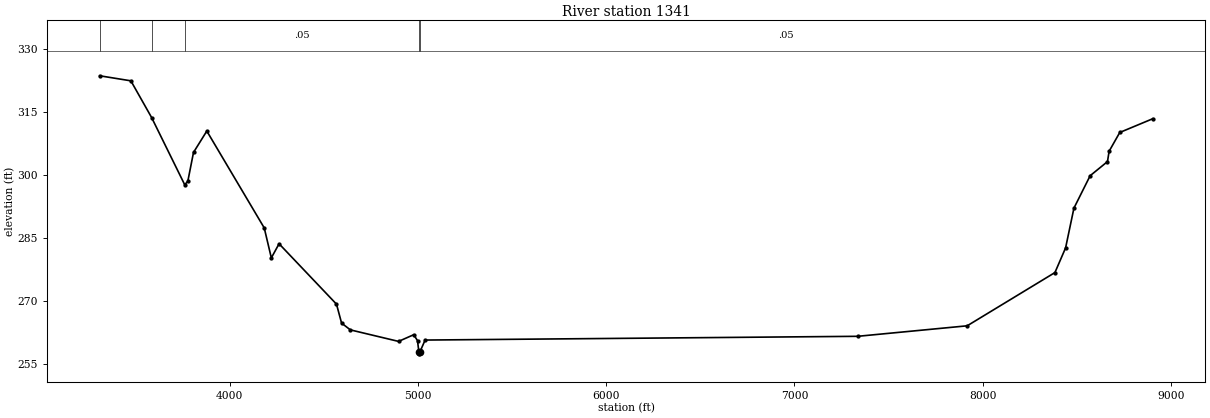
Type RM Length L Ch R = 1,1341,0,0,0
BEGIN DESCRIPTION:
UNT 139 IN UKCR 1.0
END DESCRIPTION:
XS GIS Cut Line= 3
      3677744.10     10571138.59      3675361.33     10570826.09
      3673513.51     10573428.65
#Sta/Elev= 30
  3308.7  323.52  3474.6  322.32  3584.9  313.58  3760.6  297.60  3777.2  298.42
  3807.4  305.28  3878.1  310.37  4183.2  287.32  4220.9  280.19  4262.0  283.55
  4567.1  269.18  4594.1  264.67  4640.8  263.06  4896.7  260.32  4977.4  261.91
  4997.5  260.50  5004.6  257.86  5007.4  257.36  5010.6  257.86  5037.9  260.64
  7335.9  261.53  7917.8  264.03  8384.0  276.70  8440.6  282.57  8484.9  292.03
  8571.0  299.74  8663.2  303.10  8671.8  305.56  8728.4  310.03  8903.7  313.30
#Mann=5,-1,0
  3308.7    0.05       0  3584.9    0.16       0  3760.6    0.05       0
  5004.6    0.03       0  5010.6    0.05       0
Bank Sta=5004.6,5010.6
Exp/Cntr=0.3,0.1

Chan Stop Cuts=-1