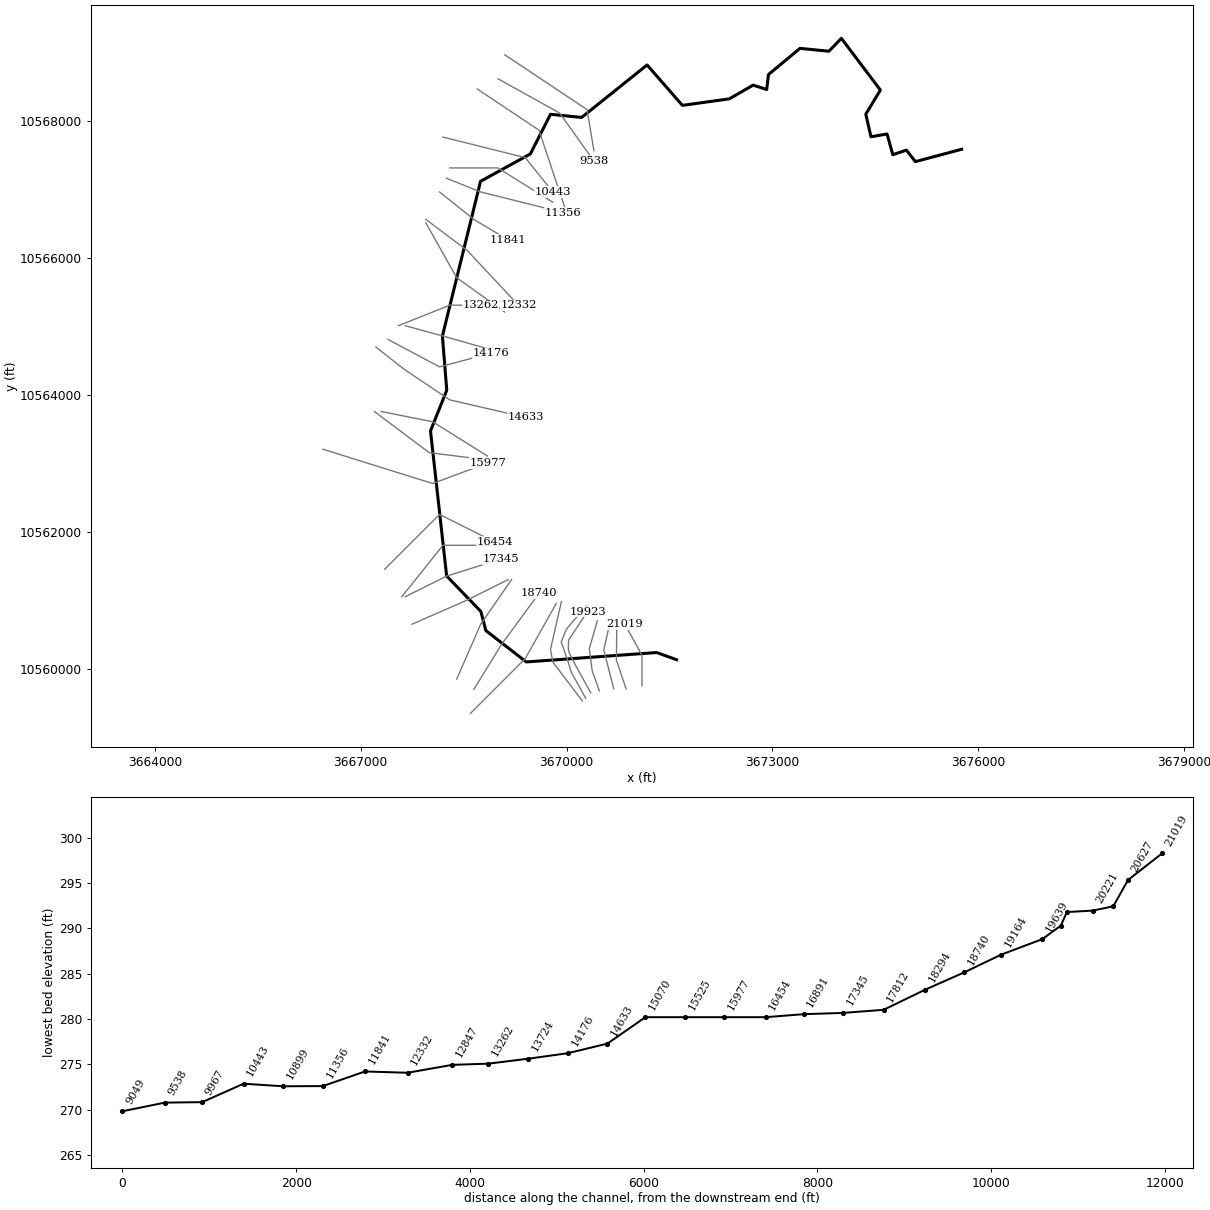
--- UNT 142 IN UKCR.prj (project) ---

Proj Title=UNT 142 IN UKCR Base Level Engineering
Current Plan=p01
Default Exp/Contr=0.3,0.1
English Units
Geom File=g01
Flow File=f01
Plan File=p01
Y Axis Title=Elevation
X Axis Title(PF)=Main Channel Distance
X Axis Title(XS)=Station
BEGIN DESCRIPTION:
UNT 142 IN UKCR
END DESCRIPTION:
DSS Export Rating Curves= 0
DSS Export Rating Curve Sorted= 0
DSS Export Volume Flow Curves= 0
DXF OffsetX= 0
DXF OffsetY= 0
DXF ScaleX= 1
DXF ScaleY= 10

--- UNT 142 IN UKCR.p01 (plan) ---

Plan Title=Multiple Run
Short Identifier=Multiple
Geom File=g01
Flow File=f01
Subcritical Flow
K Sum by GR= 0
Std Step Tol= 0.01
Critical Tol= 0.01
Num of Std Step Trials= 20
Max Error Tol= 0.3
Flow Tol Ratio= 0.001
Split Flow NTrial= 30
Split Flow Tol= 0.02
Split Flow Ratio= 0.02
Log Output Level= 0
Friction Slope Method= 1
Unsteady Friction Slope Method= 2
Unsteady Bridges Friction Slope Method= 1
Parabolic Critical Depth
Global Vel Dist=  1 , 1 , 1
Global Log Level= 0
CheckData=True
Encroach Param= -1, 0, 0, 0
BEGIN DESCRIPTION:
Multiple Run
END DESCRIPTION:

--- UNT 142 IN UKCR.f01 (steady flow) ---

Flow Title=Multiple
Program Version=4.10
Number of Profiles= 7
Profile Names=10-year,25-year,50-year,1pct_min,100-year,1pct_plu,500-year
River Rch & RM=UNT 142 IN UKCR,Reach-1         ,21019
     520     698     845     750    1015    1373    1472
River Rch & RM=UNT 142 IN UKCR,Reach-1         ,19164
     976    1355    1674    1517    2051    2774    3095
River Rch & RM=UNT 142 IN UKCR,Reach-1         ,15977
    1364    1918    2391    2182    2950    3990    4518
River Rch & RM=UNT 142 IN UKCR,Reach-1         ,15525
    1364    1918    2391    2182    2950    3990    4518
River Rch & RM=UNT 142 IN UKCR,Reach-1         ,11841
    1460    2053    2559    2334    3157    4269    4831
River Rch & RM=UNT 142 IN UKCR,Reach-1         ,7750
    1684    2373    2961    2702    3654    4942    5595
Boundary for River Rch & Prof#=UNT 142 IN UKCR,Reach-1         , 1
Up Type= 0
Dn Type= 3
Dn Slope=0.005
Boundary for River Rch & Prof#=UNT 142 IN UKCR,Reach-1         , 2
Up Type= 0
Dn Type= 3
Dn Slope=0.005
Boundary for River Rch & Prof#=UNT 142 IN UKCR,Reach-1         , 3
Up Type= 0
Dn Type= 3
Dn Slope=0.005
Boundary for River Rch & Prof#=UNT 142 IN UKCR,Reach-1         , 4
Up Type= 0
Dn Type= 3
Dn Slope=0.005
Boundary for River Rch & Prof#=UNT 142 IN UKCR,Reach-1         , 5
Up Type= 0
Dn Type= 3
Dn Slope=0.005
Boundary for River Rch & Prof#=UNT 142 IN UKCR,Reach-1         , 6
Up Type= 0
Dn Type= 3
Dn Slope=0.005
Boundary for River Rch & Prof#=UNT 142 IN UKCR,Reach-1         , 7
Up Type= 0
Dn Type= 3
Dn Slope=0.005
DSS Import GetInterval= 0
DSS Import GetPeak= 0
DSS Import FillOption= 0

--- UNT 142 IN UKCR.g01 (geometry) ---

Geom Title=Existing Conditions
Program Version=4.10

River Reach=UNT 142 IN UKCR ,Reach-1
Reach XY= 30
        3671605.       10560142.       3671314.5       10560247.
      3669413.25       10560110.       3668824.5       10560567.
      3668751.75       10560846.      3668253.25       10561362.
      3668017.75       10563477.        3668255.       10564071.
      3668191.25       10564860.        3668747.       10567115.
        3669473.       10567514.        3669767.       10568092.
       3670220.5       10568046.      3671174.75       10568811.
      3671688.75       10568222.       3672373.5       10568317.
      3672720.75       10568517.      3672917.75       10568453.
       3672944.5       10568672.      3673403.25       10569053.
       3673824.5       10569011.        3674006.       10569199.
      3674575.25       10568445.       3674362.5       10568094.
      3674437.75       10567764.        3674672.       10567805.
        3674756.       10567503.       3674954.5       10567570.
        3675085.       10567402.        3675759.       10567582.

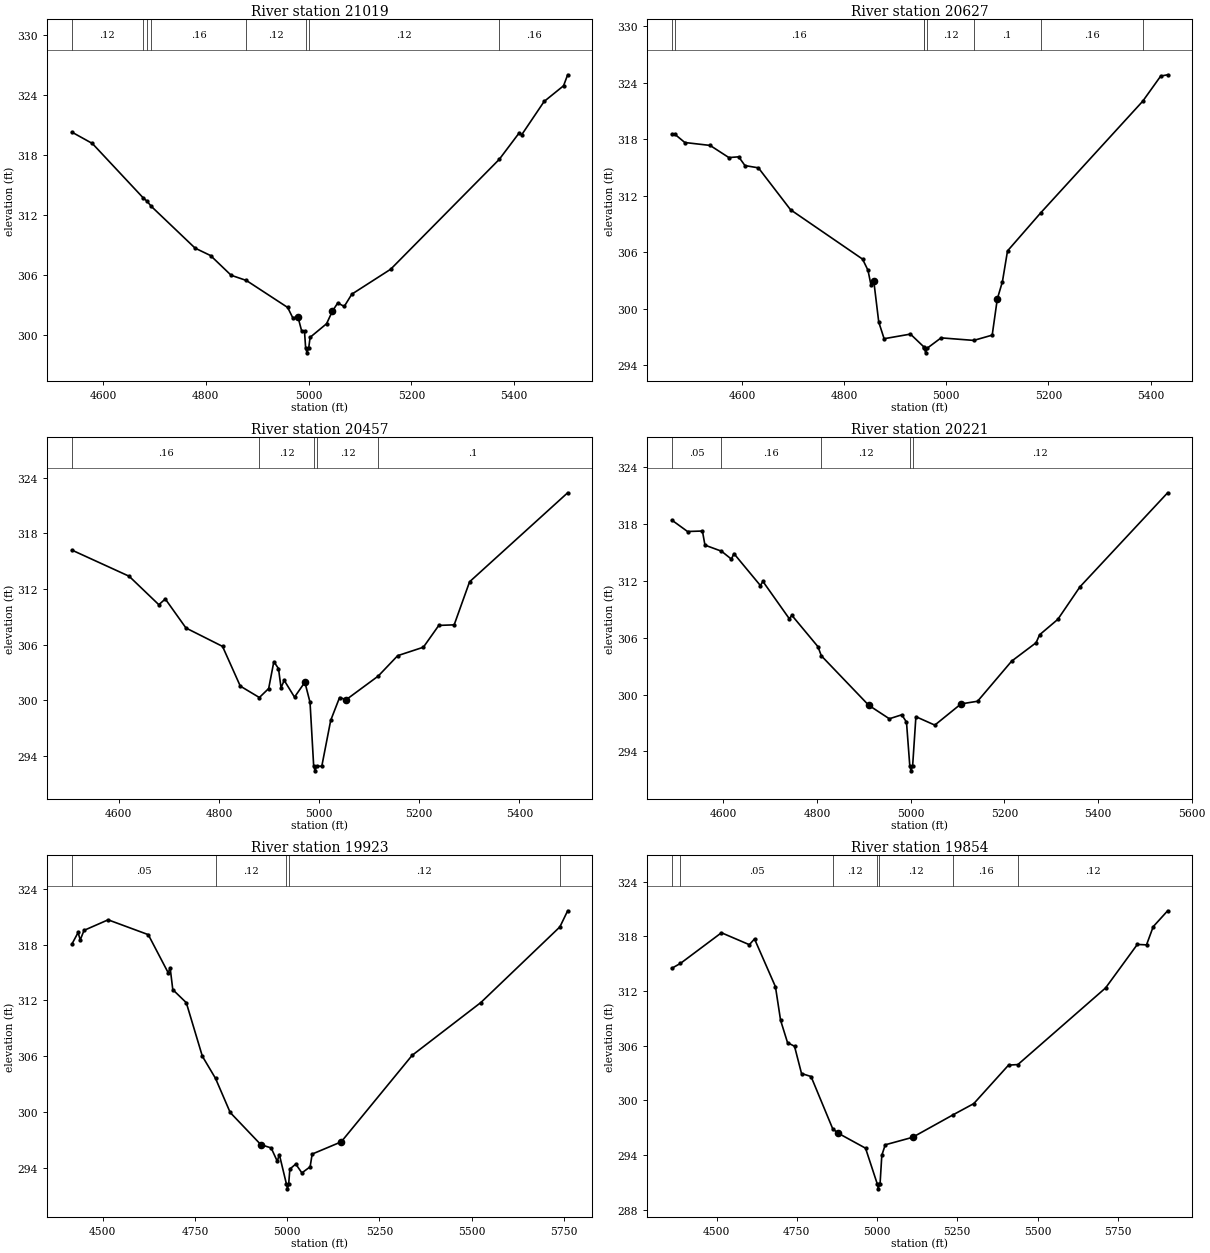
Type RM Length L Ch R = 1 ,21019   ,392,392,392
BEGIN DESCRIPTION:
UNT 142 IN UKCR 31.0
END DESCRIPTION:
XS GIS Cut Line= 3
      3671099.61     10559760.21      3671099.61     10560210.19
      3670849.59     10560660.22
#Sta/Elev= 30
  4539.1  320.33  4579.1  319.19  4677.5  313.78  4685.6  313.41  4693.6  312.91
  4779.1  308.72  4809.1  307.98  4849.1  306.01  4878.7  305.49  4959.1  302.79
  4969.1  301.75  4979.1  301.85  4986.6  300.39  4991.9  300.39  4994.1  298.75
  4996.8  298.25  5000.1  298.75  5002.8   299.8  5034.8  301.16  5046.3  302.43
  5056.6  303.24  5069.2  302.89    5084  304.12  5159.5  306.61  5370.8   317.6
  5408.9   320.2  5414.6  320.07  5458.1  323.39  5495.9  324.96  5503.9  326.06
#Mann= 8 ,-1 , 0
  4539.1     .12       0  4677.5     .16       0  4685.6     .12       0
  4693.6     .16       0  4878.7     .12       0  4994.1     .07       0
  5000.1     .12       0  5370.8     .16       0
Bank Sta=4979.1,5046.3
XS Rating Curve= 0 ,0
Exp/Cntr=0.3,0.1

Type RM Length L Ch R = 1 ,20627   ,170,170,170
BEGIN DESCRIPTION:
UNT 142 IN UKCR 30.0
END DESCRIPTION:
XS GIS Cut Line= 3
      3670869.17     10559715.93      3670726.83      10560139.5
      3670733.77      10560663.8
#Sta/Elev= 30
  4462.2  318.55  4468.4  318.52  4487.8  317.65  4537.3  317.34  4574.1  316.05
  4593.3  316.13  4605.6   315.2  4631.9  314.96  4694.9  310.51  4835.9  305.27
  4846.5  304.09  4852.5   302.5  4857.8  302.98  4867.6  298.59  4878.1  296.82
  4929.7  297.31  4955.4  295.98  4956.7  295.82  4959.5  295.32  4962.7  295.82
  4989.7  296.91  5053.6  296.64  5089.8   297.2  5099.8  301.04  5109.8  302.87
  5119.8  306.14  5185.1   310.2  5384.7  322.04  5419.8   324.7  5433.4  324.84
#Mann= 8 ,-1 , 0
  4462.2     .12       0  4468.4     .16       0  4955.4     .12       0
  4956.7     .07       0  4962.7     .12       0  5053.6      .1       0
  5185.1     .16       0  5384.7      .1       0
Bank Sta=4857.8,5099.8
XS Rating Curve= 0 ,0
Exp/Cntr=0.3,0.1

Type RM Length L Ch R = 1 ,20457   ,236,236,236
BEGIN DESCRIPTION:
Mapping XS 38cf406b
END DESCRIPTION:
XS GIS Cut Line= 3
      3670688.64     10559719.33       3670542.8     10560285.33
      3670633.08     10560681.18
#Sta/Elev= 30
    4506  316.21  4620.5  313.39  4679.9  310.32  4692.8  310.94  4734.1  307.81
  4807.1  305.83  4842.6  301.55  4880.7  300.32  4899.3  301.29  4909.6  304.18
  4918.9  303.44    4924  301.37  4930.3  302.17  4950.9  300.36  4971.6  301.97
  4981.9   299.8  4989.2  292.92    4992  292.42  4995.2  292.92  5005.4  292.92
  5023.2  297.86  5040.9  300.32  5054.2  300.09  5118.1  302.63    5157  304.83
  5208.3  305.74  5239.1  308.09  5269.8  308.15  5300.6  312.79  5496.5  322.38
#Mann= 5 ,-1 , 0
    4506     .16       0  4880.7     .12       0  4989.2     .07       0
  4995.2     .12       0  5118.1      .1       0
Bank Sta=4971.6,5054.2
XS Rating Curve= 0 ,0
Exp/Cntr=0.3,0.1

Type RM Length L Ch R = 1 ,20221   ,298,298,298
BEGIN DESCRIPTION:
UNT 142 IN UKCR 29.0
END DESCRIPTION:
XS GIS Cut Line= 4
      3670478.21     10559688.43      3670374.06     10559983.52
       3670332.4     10560302.97       3670449.6     10560710.15
#Sta/Elev= 30
  4489.9  318.44  4523.6  317.23  4555.4  317.28  4560.8  315.79  4596.1  315.15
  4617.3  314.31  4622.6   314.9  4679.2  311.52  4684.5  311.96    4741  308.01
  4746.3  308.38    4802  305.07  4809.3   304.1  4910.4  298.88  4954.5  297.45
    4981  297.87  4991.1   297.1  4998.2  292.45  5000.9  291.95  5004.2  292.45
  5011.2  297.67  5051.6  296.78  5107.5  299.02  5142.9   299.3  5215.7  303.54
  5267.8  305.48  5275.3  306.32  5314.2  307.95  5361.4  311.38  5548.7  321.32
#Mann= 5 ,-1 , 0
  4489.9     .05       0  4596.1     .16       0  4809.3     .12       0
  4998.2     .07       0  5004.2     .12       0
Bank Sta=4910.4,5107.5
XS Rating Curve= 0 ,0
Exp/Cntr=0.3,0.1

Type RM Length L Ch R = 1 ,19923   ,69,69,69
BEGIN DESCRIPTION:
Mapping XS 32272e33
END DESCRIPTION:
XS GIS Cut Line= 6
      3670353.23     10559660.61      3670137.95      10560049.5
      3670037.26     10560247.41      3670026.84     10560302.97
      3670030.31     10560427.97      3670304.63     10560841.18
#Sta/Elev= 30
  4416.3  318.02  4433.5  319.29  4439.2  318.49  4449.6  319.52  4514.8  320.65
  4623.6  319.06  4677.4  314.99  4683.1  315.45  4690.1  313.16  4726.7  311.76
  4770.2  306.02  4805.9  303.64  4845.7  299.98  4928.8  296.53  4956.7  296.18
  4973.3  294.75  4978.9  295.47  4998.2  292.29  5000.9  291.79  5004.2  292.29
  5007.4  293.91  5023.4  294.45    5040   293.5  5062.3  294.15  5067.9  295.52
  5146.6  296.83  5338.8  306.11  5525.2  311.78  5739.3  319.89  5760.4  321.62
#Mann= 5 ,-1 , 0
  4416.3     .05       0  4805.9     .12       0  4998.2     .07       0
  5004.2     .12       0  5739.3     .16       0
Bank Sta=4928.8,5146.6
XS Rating Curve= 0 ,0
Exp/Cntr=0.3,0.1

Type RM Length L Ch R = 1 ,19854   ,215,215,215
BEGIN DESCRIPTION:
Mapping XS 4efd75b0
END DESCRIPTION:
XS GIS Cut Line= 6
      3670280.29     10559580.79      3670071.98     10559955.75
       3670019.9     10560122.41      3669922.67     10560403.66
      3669999.06     10560587.69       3670286.1      10560926.6
#Sta/Elev= 30
  4360.6  314.49  4387.8  315.03  4515.4  318.39  4602.3  317.08  4618.4  317.71
  4683.6  312.47  4699.6  308.79  4721.3  306.33    4743  305.94  4764.8  302.95
  4794.5  302.62  4861.7  296.91    4877  296.44  4964.2  294.76  5001.1   290.8
  5003.9   290.3  5007.1   290.8  5009.4  290.81  5014.9  293.98  5025.6  295.13
  5110.6  295.95  5236.9  298.42  5301.4  299.65  5409.6  303.87  5438.7  303.93
    5712  312.34  5810.8  317.11  5839.4  317.06  5860.3  319.06  5905.2   320.8
#Mann= 7 ,-1 , 0
  4360.6     .16       0  4387.8     .05       0  4861.7     .12       0
  5001.1     .07       0  5007.1     .12       0  5236.9     .16       0
  5438.7     .12       0
Bank Sta=4877,5110.6
XS Rating Curve= 0 ,0
Exp/Cntr=0.3,0.1

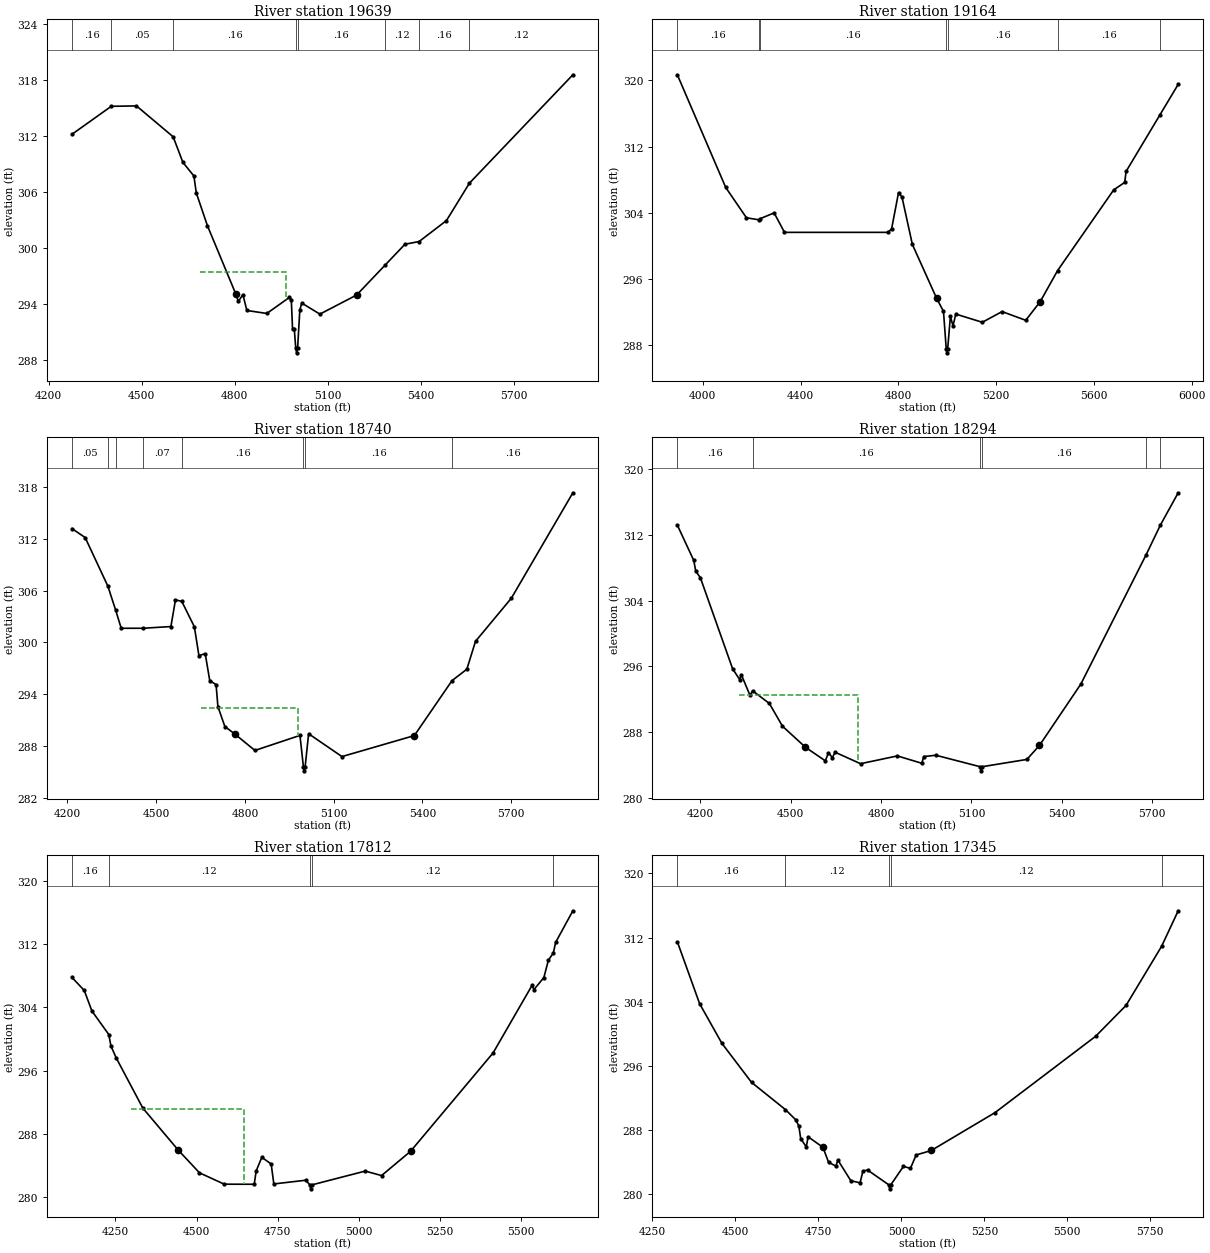
Type RM Length L Ch R = 1 ,19639   ,475,475,475
BEGIN DESCRIPTION:
UNT 142 IN UKCR 28.0
END DESCRIPTION:
XS GIS Cut Line= 4
       3670231.1     10559540.53      3669799.61     10560110.19
      3669766.42     10560292.55      3669926.14     10560990.42
#Sta/Elev= 30
  4275.4  312.17    4402  315.16  4483.4   315.2  4601.7   311.9  4633.2  309.16
  4668.6  307.71  4676.4  305.89  4712.3  302.39  4803.8  295.09  4812.1  294.29
  4826.7  295.03  4839.5  293.33  4903.7  293.01  4976.5  294.72  4982.8   294.5
  4986.9  291.32  4992.6  291.32  4997.2   289.3  4999.9   288.8  5003.2   289.3
  5010.4  293.41  5016.7  294.12  5075.1  292.94  5193.5  294.98  5285.8  298.19
  5349.5  300.41  5395.1   300.7  5483.4  302.94  5557.5  306.94  5891.3  318.53
#Mann= 8 ,-1 , 0
  4275.4     .16       0    4402     .05       0  4601.7     .16       0
  4997.2     .07       0  5003.2     .16       0  5285.8     .12       0
  5395.1     .16       0  5557.5     .12       0
#XS Ineff= 1 ,-1
 4687.84 4967.05   297.4
Permanent Ineff=
       F
Bank Sta=4803.8,5193.5
XS Rating Curve= 0 ,0
Exp/Cntr=0.3,0.1

Type RM Length L Ch R = 1 ,19164   ,424,424,424
BEGIN DESCRIPTION:
UNT 142 IN UKCR 27.0
END DESCRIPTION:
XS GIS Cut Line= 3
      3668599.63     10559360.21      3669399.61     10560160.19
       3669849.6     10560960.17
#Sta/Elev= 30
  3895.8  320.67  4093.8  307.06  4178.6   303.4  4228.7  303.16  4235.2   303.3
  4291.8  303.99  4334.2  301.64  4758.4  301.64  4772.6  302.09  4800.9  306.45
    4815  305.89  4857.4  300.18  4956.4  293.69  4984.7   292.1  4995.9  287.59
  4998.6  287.09  5001.9  287.59    5013   291.5  5023.6  290.35  5035.1  291.77
  5143.5  290.78  5224.4  292.07  5321.3  291.02  5380.6  293.28  5451.7  297.03
  5681.1  306.77  5726.1  307.67  5731.8     309  5869.7   315.8    5945  319.51
#Mann= 7 ,-1 , 0
  3895.8     .16       0  4228.7     .12       0  4235.2     .16       0
  4995.9     .07       0  5001.9     .16       0  5451.7     .16       0
  5869.7     .12       0
Bank Sta=4956.4,5380.6
XS Rating Curve= 0 ,0
Exp/Cntr=0.3,0.1

Type RM Length L Ch R = 1 ,18740   ,446,446,446
BEGIN DESCRIPTION:
UNT 142 IN UKCR 26.0
END DESCRIPTION:
XS GIS Cut Line= 3
      3668649.58     10559710.15      3669049.61     10560360.19
       3669599.6     10561110.17
#Sta/Elev= 30
  4215.3  313.17  4259.7  312.14  4336.4  306.52  4362.7  303.75  4381.6  301.64
  4454.5  301.64  4549.6  301.84    4565  304.92  4586.3  304.76  4628.9  301.81
  4644.3  298.48  4665.6   298.7    4681  295.57  4702.3  295.12  4708.5  292.58
    4732  290.27  4767.2  289.36  4833.6   287.5  4985.9  289.24  4997.5  285.64
  5000.3  285.14  5003.5  285.64  5015.2  289.43  5127.9  286.79  5372.6  289.22
    5500  295.58  5550.1   296.9  5579.4  300.13  5700.6  305.12  5908.6  317.32
#Mann= 8 ,-1 , 0
  4215.3     .05       0  4336.4     .07       0  4362.7      .1       0
  4454.5     .07       0  4586.3     .16       0  4997.5     .07       0
  5003.5     .16       0    5500     .16       0
#XS Ineff= 1 ,-1
 4651.02 4980.34  292.45
Permanent Ineff=
       F
Bank Sta=4767.2,5372.6
XS Rating Curve= 0 ,0
Exp/Cntr=0.3,0.1

Type RM Length L Ch R = 1 ,18294   ,482,482,482
BEGIN DESCRIPTION:
UNT 142 IN UKCR 25.0
END DESCRIPTION:
XS GIS Cut Line= 3
       3668399.6     10559860.16      3668749.61     10560660.19
       3669199.6     10561310.18
#Sta/Elev= 30
  4123.1   313.2  4177.7  308.89  4184.3  307.58  4199.5   306.8  4306.7  295.69
  4330.1  294.38  4335.6  294.98  4364.4  292.45  4373.1  293.01  4428.8  291.46
  4472.4  288.69  4548.8  286.12  4614.7  284.47  4625.2  285.45  4638.1  284.86
  4647.1  285.52  4731.7  284.12  4854.1  285.07  4935.1  284.17  4941.8  284.99
  4981.9  285.15  5129.2  283.75  5131.9  283.25  5135.2  283.75  5284.2  284.64
  5326.1  286.35  5463.3  293.81  5680.4  309.59  5727.7   313.2  5786.9  317.14
#Mann= 6 ,-1 , 0
  4123.1     .16       0  4373.1     .16       0  5129.2     .07       0
  5135.2     .16       0  5680.4     .16       0  5727.7     .12       0
#XS Ineff= 1 ,-1
  4328.3 4722.05  292.52
Permanent Ineff=
       F
Bank Sta=4548.8,5326.1
XS Rating Curve= 0 ,0
Exp/Cntr=0.3,0.1

Type RM Length L Ch R = 1 ,17812   ,467,467,467
BEGIN DESCRIPTION:
UNT 142 IN UKCR 24.0
END DESCRIPTION:
XS GIS Cut Line= 3
      3667749.64      10560660.2      3668549.61     10561010.19
      3669149.61     10561310.19
#Sta/Elev= 30
    4116   307.8  4153.8  306.15  4177.2  303.56  4229.4  300.57    4236  299.11
  4252.8  297.56  4334.3  291.25  4443.4  285.93  4508.9  283.05  4585.3  281.61
  4677.7   281.6  4683.6  283.28  4701.1  285.01  4729.9  284.17  4738.1  281.64
  4836.4  282.11  4849.3  281.52  4852.1  281.02  4855.3  281.52  5019.9  283.27
  5070.2   282.7  5159.7  285.78    5414  298.24  5534.2   306.8  5539.8  306.26
  5570.6  307.79  5584.5  309.99  5599.8  310.91  5606.9  312.25    5660  316.25
#Mann= 5 ,-1 , 0
    4116     .16       0  4229.4     .12       0  4849.3     .07       0
  4855.3     .12       0  5599.8     .16       0
#XS Ineff= 1 ,-1
 4296.59 4645.34  291.11
Permanent Ineff=
       F
Bank Sta=4443.4,5159.7
XS Rating Curve= 0 ,0
Exp/Cntr=0.3,0.1

Type RM Length L Ch R = 1 ,17345   ,454,454,454
BEGIN DESCRIPTION:
UNT 142 IN UKCR 23.0
END DESCRIPTION:
XS GIS Cut Line= 3
      3667649.61     10561060.19      3668249.61     10561360.19
      3669049.63      10561610.2
#Sta/Elev= 30
    4325  311.48  4392.1  303.76  4459.2  298.82  4548.6  293.95  4650.6  290.56
  4682.8  289.24  4691.2  288.48  4696.7  286.93  4713.5  285.92  4719.1  287.17
  4763.8  285.85  4780.6  283.99    4803  283.51  4808.5  284.28  4847.7  281.69
  4875.6  281.43    4884  282.88    4898  283.03  4962.1  281.18  4964.8  280.68
  4968.1  281.18  5006.3  283.48  5027.3  283.23  5044.5   284.9  5090.1  285.46
  5282.4  290.19  5585.1  299.69  5676.8  303.54    5784  310.91    5834  315.34
#Mann= 5 ,-1 , 0
    4325     .16       0  4650.6     .12       0  4962.1     .07       0
  4968.1     .12       0    5784     .16       0
Bank Sta=4763.8,5090.1
XS Rating Curve= 0 ,0
Exp/Cntr=0.3,0.1

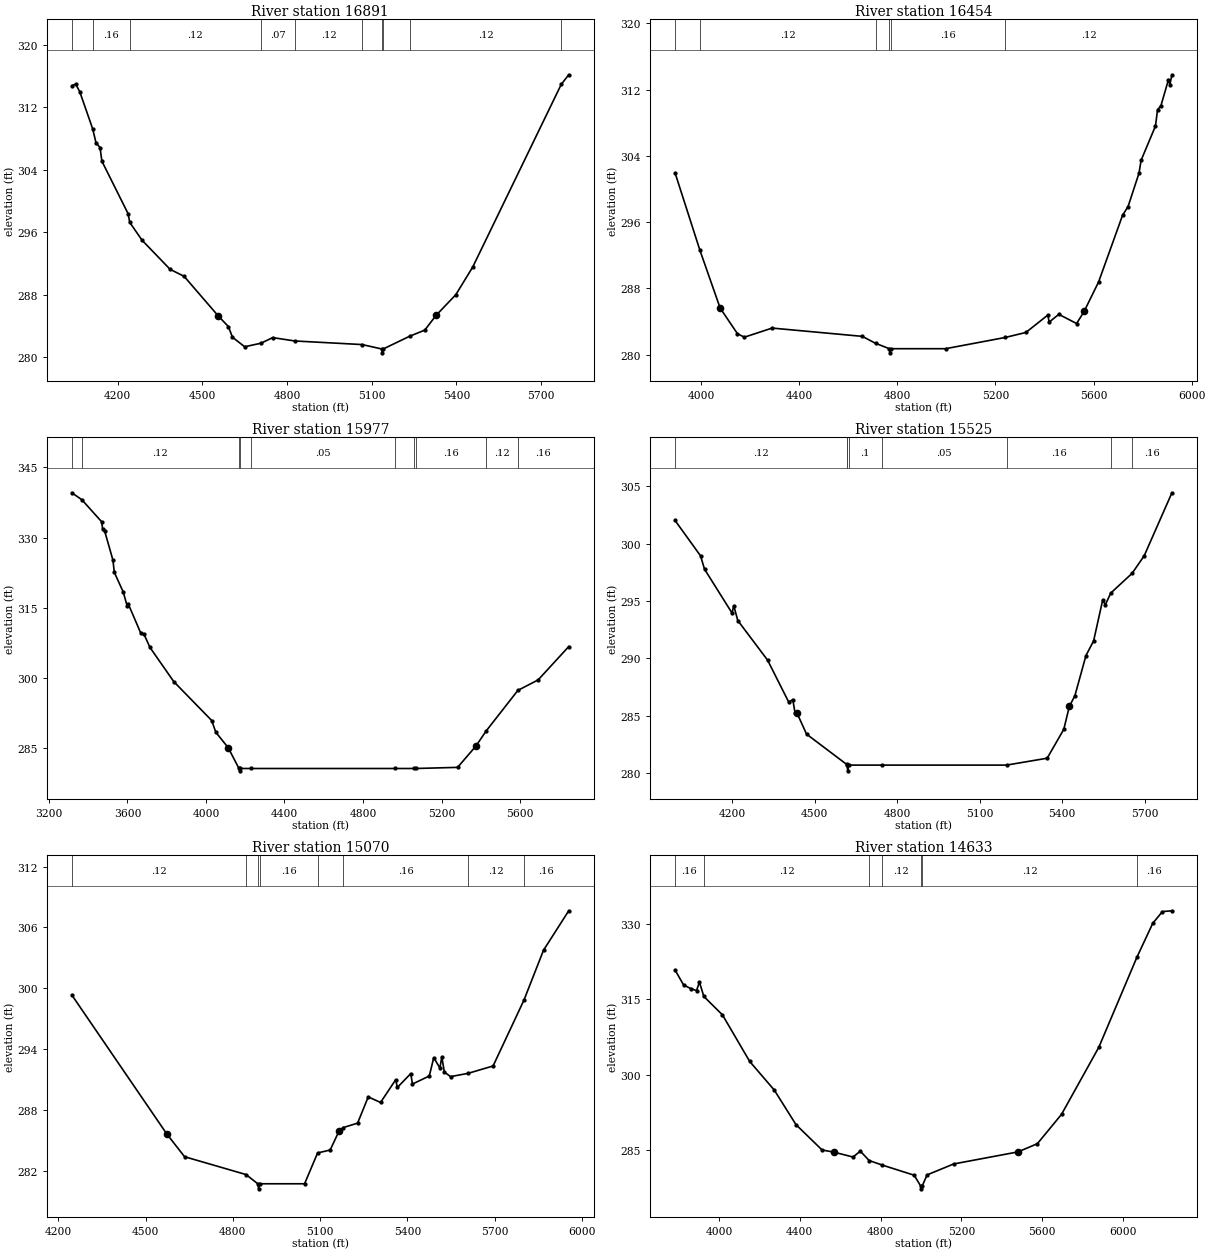
Type RM Length L Ch R = 1 ,16891   ,437,437,437
BEGIN DESCRIPTION:
UNT 142 IN UKCR 22.0
END DESCRIPTION:
XS GIS Cut Line= 3
      3667599.62     10561060.21      3668199.61     10561810.19
      3668999.56     10561810.19
#Sta/Elev= 30
  4037.6  314.76  4051.2  314.97  4065.6     314  4111.6  309.22  4123.2  307.46
  4137.6  306.83    4144   305.1  4236.9  298.37  4242.8  297.25  4286.5  294.96
  4385.7  291.24  4435.4  290.34    4557  285.24  4592.2  283.91  4606.7  282.54
  4649.9  281.32  4707.4  281.77  4749.1  282.49  4827.7  282.06  5065.9   281.6
    5135  281.04  5137.8  280.54    5141  281.04  5235.3  282.68    5288  283.45
    5328  285.34    5398  287.99    5458  291.54  5771.6  314.94    5798  316.16
#Mann= 10 ,-1 , 0
  4037.6     .12       0  4111.6     .16       0  4242.8     .12       0
  4707.4     .07       0  4827.7     .12       0  5065.9     .16       0
    5135     .07       0    5141     .16       0  5235.3     .12       0
  5771.6     .16       0
Bank Sta=4557,5328
XS Rating Curve= 0 ,0
Exp/Cntr=0.3,0.1

Type RM Length L Ch R = 1 ,16454   ,477,477,477
BEGIN DESCRIPTION:
UNT 142 IN UKCR 21.0
END DESCRIPTION:
XS GIS Cut Line= 3
      3667349.64     10561460.22      3668149.61     10562260.19
      3668949.65     10561860.17
#Sta/Elev= 30
  3893.8  301.96  3995.5  292.58  4077.6  285.63  4148.3  282.52  4176.6   282.1
  4289.7   283.2  4657.4   282.2  4711.4  281.36  4767.6  280.71  4770.3  280.21
  4773.6  280.71  4996.8  280.71  5240.6  282.07  5324.2  282.67  5413.6  284.77
  5419.2  283.92  5458.4  284.86    5531  283.75  5561.8  285.22  5620.5  288.76
  5718.3  296.82  5740.7  297.87  5785.4  301.91  5793.8  303.45  5852.5   307.6
  5860.9  309.56  5874.8  310.06  5905.6  313.21  5911.2   312.6  5919.6  313.79
#Mann= 6 ,-1 , 0
  3893.8     .16       0  3995.5     .12       0  4711.4     .16       0
  4767.6     .07       0  4773.6     .16       0  5240.6     .12       0
Bank Sta=4077.6,5561.8
XS Rating Curve= 0 ,0
Exp/Cntr=0.3,0.1

Type RM Length L Ch R = 1 ,15977   ,452,452,452
BEGIN DESCRIPTION:
UNT 142 IN UKCR 20.0
END DESCRIPTION:
XS GIS Cut Line= 3
      3666449.64     10563210.18      3668049.61     10562710.19
      3668849.64      10563010.2
#Sta/Elev= 30
  3316.9  339.56  3367.9  338.08  3468.3   333.4    3474  331.85  3484.5  331.33
  3526.4  325.17  3533.2  322.58  3578.8  318.38  3598.2  315.47  3603.4  315.92
  3668.4  309.57  3683.6  309.44    3715  306.54    3836  299.26  4029.3  290.95
  4050.2  288.45  4113.1  285.16  4168.3  280.71    4171  280.21  4174.3  280.71
  4229.4  280.71  4963.6  280.71  5057.2  280.71    5068  280.71  5281.5  280.95
    5375   285.5  5426.7   288.7  5588.5  297.38  5691.8  299.62  5847.6  306.73
#Mann= 10 ,-1 , 0
  3316.9     .16       0  3367.9     .12       0  4168.3     .07       0
  4174.3     .12       0  4229.4     .05       0  4963.6     .16       0
  5057.2     .05       0    5068     .16       0  5426.7     .12       0
  5588.5     .16       0
Bank Sta=4113.1,5375
XS Rating Curve= 0 ,0
Exp/Cntr=0.3,0.1

Type RM Length L Ch R = 1 ,15525   ,455,455,455
BEGIN DESCRIPTION:
UNT 142 IN UKCR 19.0
END DESCRIPTION:
XS GIS Cut Line= 3
      3667199.63     10563760.17      3667999.61     10563160.19
      3668799.61     10563060.19
#Sta/Elev= 30
  3992.8  302.03  4085.5  298.95  4100.1  297.78  4200.1  293.96  4206.3   294.6
  4220.9  293.31  4329.2  289.86  4406.3  286.19  4420.9  286.42  4429.2  285.24
  4435.5  285.28  4470.9  283.41  4616.8  280.77  4617.9  280.71  4620.7  280.21
  4623.9  280.71  4744.1  280.71  5197.8  280.71  5345.5  281.31    5406  283.83
  5426.1  285.82  5446.3  286.76  5486.6  290.26  5514.3  291.53  5547.1  295.07
  5557.1  294.69  5576.7   295.7  5654.2  297.42  5698.2  298.95    5799  304.44
#Mann= 8 ,-1 , 0
  3992.8     .12       0  4616.8      .1       0  4617.9    .033       0
  4623.9      .1       0  4744.1     .05       0  5197.8     .16       0
  5576.7     .12       0  5654.2     .16       0
Bank Sta=4435.5,5426.1
XS Rating Curve= 0 ,0
Exp/Cntr=0.3,0.1

Type RM Length L Ch R = 1 ,15070   ,437,437,437
BEGIN DESCRIPTION:
UNT 142 IN UKCR 18.0
END DESCRIPTION:
XS GIS Cut Line= 3
       3667299.6     10563760.19      3668049.61     10563610.19
      3668849.64     10563110.17
#Sta/Elev= 30
  4246.5  299.33  4572.8  285.63    4634  283.38  4845.2  281.62    4886  280.71
  4888.7  280.21    4892  280.71  5046.7  280.71  5091.4  283.75  5134.6  284.04
  5164.7  285.88  5180.3  286.26  5228.9  286.69  5265.5  289.28  5307.9  288.73
  5359.8  290.97  5365.7  290.21  5411.7  291.58  5417.6  290.55  5475.4  291.34
  5490.7  293.15    5512  292.13  5518.4  293.22  5527.3  291.73  5548.5  291.28
  5608.4   291.6  5694.7  292.33  5800.9  298.83  5868.1  303.75  5954.8  307.64
#Mann= 8 ,-1 , 0
  4246.5     .12       0  4845.2     .16       0    4886     .07       0
    4892     .16       0  5091.4     .05       0  5180.3     .16       0
  5608.4     .12       0  5800.9     .16       0
Bank Sta=4572.8,5164.7
XS Rating Curve= 0 ,0
Exp/Cntr=0.3,0.1

Type RM Length L Ch R = 1 ,14633   ,457,457,457
BEGIN DESCRIPTION:
UNT 142 IN UKCR 17.0
END DESCRIPTION:
XS GIS Cut Line= 4
      3667220.52     10564700.64      3667637.19     10564372.51
      3668298.65      10563929.8      3669401.57     10563674.88
#Sta/Elev= 30
    3783  320.85  3825.3  317.87  3860.5  317.15  3889.4  316.74  3903.9  318.43
  3925.4  315.58  4017.7  311.91  4152.4  302.65  4274.3  296.94  4381.5  290.07
  4510.6  285.03    4569   284.6  4663.7  283.63  4699.7   284.8  4743.5  282.93
  4805.9  282.06  4966.1  280.01  4999.2   277.8  5001.9   277.3  5005.2   277.8
    5030  280.07  5161.6  282.25  5479.8  284.65  5575.6  286.28  5695.3  292.13
  5879.8  305.48  6067.8  323.35  6146.5  330.13  6194.3  332.46  6241.3  332.62
#Mann= 7 ,-1 , 0
    3783     .16       0  3925.4     .12       0  4743.5     .16       0
  4805.9     .12       0  4999.2     .07       0  5005.2     .12       0
  6067.8     .16       0
Bank Sta=4569,5479.8
XS Rating Curve= 0 ,0
Exp/Cntr=0.3,0.1

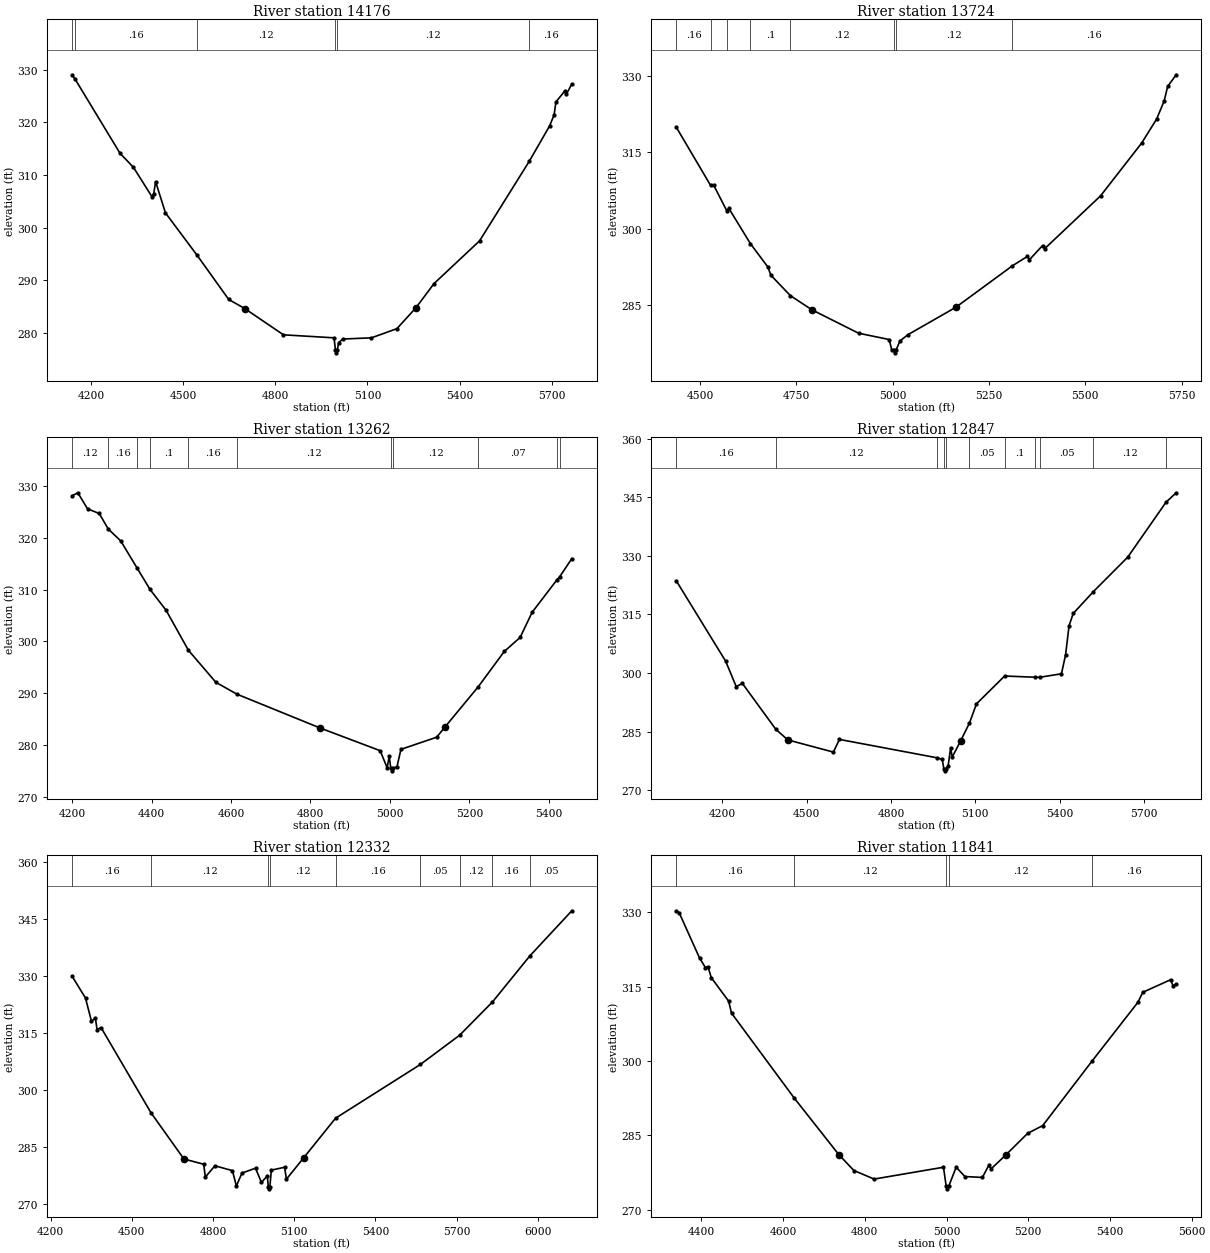
Type RM Length L Ch R = 1 ,14176   ,452,452,452
BEGIN DESCRIPTION:
UNT 142 IN UKCR 16.0
END DESCRIPTION:
XS GIS Cut Line= 3
      3667399.62     10564810.18      3668149.61     10564410.19
      3668899.62     10564610.19
#Sta/Elev= 30
  4138.6  329.02  4147.7  328.29  4294.8  314.13  4338.7  311.44  4398.9  305.87
  4404.6  306.46  4410.6  308.74  4442.8   302.8  4545.9  294.74  4648.6  286.37
  4700.6  284.65  4826.7  279.66  4991.2  279.09  4995.9  276.74  4998.7  276.24
  5001.9  276.74    5006  278.18  5019.6  278.86  5112.8  279.09  5195.6  280.82
  5257.7   284.8  5316.5  289.39  5464.7   297.5    5626  312.57  5692.3  319.29
  5707.2  321.41    5713  323.86  5742.2  325.96  5747.3  325.33  5764.8  327.29
#Mann= 6 ,-1 , 0
  4138.6     .12       0  4147.7     .16       0  4545.9     .12       0
  4995.9     .07       0  5001.9     .12       0    5626     .16       0
Bank Sta=4700.6,5257.7
XS Rating Curve= 0 ,0
Exp/Cntr=0.3,0.1

Type RM Length L Ch R = 1 ,13724   ,462,462,462
BEGIN DESCRIPTION:
UNT 142 IN UKCR 15.0
END DESCRIPTION:
XS GIS Cut Line= 3
      3667649.63     10565010.18      3668199.61     10564860.19
      3668899.63     10564660.18
#Sta/Elev= 30
    4438  319.88    4527  308.48  4534.7  308.58  4568.7  303.55  4574.5  303.96
  4630.6  297.04  4676.4  292.41  4683.3  290.88  4734.2  286.86  4790.4  284.07
  4911.3  279.49  4990.8  278.25  4997.7  276.16  5002.5  276.14  5005.2  275.64
  5008.5  276.14  5018.5  277.94  5039.3  279.19  5164.1  284.58  5310.4  292.69
    5350  294.56  5355.2  293.91    5389  296.67  5394.2  296.03  5539.8  306.43
  5646.4  316.77  5685.4  321.49  5704.9  325.03    5714  327.88  5736.1  330.17
#Mann= 8 ,-1 , 0
    4438     .16       0    4527     .12       0  4568.7     .16       0
  4630.6      .1       0  4734.2     .12       0  5002.5     .07       0
  5008.5     .12       0  5310.4     .16       0
Bank Sta=4790.4,5164.1
XS Rating Curve= 0 ,0
Exp/Cntr=0.3,0.1

Type RM Length L Ch R = 1 ,13262   ,415,415,415
BEGIN DESCRIPTION:
UNT 142 IN UKCR 14.0
END DESCRIPTION:
XS GIS Cut Line= 3
      3667549.58     10565010.18      3668299.61     10565310.19
      3668749.61     10565310.19
#Sta/Elev= 30
  4199.8  328.05  4214.6  328.64  4238.9  325.55  4268.5  324.65  4291.1  321.66
  4322.3  319.39  4363.6  314.15    4396  310.05  4436.8  305.99  4492.7  298.32
    4562  292.13    4615  289.85  4824.5  283.33  4975.3  278.97  4992.8  275.69
  4998.2  277.88  5001.9  275.59  5004.7  275.09  5007.9  275.59  5017.6  275.88
  5027.6  279.23  5117.6  281.57  5137.6  283.46  5222.1  291.28  5287.6  298.08
  5327.6  300.79  5357.6  305.61  5419.9  311.85  5426.9  312.45  5457.6  315.96
#Mann= 11 ,-1 , 0
  4199.8     .12       0  4291.1     .16       0  4363.6     .12       0
    4396      .1       0  4492.7     .16       0    4615     .12       0
  5001.9     .07       0  5007.9     .12       0  5222.1     .07       0
  5419.9     .05       0  5426.9     .12       0
Bank Sta=4824.5,5137.6
XS Rating Curve= 0 ,0
Exp/Cntr=0.3,0.1

Type RM Length L Ch R = 1 ,12847   ,515,515,515
BEGIN DESCRIPTION:
UNT 142 IN UKCR 13.0
END DESCRIPTION:
XS GIS Cut Line= 3
      3667949.62     10566510.16      3668399.61     10565710.19
      3669099.62     10565210.18
#Sta/Elev= 30
  4036.2  323.59  4211.8  303.02  4249.4   296.5  4271.1  297.35  4390.2  285.59
    4433  282.87  4594.9  279.76  4616.5     283  4963.1  278.31  4982.3  277.89
  4987.9  275.46  4990.7  274.96  4993.9  275.46  5003.2  276.23  5011.8  280.71
    5018  278.52  5047.4   282.6  5079.1   287.2    5104  292.11  5204.1  299.23
  5312.5  298.92  5329.1  298.91  5406.3   299.8    5421  304.69  5433.3  312.11
  5448.1  315.24  5520.1  320.85  5642.2  329.67  5778.2  343.71  5814.3  346.13
#Mann= 11 ,-1 , 0
  4036.2     .16       0  4390.2     .12       0  4963.1     .05       0
  4987.9     .07       0  4993.9     .05       0  5079.1     .05       0
  5204.1      .1       0  5312.5     .15       0  5329.1     .05       0
  5520.1     .12       0  5778.2     .16       0
Bank Sta=4433,5047.4
XS Rating Curve= 0 ,0
Exp/Cntr=0.3,0.1

Type RM Length L Ch R = 1 ,12332   ,491,491,491
BEGIN DESCRIPTION:
UNT 142 IN UKCR 12.0
END DESCRIPTION:
XS GIS Cut Line= 3
       3667949.6      10566560.2      3668549.61     10566110.19
      3669299.61     10565310.19
#Sta/Elev= 30
  4278.8  330.06  4328.8  324.24  4350.7  318.19  4365.3  318.97  4371.5  315.96
  4386.1  316.51  4570.7  294.09  4692.4  281.94  4765.3  280.56  4771.5  277.19
  4806.9  280.15  4871.5  278.88  4886.1  274.83  4906.9  278.25  4956.9  279.51
  4978.8  275.77  5000.7  277.52  5003.9  274.59  5006.7  274.09  5009.9  274.59
  5015.3  279.01  5064.2  279.76  5071.1  276.63    5135  282.27  5252.5  292.66
  5565.9  306.79  5710.9  314.48  5832.3  323.23  5970.4  335.34  6125.4   347.2
#Mann= 9 ,-1 , 0
  4278.8     .16       0  4570.7     .12       0  5003.9     .07       0
  5009.9     .12       0  5252.5     .16       0  5565.9     .05       0
  5710.9     .12       0  5832.3     .16       0  5970.4     .05       0
Bank Sta=4692.4,5135
XS Rating Curve= 0 ,0
Exp/Cntr=0.3,0.1

Type RM Length L Ch R = 1 ,11841   ,485,485,485
BEGIN DESCRIPTION:
UNT 142 IN UKCR 11.0
END DESCRIPTION:
XS GIS Cut Line= 3
      3668149.63     10566960.17      3668649.61     10566560.19
      3669149.63     10566260.18
#Sta/Elev= 30
  4338.7  330.33  4345.9  329.91  4395.5  320.81  4409.9  318.88  4416.3  319.04
  4424.3  316.83  4466.7  312.11  4473.9  309.67  4626.7  292.61  4736.5  281.13
  4773.3  277.93  4822.9   276.2  4992.6  278.59  4999.3  274.73  5002.1  274.23
  5005.3  274.73  5023.7   278.6  5045.1  276.71  5087.8  276.53  5103.4  278.96
  5109.2  278.26  5146.1  281.14  5198.6  285.42  5235.5  286.99  5357.1   300.1
  5468.8   311.9  5480.4  313.88  5548.5  316.42  5554.3  315.22  5562.1  315.51
#Mann= 5 ,-1 , 0
  4338.7     .16       0  4626.7     .12       0  4999.3     .07       0
  5005.3     .12       0  5357.1     .16       0
Bank Sta=4736.5,5146.1
XS Rating Curve= 0 ,0
Exp/Cntr=0.3,0.1

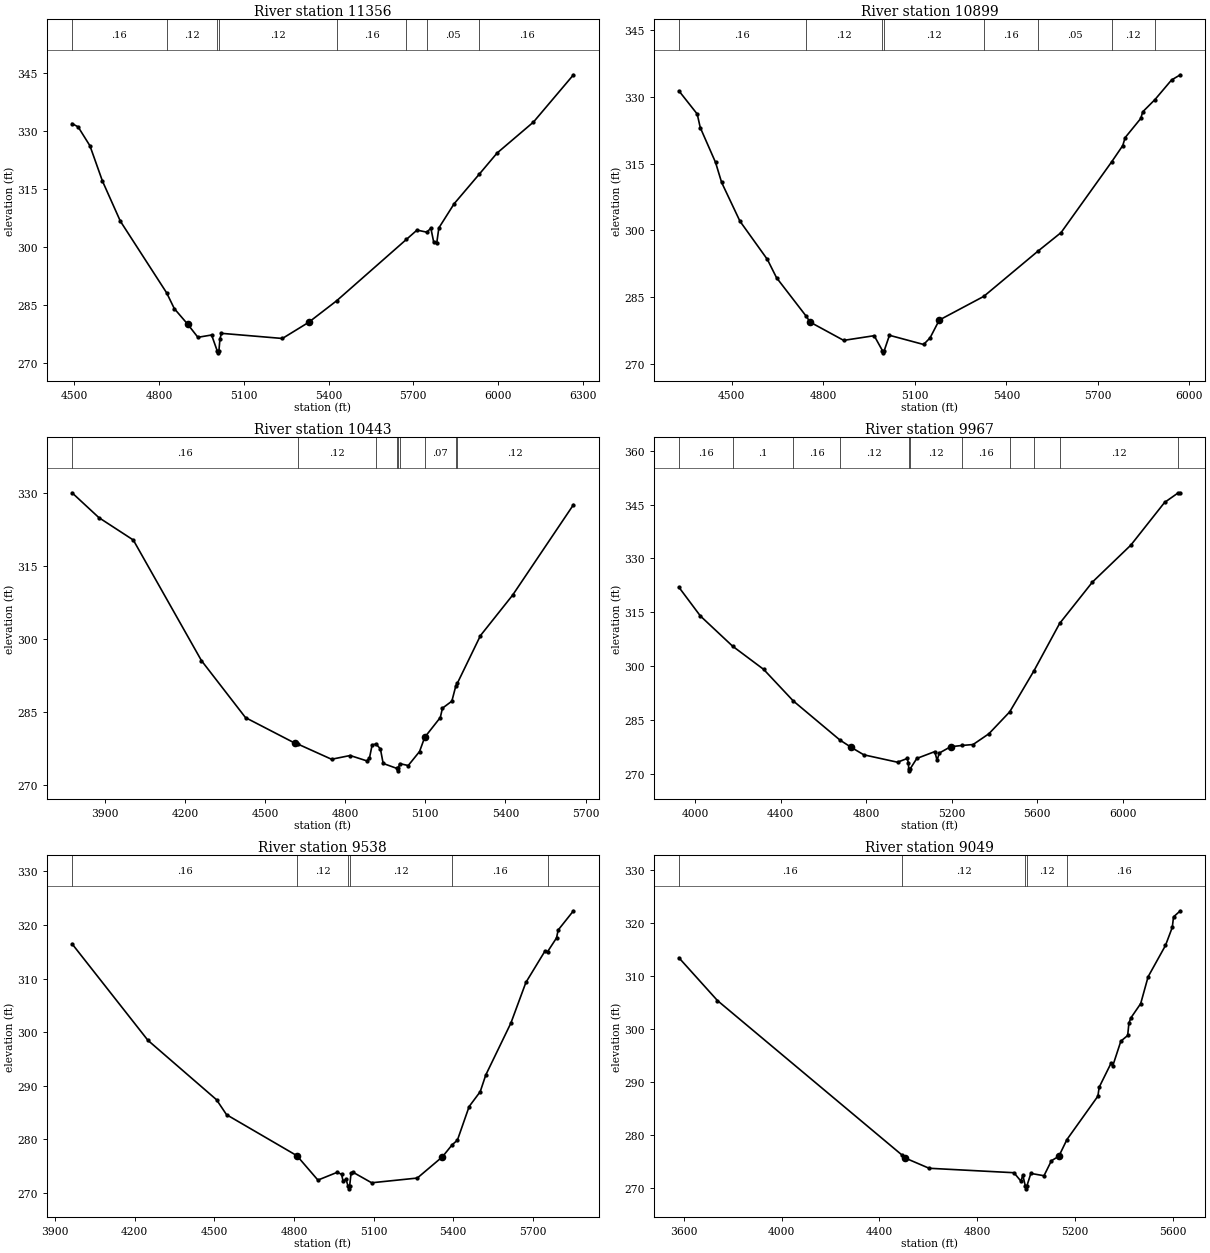
Type RM Length L Ch R = 1 ,11356   ,457,457,457
BEGIN DESCRIPTION:
UNT 142 IN UKCR 10.0
END DESCRIPTION:
XS GIS Cut Line= 3
      3668249.62     10567160.18      3668749.61     10566960.19
      3669949.57      10566660.2
#Sta/Elev= 30
  4491.7  331.98  4513.2  331.12    4555  326.23  4599.4  317.08  4662.7  306.71
  4826.7  288.14  4853.8  284.06    4901  280.04  4937.3  276.64  4985.8  277.24
  5005.7  273.12  5008.4  272.62  5011.7  273.12  5015.4  276.27  5020.8  277.67
  5236.4  276.34  5329.1   280.5  5428.2  286.08  5675.7     302  5713.1   304.4
  5747.7  303.86  5762.1  304.89  5772.4  301.21  5782.7  300.93  5790.4  304.96
  5844.5  311.22  5934.1  318.93  5996.6  324.35  6125.4  332.37  6267.1  344.61
#Mann= 8 ,-1 , 0
  4491.7     .16       0  4826.7     .12       0  5005.7     .07       0
  5011.7     .12       0  5428.2     .16       0  5675.7     .12       0
  5747.7     .05       0  5934.1     .16       0
Bank Sta=4901,5329.1
XS Rating Curve= 0 ,0
Exp/Cntr=0.3,0.1

Type RM Length L Ch R = 1 ,10899   ,456,456,456
BEGIN DESCRIPTION:
UNT 142 IN UKCR 9.0
END DESCRIPTION:
XS GIS Cut Line= 3
      3668299.61     10567310.19      3668999.61     10567310.19
      3669799.61     10566810.19
#Sta/Elev= 30
  4326.8  331.27  4386.8  326.08  4396.8  323.04  4446.8  315.26  4466.8  310.76
  4526.8  302.09  4616.8  293.51  4646.8  289.42  4743.2  280.87  4756.8  279.48
  4866.8  275.39  4966.8  276.44  4993.8   273.1  4996.5   272.6  4999.8   273.1
  5016.8  276.53  5128.8  274.47    5150  275.96  5180.1  279.94  5326.1  285.25
  5502.4  295.31  5579.3  299.53  5745.5  315.41  5781.5  319.02  5789.2  320.79
  5840.5  325.09    5847  326.58  5887.2  329.33  5941.3   333.7  5970.2  334.87
#Mann= 8 ,-1 , 0
  4326.8     .16       0  4743.2     .12       0  4993.8     .07       0
  4999.8     .12       0  5326.1     .16       0  5502.4     .05       0
  5745.5     .12       0  5887.2     .16       0
Bank Sta=4756.8,5180.1
XS Rating Curve= 0 ,0
Exp/Cntr=0.3,0.1

Type RM Length L Ch R = 1 ,10443   ,476,476,476
BEGIN DESCRIPTION:
UNT 142 IN UKCR 8.0
END DESCRIPTION:
XS GIS Cut Line= 3
      3668199.64     10567760.18      3669399.61     10567460.19
       3669799.6      10566960.2
#Sta/Elev= 30
  3777.7  330.04  3878.2  324.93    4007  320.33  4262.1  295.54  4427.1  283.82
  4612.6  278.55  4623.6  278.37  4749.2  275.26  4818.8  276.03  4880.6  274.94
  4890.9  275.46  4901.2  278.22  4915.9  278.39  4932.1  277.38  4942.4   274.4
  4993.6  273.38  4996.3  272.88  4999.6  273.38  5003.9  274.37  5036.2  273.97
  5078.6  276.85  5097.9  279.77  5156.3  283.84  5164.3  285.76  5199.5   287.2
  5214.5  290.36  5219.7  290.84  5306.7  300.69  5426.8  308.98  5654.9  327.59
#Mann= 9 ,-1 , 0
  3777.7     .16       0  4623.6     .12       0  4915.9     .07       0
  4993.6     .07       0  4999.6     .07       0  5003.9     .12       0
  5097.9     .07       0  5214.5     .05       0  5219.7     .12       0
Bank Sta=4612.6,5097.9
XS Rating Curve= 0 ,0
Exp/Cntr=0.3,0.1

Type RM Length L Ch R = 1 ,9967    ,429,429,429
BEGIN DESCRIPTION:
UNT 142 IN UKCR 7.0
END DESCRIPTION:
XS GIS Cut Line= 3
      3668699.62     10568460.18      3669599.61     10567860.19
      3669999.62     10566660.15
#Sta/Elev= 30
  3923.8  321.97  4024.4  313.96  4175.1  305.56  4320.4   299.1  4458.9  290.32
  4677.9   279.4  4730.5  277.38  4789.1  275.31  4946.9  273.25  4991.9  274.29
  4997.9  273.05  4999.4  271.35  5002.2  270.85  5005.4  271.35  5037.1   274.3
  5121.4  276.21  5131.9  273.77  5142.5  275.81  5195.2  277.56  5247.7  277.91
  5300.6  278.18  5374.4  281.17  5471.8  287.27  5585.5  298.72  5705.4  311.88
  5859.3  323.43  6038.5  333.68  6196.6  345.58  6259.9  348.23  6270.4  348.27
#Mann= 11 ,-1 , 0
  3923.8     .16       0  4175.1      .1       0  4458.9     .16       0
  4677.9     .12       0  4999.4     .07       0  5005.4     .12       0
  5247.7     .16       0  5471.8      .1       0  5585.5     .16       0
  5705.4     .12       0  6259.9     .16       0
Bank Sta=4730.5,5195.2
XS Rating Curve= 0 ,0
Exp/Cntr=0.3,0.1

Type RM Length L Ch R = 1 ,9538    ,489,489,489
BEGIN DESCRIPTION:
UNT 142 IN UKCR 6.0
END DESCRIPTION:
XS GIS Cut Line= 3
      3668999.61     10568610.19      3669899.61     10568110.19
      3670399.61     10567410.18
#Sta/Elev= 30
  3963.9  316.47  4249.9  298.48  4508.4  287.41  4546.2  284.62  4811.3  276.98
  4890.5  272.43  4963.7  273.89  4979.7  273.49  4985.5   272.2  4996.5  272.59
    5004   271.3  5006.7   270.8    5010   271.3  5015.6  273.76  5021.7  273.92
    5093  271.93    5265  272.81  5359.7  276.77  5396.4  279.01  5416.2  279.87
  5460.4  286.14  5502.2  288.91  5523.1  292.02  5617.7  301.69  5674.3  309.27
  5745.6  315.07  5756.1  315.01  5789.8  317.57  5795.9  319.04  5853.7  322.63
#Mann= 6 ,-1 , 0
  3963.9     .16       0  4811.3     .12       0    5004     .07       0
    5010     .12       0  5396.4     .16       0  5756.1     .05       0
Bank Sta=4811.3,5359.7
XS Rating Curve= 0 ,0
Exp/Cntr=0.3,0.1

Type RM Length L Ch R = 1 ,9049    ,191,191,191
BEGIN DESCRIPTION:
UNT 142 IN UKCR 5.0
END DESCRIPTION:
XS GIS Cut Line= 3
      3669099.59      10568960.2      3670299.61     10568160.19
      3670399.61      10567560.2
#Sta/Elev= 30
    3580  313.43  3737.8  305.35  4491.1  276.27  4503.9  275.69  4603.1  273.73
  4950.1  272.89  4978.7  271.29  4986.2  272.46  4996.7  270.35  4999.5  269.85
  5002.7  270.35  5019.2  272.76  5072.9  272.32  5103.3  275.15  5133.8     276
  5166.8  279.15  5293.4  287.33  5298.5  289.01  5346.7   293.5  5354.3  293.06
  5387.2   297.7  5415.1  298.77  5420.2   301.1  5427.8  302.06  5468.3  304.78
  5498.7  309.85  5569.7  315.75  5597.6  319.17  5602.6  321.14  5630.5  322.29
#Mann= 5 ,-1 , 0
    3580     .16       0  4491.1     .12       0  4996.7     .07       0
  5002.7     .12       0  5166.8     .16       0
Bank Sta=4503.9,5133.8
XS Rating Curve= 0 ,0
Exp/Cntr=0.3,0.1