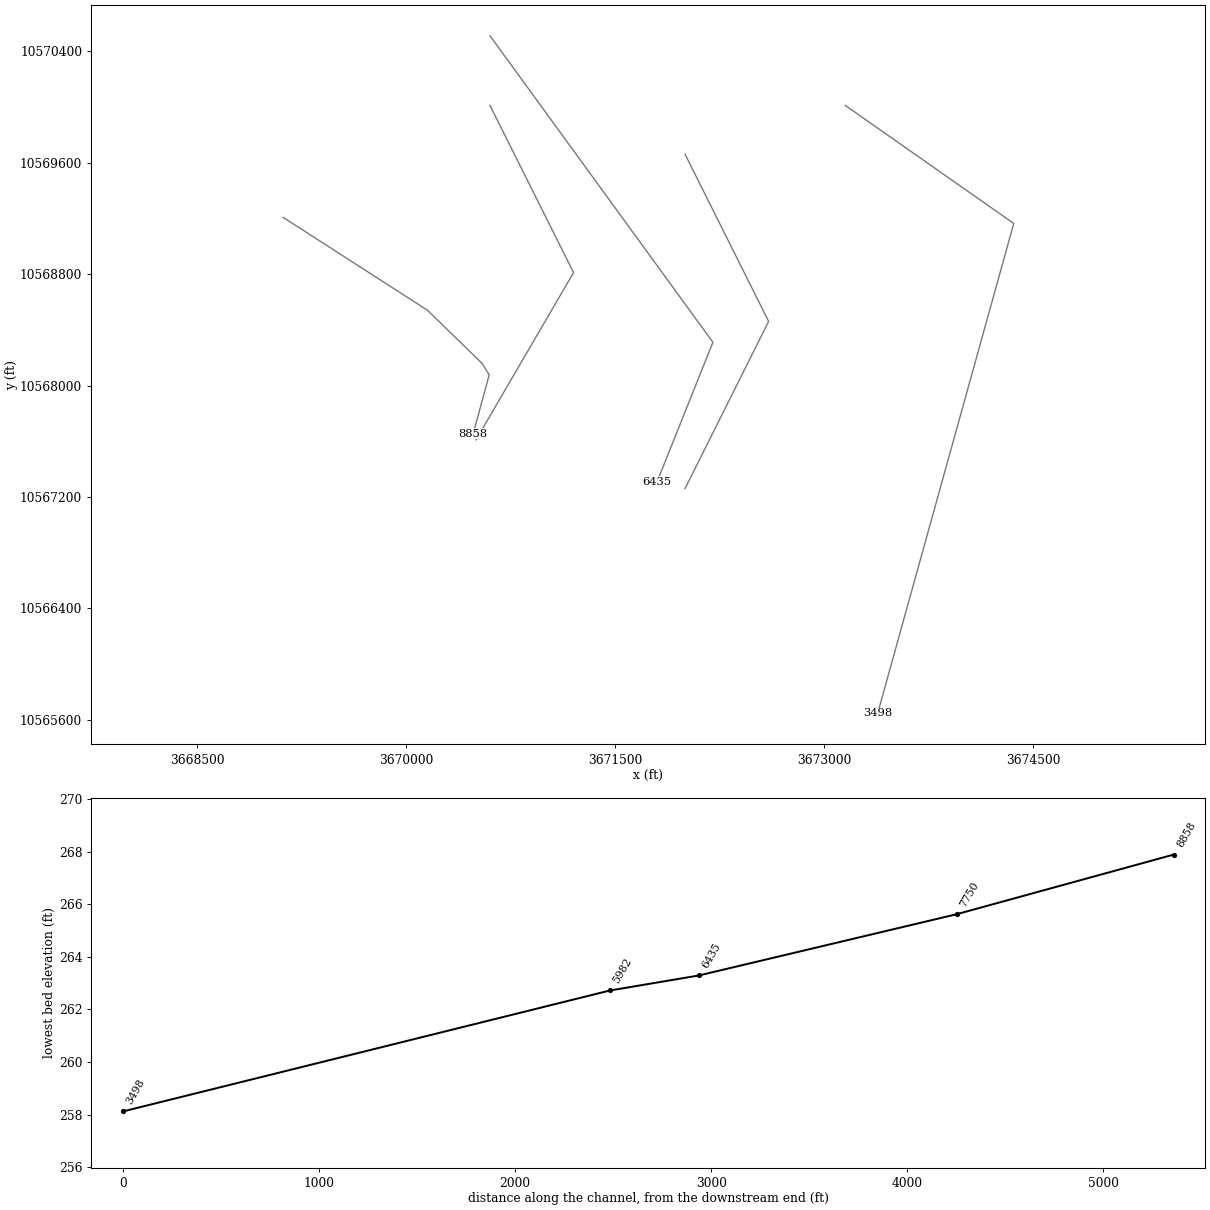
HEC-RAS study UNT 142 IN UKCR.prj: UNT 142 IN UKCR Base Level Engineering

--- UNT 142 IN UKCR.g01 (geometry) --- (continued)

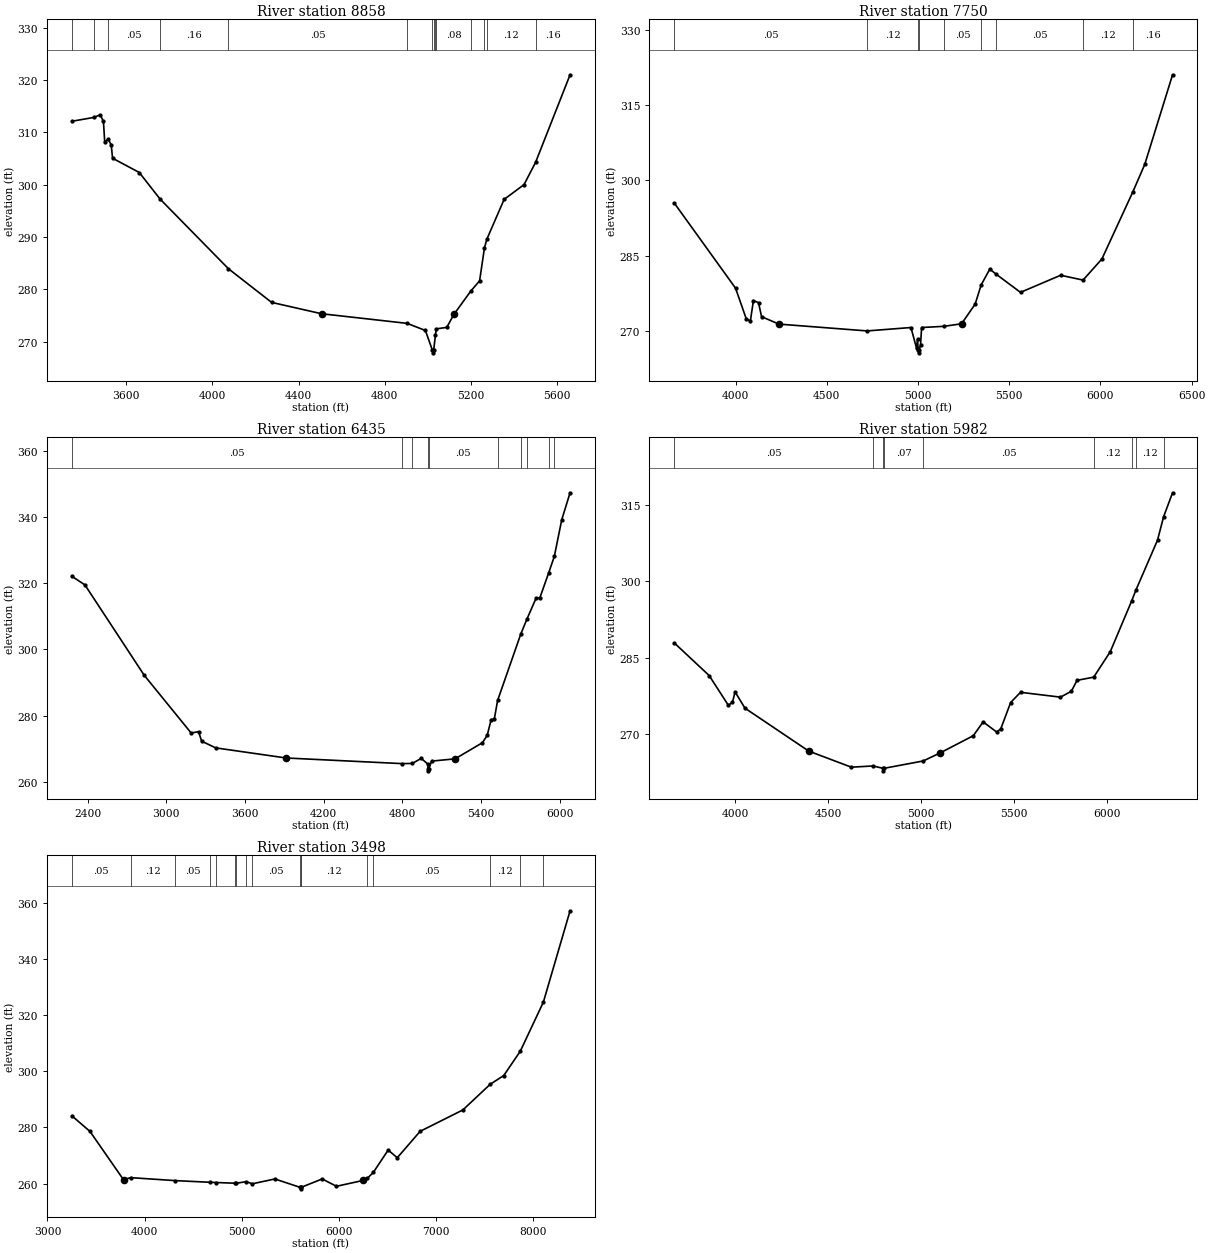
Type RM Length L Ch R = 1 ,8858    ,1108,1108,1108
BEGIN DESCRIPTION:
Mapping XS 497ed691
END DESCRIPTION:
XS GIS Cut Line= 5
      3669114.94      10569206.7      3670151.44       10568540.
      3670542.06      10568159.8      3670594.14     10568076.46
      3670479.65     10567654.92
#Sta/Elev= 30
  3347.5  312.13  3450.4  312.87  3478.8  313.37    3494  312.09  3499.9  308.16
  3515.6  308.73  3530.3  307.61  3536.2  305.07  3660.4  302.34  3756.8  297.27
  4074.4  283.95  4274.5  277.53  4506.4  275.36  4903.7  273.52  4988.6  272.16
  5020.9  268.39  5023.7  267.89  5026.9  268.39  5035.3  271.32  5038.9  272.47
  5087.7  272.75  5121.1  275.25  5199.5   279.7  5240.1  281.64  5262.7  287.96
    5274  289.62  5354.1  297.21  5446.3  300.02  5500.1  304.29  5660.1  321.01
#Mann= 14 ,-1 , 0
  3347.5     .05       0  3450.4     .08       0  3515.6     .05       0
  3756.8     .16       0  4074.4     .05       0  4903.7     .08       0
  5020.9     .07       0  5026.9     .08       0  5035.3     .12       0
  5038.9     .08       0  5199.5     .05       0  5262.7     .08       0
    5274     .12       0  5500.1     .16       0
Bank Sta=4506.4,5121.1
XS Rating Curve= 0 ,0
Exp/Cntr=0.3,0.1

Type RM Length L Ch R = 1 ,7750    ,1315,1315,1315
BEGIN DESCRIPTION:
UNT 142 IN UKCR 4.0
END DESCRIPTION:
XS GIS Cut Line= 3
       3670599.6     10570010.21      3671199.61     10568810.19
      3670499.61      10567610.2
#Sta/Elev= 30
  3664.4  295.46  3999.8  278.51  4058.5  272.39  4080.9  271.96  4097.7  276.04
  4125.6  275.63  4142.4  272.83  4237.4  271.35  4721.1  269.99  4961.3  270.67
  4992.1  266.51  4997.7  268.34  5000.3  266.12    5003  265.62  5006.3  266.12
  5013.9  267.26  5019.7  270.67  5143.5  270.91  5238.8  271.42  5313.3  275.35
    5346  279.16  5393.5  282.32  5426.1  281.36  5561.8  277.68  5781.7  281.09
  5904.7  280.13  6007.9  284.33  6176.7  297.65  6242.7  303.18  6395.3  321.07
#Mann= 9 ,-1 , 0
  3664.4     .05       0  4721.1     .12       0  5000.3     .07       0
  5006.3     .12       0  5143.5     .05       0    5346     .16       0
  5426.1     .05       0  5904.7     .12       0  6176.7     .16       0
Bank Sta=4237.4,5238.8
XS Rating Curve= 0 ,0
Exp/Cntr=0.3,0.1

Type RM Length L Ch R = 1 ,6435    ,453,453,453
BEGIN DESCRIPTION:
UNT 142 IN UKCR 3.0
END DESCRIPTION:
XS GIS Cut Line= 3
      3670599.63     10570510.17      3672199.61     10568310.19
      3671799.61     10567310.19
#Sta/Elev= 30
  2280.1  322.13  2379.4  319.53  2831.5  292.19  3189.3  274.73  3245.7  275.14
  3268.9  272.27  3375.5  270.24  3912.2  267.18    4798  265.47  4875.8  265.53
  4942.8  267.07    4993  265.32  4994.3  263.79    4997  263.29  5000.3  263.79
  5021.9  266.23    5201  266.92  5409.6   271.8    5446  274.05  5475.6  278.74
  5499.8  278.92  5525.1  284.58  5701.3  304.61  5747.7  309.11  5817.6  315.45
  5847.2  315.62  5915.2  323.26  5957.4  328.14  6014.1  339.26  6077.4  347.39
#Mann= 10 ,-1 , 0
  2280.1     .05       0    4798     .07       0  4875.8     .05       0
  4994.3     .03       0  5000.3     .05       0  5525.1     .16       0
  5701.3     .12       0  5747.7     .16       0  5915.2     .12       0
  5957.4     .16       0
Bank Sta=3912.2,5201
XS Rating Curve= 0 ,0
Exp/Cntr=0.3,0.1

Type RM Length L Ch R = 1 ,5982    ,2484,2484,2484
BEGIN DESCRIPTION:
UNT 142 IN UKCR 2.0
END DESCRIPTION:
XS GIS Cut Line= 3
      3671999.62     10569660.17      3672599.61     10568460.19
      3671999.59     10567260.16
#Sta/Elev= 30
  3672.4  287.87  3859.7  281.47  3963.1  275.62  3985.4  276.23  3999.4  278.26
  4052.5  275.05  4396.3   266.6  4625.5  263.44  4742.6  263.68  4795.8  263.22
  4798.6  262.72  4801.8  263.22  5012.6  264.66  5103.5  266.24  5282.4  269.63
  5335.5  272.35  5408.1  270.36  5430.5  270.99  5483.6  276.16  5536.7  278.17
  5751.9  277.22  5810.6  278.38  5841.4  280.53  5930.9  281.15  6020.3  286.17
  6136.1  296.21  6158.3  298.28  6274.6   308.1  6307.5  312.72  6355.7  317.43
#Mann= 9 ,-1 , 0
  3672.4     .05       0  4742.6     .07       0  4795.8     .07       0
  4801.8     .07       0  5012.6     .05       0  5930.9     .12       0
  6136.1     .16       0  6158.3     .12       0  6307.5     .16       0
Bank Sta=4396.3,5103.5
XS Rating Curve= 0 ,0
Exp/Cntr=0.3,0.1

Type RM Length L Ch R = 1 ,3498    ,0,0,0
BEGIN DESCRIPTION:
UNT 142 IN UKCR 1.0
END DESCRIPTION:
XS GIS Cut Line= 3
      3673149.57     10570010.21      3674358.73      10569162.9
      3673382.17     10565647.29
#Sta/Elev= 30
  3251.2  284.13  3437.4  278.56  3782.6  261.35  3855.5  262.11  4313.2  261.05
  4676.5  260.45  4735.7  260.37    4926  260.13  4941.6   260.1  5044.5  260.68
  5107.6  259.92  5339.3  261.63    5602  258.62  5604.7  258.12    5608  258.62
    5609  258.64    5826  261.64  5973.4  259.03  6245.8   261.1  6292.2  261.89
  6353.4  264.03  6505.2  271.93  6598.6  269.19  6833.8   278.6  7273.3  286.21
    7555  295.36  7694.2  298.47    7864  307.11  8101.5  324.59  8376.4  357.14
#Mann= 17 ,-1 , 0
  3251.2     .05       0  3855.5     .12       0  4313.2     .05       0
  4676.5     .16       0  4735.7     .12       0    4926     .16       0
  4941.6     .12       0  5044.5     .16       0  5107.6     .05       0
    5602     .07       0    5608     .05       0    5609     .12       0
  6292.2     .16       0  6353.4     .05       0    7555     .12       0
    7864     .16       0  8101.5     .12       0
Bank Sta=3782.6,6245.8
XS Rating Curve= 0 ,0
Exp/Cntr=0.3,0.1

Chan Stop Cuts=-1
Use User Specified Reach Order=0
Composite Channel Slope=5