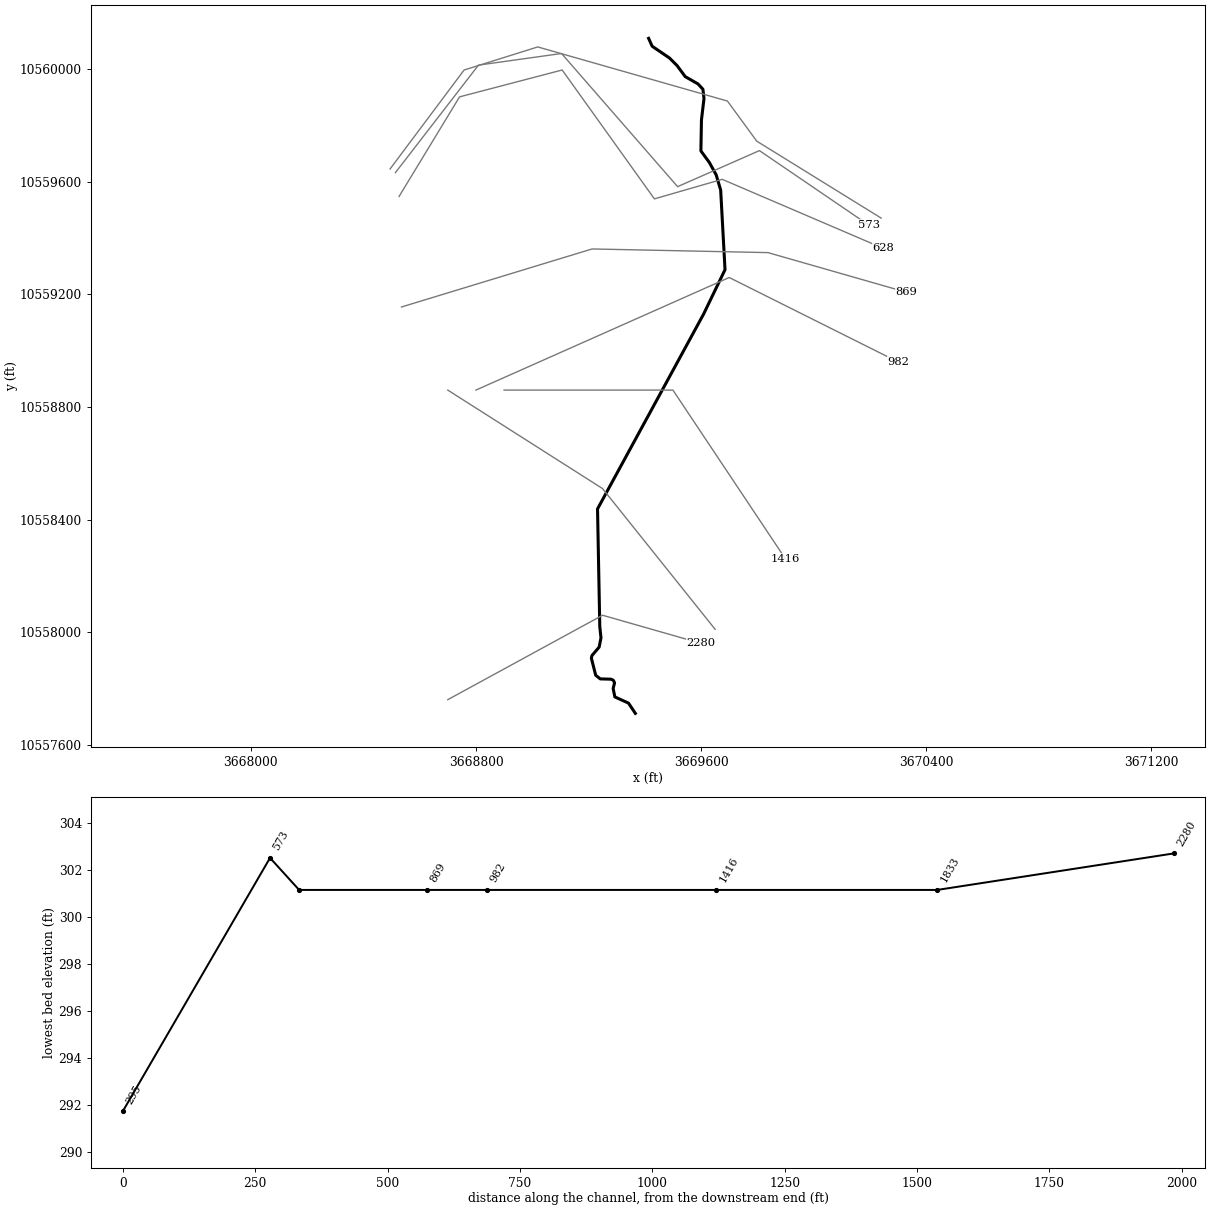
--- UNT 143 IN UKCR.prj (project) ---

Proj Title=UNT 143 IN UKCR Base Level Engineering
Current Plan=p01
Default Exp/Contr=0.3,0.1
English Units
Geom File=g01
Flow File=f01
Plan File=p01
Y Axis Title=Elevation
X Axis Title(PF)=Main Channel Distance
X Axis Title(XS)=Station
BEGIN DESCRIPTION:
UNT 143 IN UKCR
END DESCRIPTION:
DSS Export Rating Curves= 0
DSS Export Rating Curve Sorted= 0
DSS Export Volume Flow Curves= 0
DXF OffsetX= 0
DXF OffsetY= 0
DXF ScaleX= 1
DXF ScaleY= 10

--- UNT 143 IN UKCR.p01 (plan) ---

Plan Title=Multiple Run
Short Identifier=Multiple
Geom File=g01
Flow File=f01
Subcritical Flow
K Sum by GR= 0
Std Step Tol= 0.01
Critical Tol= 0.01
Num of Std Step Trials= 20
Max Error Tol= 0.3
Flow Tol Ratio= 0.001
Split Flow NTrial= 30
Split Flow Tol= 0.02
Split Flow Ratio= 0.02
Log Output Level= 0
Friction Slope Method= 1
Unsteady Friction Slope Method= 2
Unsteady Bridges Friction Slope Method= 1
Parabolic Critical Depth
Global Vel Dist=  1 , 1 , 1
Global Log Level= 0
CheckData=True
Encroach Param= -1, 0, 0, 0
BEGIN DESCRIPTION:
Multiple Run
END DESCRIPTION:

--- UNT 143 IN UKCR.f01 (steady flow) ---

Flow Title=Multiple
Number of Profiles=7
Profile Names=10-year,25-year,50-year,1pct_min,100-year,1pct_plu,500-year
River Rch & RM= UNT 143 IN UKCR,Reach-1,2280
     469     629     760     675     912    1234    1321
Boundary for River Rch & Prof#=UNT 143 IN UKCR,Reach-1,1
Up Type=0
Dn Type=3
Dn Slope=0.005
Boundary for River Rch & Prof#=UNT 143 IN UKCR,Reach-1,2
Up Type=0
Dn Type=3
Dn Slope=0.005
Boundary for River Rch & Prof#=UNT 143 IN UKCR,Reach-1,3
Up Type=0
Dn Type=3
Dn Slope=0.005
Boundary for River Rch & Prof#=UNT 143 IN UKCR,Reach-1,4
Up Type=0
Dn Type=3
Dn Slope=0.005
Boundary for River Rch & Prof#=UNT 143 IN UKCR,Reach-1,5
Up Type=0
Dn Type=3
Dn Slope=0.005
Boundary for River Rch & Prof#=UNT 143 IN UKCR,Reach-1,6
Up Type=0
Dn Type=3
Dn Slope=0.005
Boundary for River Rch & Prof#=UNT 143 IN UKCR,Reach-1,7
Up Type=0
Dn Type=3
Dn Slope=0.005

--- UNT 143 IN UKCR.g01 (geometry) ---

Geom Title=Existing Conditions
Program Version=4.10

River Reach=UNT 143 IN UKCR ,Reach-1
Reach XY= 30
      3669366.18     10557711.51      3669341.75       10557748.
      3669293.25       10557770.      3669287.25       10557800.
      3669292.25       10557820.        3669288.       10557829.
       3669279.5       10557833.       3669241.5       10557834.
      3669225.25       10557847.      3669209.75       10557908.
        3669212.       10557917.       3669237.5       10557947.
        3669244.       10557980.      3669239.75       10558020.
      3669231.75       10558438.       3669608.5       10559130.
      3669684.75       10559288.      3669669.25       10559571.
      3669653.25       10559625.        3669629.       10559669.
        3669599.       10559710.        3669601.       10559820.
        3669610.       10559896.      3669606.25       10559929.
      3669588.75       10559948.      3669543.25       10559974.
       3669514.5       10560013.       3669487.5       10560040.
      3669425.75       10560082.      3669413.25       10560110.

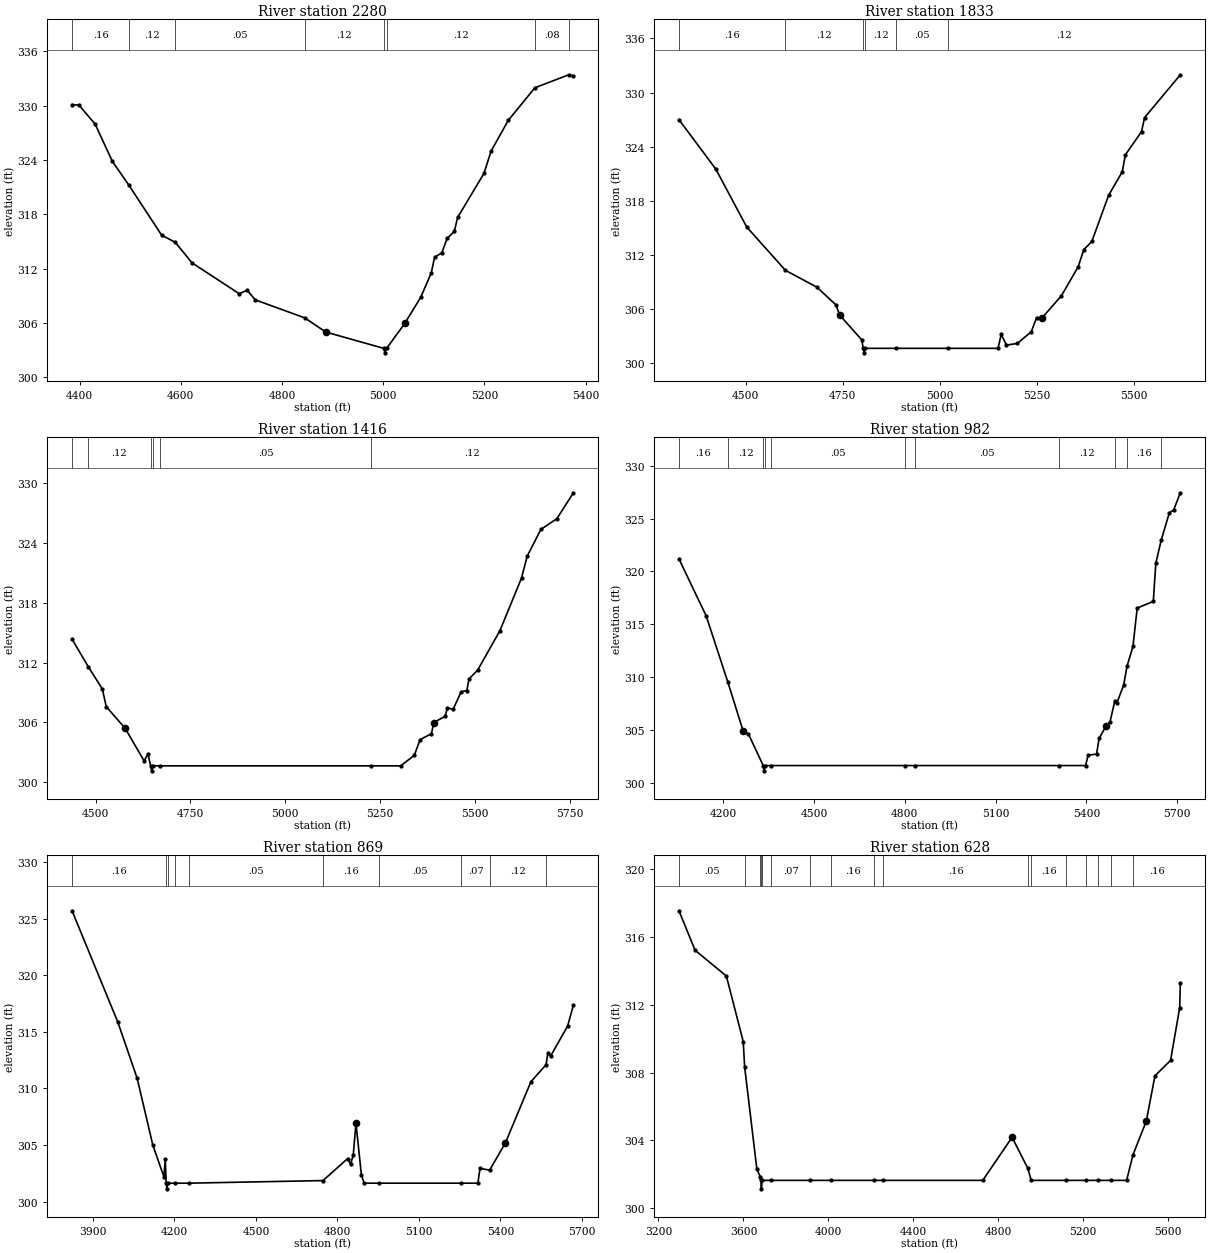
Type RM Length L Ch R = 1 ,2280    ,447,447,447
BEGIN DESCRIPTION:
UNT 143 IN UKCR 5.0
END DESCRIPTION:
XS GIS Cut Line= 3
      3668699.58     10557760.17      3669249.61     10558060.19
      3669599.57      10557960.2
#Sta/Elev= 30
  4385.2  330.12    4399  330.06  4430.8  327.97    4465  323.84  4497.8  321.19
  4562.3  315.69  4589.2   314.9  4622.1  312.64  4715.6  309.22  4731.2  309.61
  4747.4  308.54  4845.1  306.55  4886.4  304.99  5000.7  303.19  5003.4  302.69
  5006.7  303.19  5042.9  305.97  5074.1  308.84  5094.9  311.52  5101.4  313.26
  5115.7  313.74  5126.1  315.33  5140.4   316.1  5146.9  317.65  5198.9  322.51
  5213.2     325    5247  328.38  5299.5  331.98  5366.5  333.42  5375.7  333.33
#Mann= 8 ,-1 , 0
  4385.2     .16       0  4497.8     .12       0  4589.2     .05       0
  4845.1     .12       0  5000.7     .07       0  5006.7     .12       0
  5299.5     .08       0  5366.5     .12       0
Bank Sta=4886.4,5042.9
XS Rating Curve= 0 ,0
Exp/Cntr=0.3,0.1

Type RM Length L Ch R = 1 ,1833    ,417,417,417
BEGIN DESCRIPTION:
UNT 143 IN UKCR 4.0
END DESCRIPTION:
XS GIS Cut Line= 3
      3668699.65     10558860.16      3669249.61     10558510.19
      3669649.62     10558010.18
#Sta/Elev= 30
  4327.7  326.99  4422.5  321.52  4502.1   315.1    4602  310.29  4683.2  308.42
  4732.4  306.45  4741.7  305.33  4799.2  302.56  4802.2  301.64  4804.9  301.14
  4808.2  301.64  4887.1  301.64  5021.3  301.64  5150.1  301.64  5158.1  303.19
  5171.7     302  5199.7  302.18  5235.7  303.48  5249.3  305.04  5263.7  305.03
  5313.3  307.46  5356.6  310.69    5371  312.58  5391.8  313.49    5435  318.61
  5470.2  321.21  5478.2  323.09  5519.8  325.67  5527.8  327.23  5619.9  331.97
#Mann= 6 ,-1 , 0
  4327.7     .16       0    4602     .12       0  4802.2    .033       0
  4808.2     .12       0  4887.1     .05       0  5021.3     .12       0
Bank Sta=4741.7,5263.7
XS Rating Curve= 0 ,0
Exp/Cntr=0.3,0.1

Type RM Length L Ch R = 1 ,1416    ,434,434,434
BEGIN DESCRIPTION:
UNT 143 IN UKCR 3.0
END DESCRIPTION:
XS GIS Cut Line= 3
       3668899.6     10558860.19      3669499.61     10558860.19
       3669899.6      10558260.2
#Sta/Elev= 30
    4438  314.35  4480.6   311.6    4518  309.34    4528  307.59    4578   305.4
    4628  302.13    4638  302.84    4645  301.64  4647.8  301.14    4651  301.64
  4670.4  301.64  5225.7  301.64  5303.9  301.64    5340   302.7    5355  304.27
    5385  304.86    5391  305.99  5421.1  306.61  5427.1  307.46  5442.1  307.31
  5463.2  309.07  5478.2   309.2  5484.2  310.37  5506.7  311.24  5565.3  315.19
  5622.4  320.49  5637.4  322.69  5673.5  325.37  5715.5  326.44  5759.1  329.04
#Mann= 6 ,-1 , 0
    4438     .16       0  4480.6     .12       0    4645    .033       0
    4651     .12       0  4670.4     .05       0  5225.7     .12       0
Bank Sta=4578,5391
XS Rating Curve= 0 ,0
Exp/Cntr=0.3,0.1

Type RM Length L Ch R = 1 ,982     ,113,113,113
BEGIN DESCRIPTION:
UNT 143 IN UKCR 2.0
END DESCRIPTION:
XS GIS Cut Line= 3
       3668799.6     10558860.18      3669699.61     10559260.19
      3670299.59      10558960.2
#Sta/Elev= 30
  4054.5  321.18  4144.1  315.81  4215.9  309.53  4265.9  304.95  4283.6  304.64
  4332.6  301.64  4335.4  301.14  4338.6  301.64  4357.3  301.64  4800.4  301.64
  4834.7  301.64  5308.8  301.64  5397.2  301.64  5405.6  302.61  5433.5  302.73
  5441.9  304.21  5464.3  305.35  5478.2   305.8  5493.4  307.71  5500.6  307.56
  5522.9  309.24  5534.3  311.06  5553.7  312.91  5567.7  316.54  5620.8  317.16
  5629.2  320.77  5647.1  322.97  5673.9  325.55  5687.9   325.8  5710.2  327.44
#Mann= 11 ,-1 , 0
  4054.5     .16       0  4215.9     .12       0  4332.6    .033       0
  4338.6     .12       0  4357.3     .05       0  4800.4     .16       0
  4834.7     .05       0  5308.8     .12       0  5493.4     .05       0
  5534.3     .16       0  5647.1     .05       0
Bank Sta=4265.9,5464.3
XS Rating Curve= 0 ,0
Exp/Cntr=0.3,0.1

Type RM Length L Ch R = 1 ,869     ,241,241,241
BEGIN DESCRIPTION:
Mapping XS 8916099c
END DESCRIPTION:
XS GIS Cut Line= 4
      3668535.34      10559155.5      3669212.42     10559361.66
      3669837.42     10559348.64      3670330.02     10559207.59
#Sta/Elev= 30
  3823.3  325.69  3991.8  315.86  4062.7  310.92  4120.5  305.01  4161.3  302.21
  4166.5  303.76  4169.7  301.64  4172.5  301.14  4175.7  301.64  4203.1  301.64
  4252.7  301.64    4747  301.87  4837.6  303.81  4848.3   303.3  4858.3  304.12
  4868.3  306.93  4888.3  302.37  4898.3  301.64  4954.3  301.64  5256.2  301.64
  5316.9  301.64  5324.9  302.95  5360.2  302.79  5418.2  305.19  5512.1  310.59
  5568.2  312.11  5574.6  313.13    5585  312.87  5647.4  315.52  5668.6  317.36
#Mann= 10 ,-1 , 0
  3823.3     .16       0  4169.7    .033       0  4175.7     .16       0
  4203.1      .1       0  4252.7     .05       0    4747     .16       0
  4954.3     .05       0  5256.2     .07       0  5360.2     .12       0
  5568.2     .05       0
Bank Sta=4868.3,5418.2
XS Rating Curve= 0 ,0
Exp/Cntr=0.3,0.1

Type RM Length L Ch R = 1 ,628     ,55,55,55
BEGIN DESCRIPTION:
Mapping XS 0aaf427a
END DESCRIPTION:
XS GIS Cut Line= 6
      3668526.64     10559548.27       3668741.5     10559902.03
      3669106.08     10559997.51      3669433.77     10559539.61
      3669674.66     10559609.06      3670246.09     10559364.17
#Sta/Elev= 30
  3296.9  317.55  3372.6  315.22  3519.9   313.7  3599.3  309.83  3605.8  308.35
  3663.3  302.32  3679.5  301.85  3682.2  301.64    3685  301.14  3688.2  301.64
  3730.8  301.64  3914.1  301.64  4013.6  301.64  4216.6  301.64  4259.2  301.64
  4726.7  301.64  4864.8  304.18  4938.5  302.36  4955.1  301.64  5118.7  301.64
  5210.8  301.64    5268  301.64    5331  301.64    5404  301.64    5434  303.15
  5496.4  305.13  5537.4  307.81  5610.9  308.72  5653.9  311.84  5656.9  313.31
#Mann= 17 ,-1 , 0
  3296.9     .05       0  3605.8     .07       0  3679.5      .1       0
  3682.2     .07       0  3688.2      .1       0  3730.8     .07       0
  3914.1      .1       0  4013.6     .16       0  4216.6     .12       0
  4259.2     .16       0  4938.5     .07       0  4955.1     .16       0
  5118.7     .07       0  5210.8     .12       0    5268     .05       0
    5331     .12       0    5434     .16       0
Bank Sta=4864.8,5496.4
XS Rating Curve= 0 ,0
Exp/Cntr=0.3,0.1

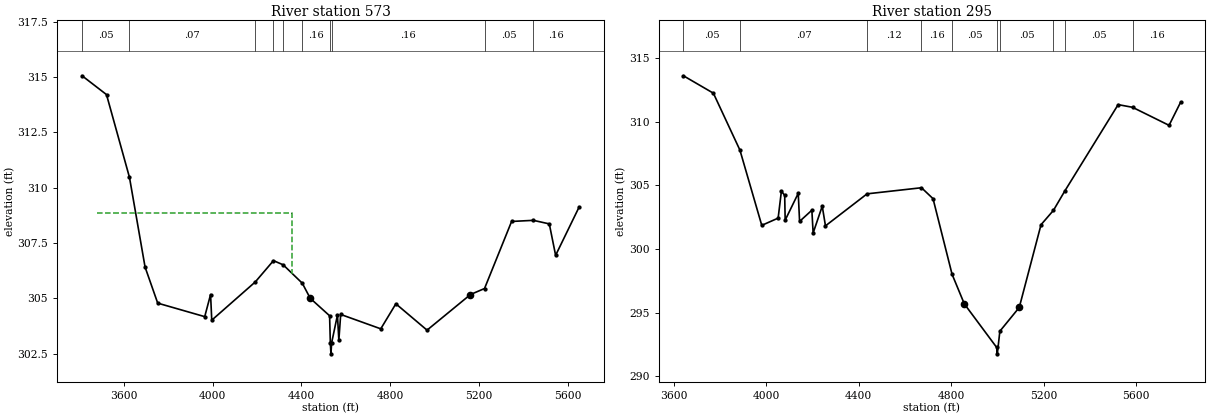
Type RM Length L Ch R = 1 ,573     ,278,278,278
BEGIN DESCRIPTION:
Mapping XS f1412015
END DESCRIPTION:
XS GIS Cut Line= 6
      3668513.66     10559632.97      3668808.77     10560014.87
      3669103.91     10560056.11      3669516.24     10559583.02
      3669807.03     10559711.06      3670195.03     10559446.67
#Sta/Elev= 30
  3410.7  315.06  3520.8  314.21  3624.4  310.47  3694.7  306.42  3751.7  304.79
  3963.7  304.18  3990.1  305.18  3995.4  304.02  4191.9  305.75  4273.7  306.71
  4317.6  306.52  4403.7  305.69  4439.4  305.01  4526.8  304.22  4530.1     303
  4532.8   302.5  4536.1     303  4562.2  304.25  4568.5  303.11  4576.8  304.28
  4757.5  303.63  4825.6  304.76  4966.2  303.57  5162.1  305.18  5225.4  305.45
  5347.5  308.48  5445.6  308.53  5517.5  308.37    5546  306.95  5652.4  309.14
#Mann= 10 ,-1 , 0
  3410.7     .05       0  3624.4     .07       0  4191.9     .12       0
  4273.7     .16       0  4317.6     .12       0  4403.7     .16       0
  4530.1     .07       0  4536.1     .16       0  5225.4     .05       0
  5445.6     .16       0
#XS Ineff= 1 ,-1
 3477.27 4358.52  308.88
Permanent Ineff=
       F
Bank Sta=4439.4,5162.1
XS Rating Curve= 0 ,0
Exp/Cntr=0.3,0.1

Type RM Length L Ch R = 1 ,295     ,0,0,0
BEGIN DESCRIPTION:
UNT 143 IN UKCR 1.0
END DESCRIPTION:
XS GIS Cut Line= 6
      3668494.63      10559645.9      3668757.64     10559997.44
      3669019.36     10560079.47      3669693.28      10559887.2
      3669797.53     10559744.63      3670239.44     10559471.37
#Sta/Elev= 30
  3642.2  313.63  3771.7  312.26  3886.5  307.78  3980.9  301.86  4051.7  302.43
  4065.8  304.55    4080  304.22  4082.1  302.27  4138.6  304.38  4144.4  302.17
  4197.5  303.05    4203  301.26  4242.4  303.37  4256.3  301.82  4436.2  304.34
  4671.5  304.82  4721.4  303.96  4803.7  298.01  4856.7  295.68  4996.7  292.25
  4999.4  291.75  5010.3  293.53  5094.2   295.4  5188.3  301.91    5242  303.04
    5291  304.56  5521.8  311.36  5583.9  311.15  5741.9  309.73  5791.6  311.54
#Mann= 10 ,-1 , 0
  3642.2     .05       0  3886.5     .07       0  4436.2     .12       0
  4671.5     .16       0  4803.7     .05       0  4996.7     .03       0
  5010.3     .05       0    5242     .16       0    5291     .05       0
  5583.9     .16       0
Bank Sta=4856.7,5094.2
XS Rating Curve= 0 ,0
Exp/Cntr=0.3,0.1

Chan Stop Cuts=-1
Use User Specified Reach Order=0
Composite Channel Slope=5