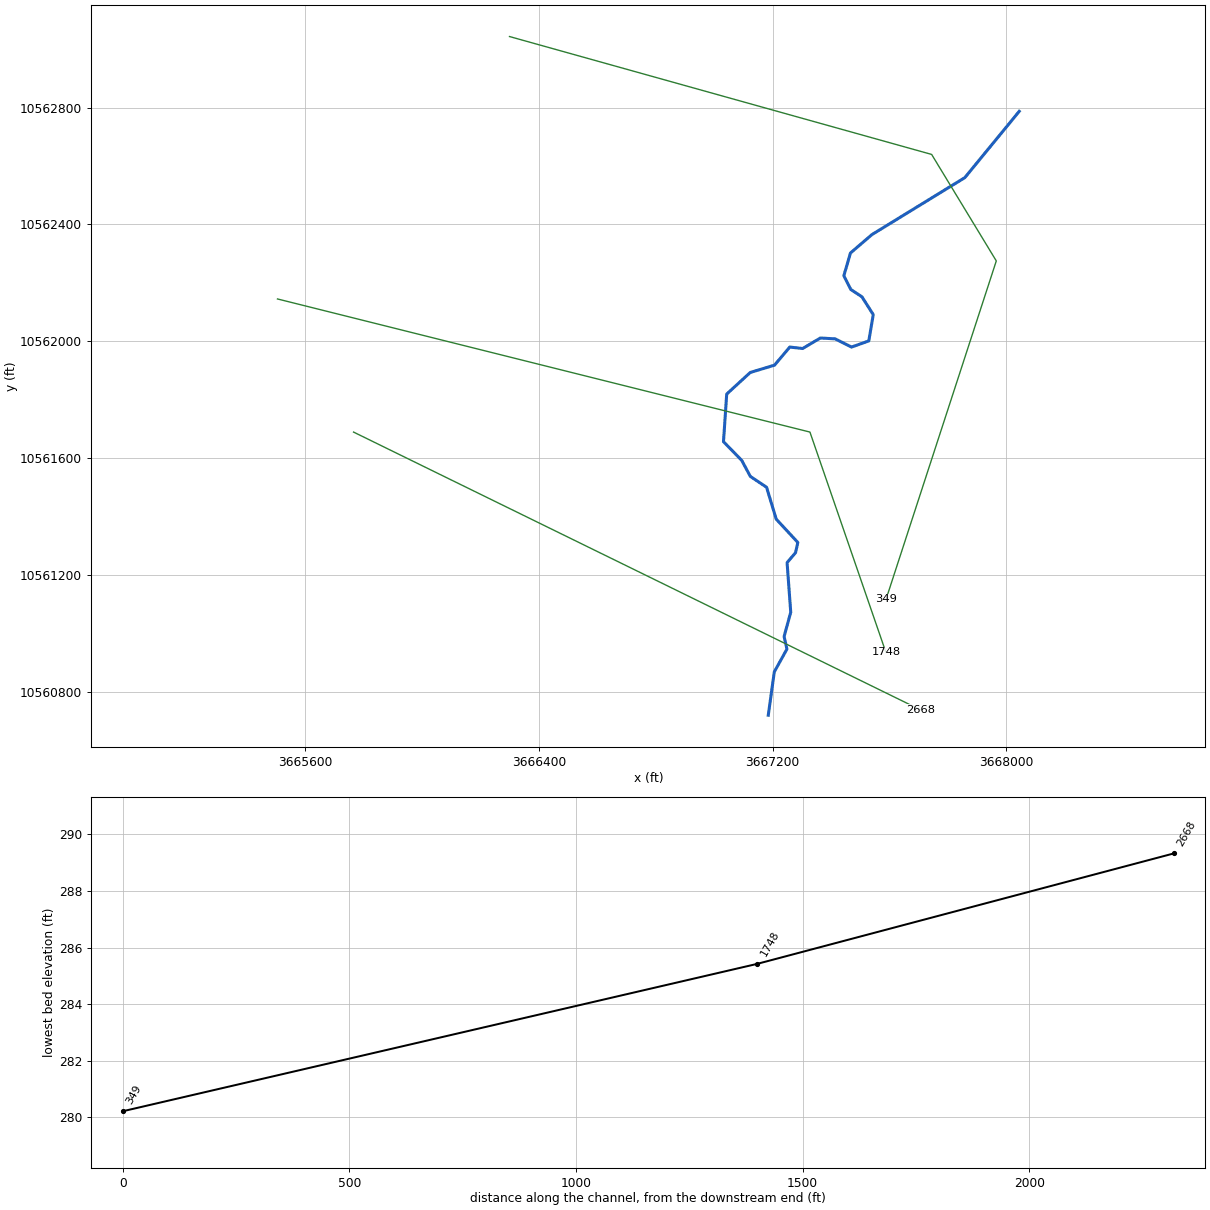
--- UNT 145 IN UKCR.prj (project) ---

Proj Title=UNT 145 IN UKCR Base Level Engineering
Current Plan=p01
Default Exp/Contr=0.3,0.1
English Units
Geom File=g01
Flow File=f01
Plan File=p01
BEGIN DESCRIPTION:
UNT 145 IN UKCR
END DESCRIPTION:

--- UNT 145 IN UKCR.p01 (plan) ---

Plan Title=Multiple Run
Short Identifier=Multiple
Geom File=g01
Flow File=f01
Subcritical Flow
K Sum by GR= 0
Std Step Tol= 0.01
Critical Tol= 0.01
Num of Std Step Trials= 20
Max Error Tol= 0.3
Flow Tol Ratio= 0.001
Split Flow NTrial= 30
Split Flow Tol= 0.02
Split Flow Ratio= 0.02
Log Output Level= 0
Friction Slope Method= 1
Unsteady Friction Slope Method= 2
Unsteady Bridges Friction Slope Method= 1
Parabolic Critical Depth
Global Vel Dist=  1 , 1 , 1
Global Log Level= 0
CheckData=True
Encroach Param= -1, 0, 0, 0
BEGIN DESCRIPTION:
Multiple Run
END DESCRIPTION:

--- UNT 145 IN UKCR.f01 (steady flow) ---

Flow Title=Multiple
Number of Profiles=7
Profile Names=10-year,25-year,50-year,1pct_min,100-year,1pct_plu,500-year
River Rch & RM= UNT 145 IN UKCR,Reach-1,2668
     716     992    1225    1113    1505    2035    2278
Boundary for River Rch & Prof#=UNT 145 IN UKCR,Reach-1,1
Up Type=0
Dn Type=3
Dn Slope=0.005
Boundary for River Rch & Prof#=UNT 145 IN UKCR,Reach-1,2
Up Type=0
Dn Type=3
Dn Slope=0.005
Boundary for River Rch & Prof#=UNT 145 IN UKCR,Reach-1,3
Up Type=0
Dn Type=3
Dn Slope=0.005
Boundary for River Rch & Prof#=UNT 145 IN UKCR,Reach-1,4
Up Type=0
Dn Type=3
Dn Slope=0.005
Boundary for River Rch & Prof#=UNT 145 IN UKCR,Reach-1,5
Up Type=0
Dn Type=3
Dn Slope=0.005
Boundary for River Rch & Prof#=UNT 145 IN UKCR,Reach-1,6
Up Type=0
Dn Type=3
Dn Slope=0.005
Boundary for River Rch & Prof#=UNT 145 IN UKCR,Reach-1,7
Up Type=0
Dn Type=3
Dn Slope=0.005

--- UNT 145 IN UKCR.g01 (geometry) ---

Geom Title=Existing Conditions

River Reach=UNT 145 IN UKCR,Reach-1
Reach XY= 30
      3667184.83     10560719.67      3667205.50     10560868.00
      3667248.75     10560946.00      3667239.00     10560989.00
      3667261.75     10561072.00      3667249.25     10561242.00
      3667278.25     10561276.00      3667286.00     10561311.00
      3667212.00     10561391.00      3667179.00     10561500.00
      3667123.50     10561537.00      3667094.00     10561592.00
      3667031.50     10561656.00      3667042.50     10561819.00
      3667123.25     10561893.00      3667206.25     10561918.00
      3667258.50     10561980.00      3667302.50     10561975.00
      3667363.25     10562011.00      3667413.75     10562008.00
      3667470.00     10561980.00      3667529.00     10562001.00
      3667544.25     10562091.00      3667505.50     10562152.00
      3667467.50     10562177.00      3667443.50     10562224.00
      3667466.25     10562302.00      3667539.75     10562365.00
      3667857.75     10562560.00      3668044.00     10562787.00

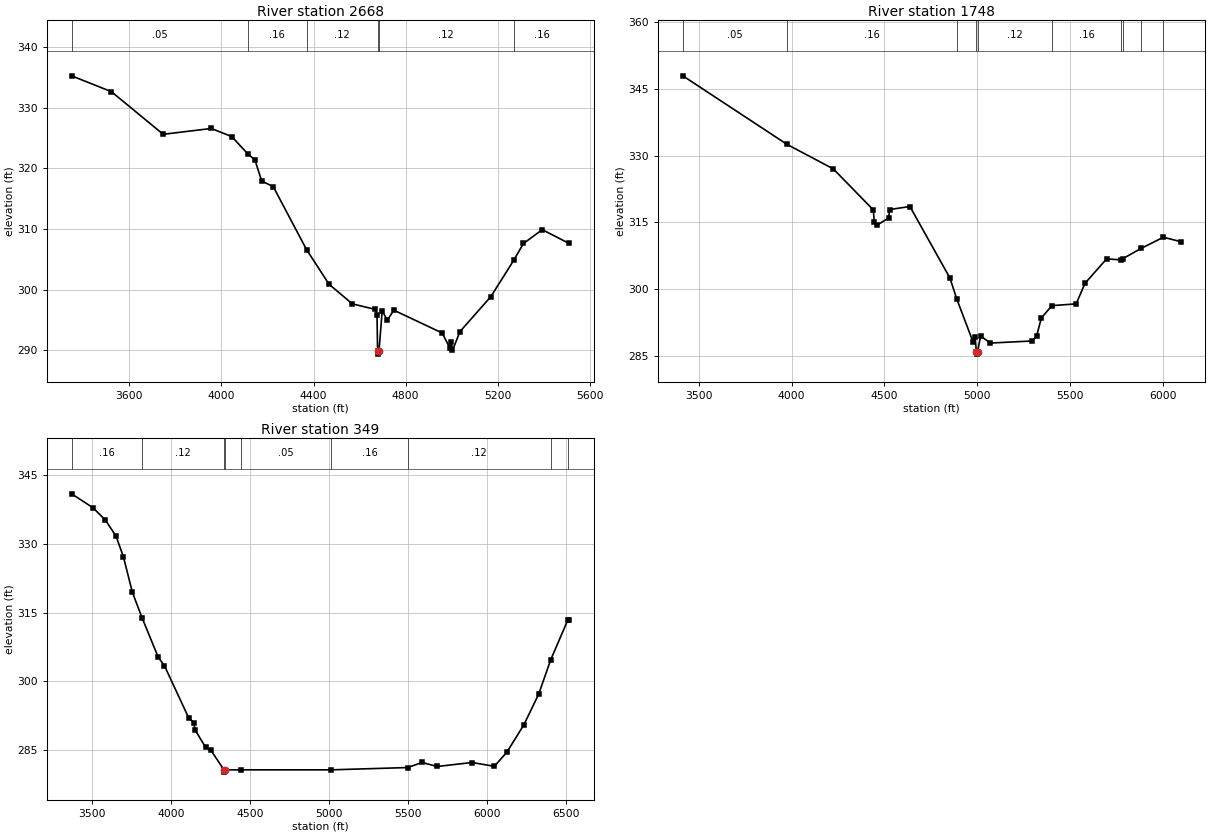
Type RM Length L Ch R = 1,2668,920,920,920
BEGIN DESCRIPTION:
UNT 145 IN UKCR 2.0
END DESCRIPTION:
XS GIS Cut Line= 2
      3665765.01     10561688.93      3667704.81     10560738.55
#Sta/Elev= 30
  3349.8  335.31  3522.5  332.70  3747.5  325.65  3956.2  326.61  4045.5  325.27
  4114.8  322.41  4145.6  321.42  4175.0  317.94  4225.5  316.98  4369.7  306.60
  4467.5  300.87  4568.7  297.63  4668.9  296.71  4675.5  295.84  4678.1  289.83
  4680.9  289.33  4684.1  289.83  4698.0  296.48  4720.5  294.95  4748.6  296.59
  4958.5  292.82  4990.5  290.42  4996.1  291.26  5003.0  289.93  5035.5  293.05
  5170.0  298.85  5268.7  304.82  5311.1  307.61  5392.7  309.89  5509.9  307.61
#Mann=6,-1,0
  3349.8    0.05       0  4114.8    0.16       0  4369.7    0.12       0
  4678.1    0.07       0  4684.1    0.12       0  5268.7    0.16       0
Bank Sta=4678.1,4684.1
Exp/Cntr=0.3,0.1

Type RM Length L Ch R = 1,1748,1399,1399,1399
BEGIN DESCRIPTION:
Mapping XS ab8ab4a0
END DESCRIPTION:
XS GIS Cut Line= 3
      3665504.57     10562144.67      3667327.48     10561688.94
      3667587.65     10560934.45
#Sta/Elev= 30
  3415.4  347.94  3976.2  332.53  4224.6  327.04  4440.0  317.82  4445.1  315.19
  4461.7  314.44  4522.4  316.00  4527.6  317.90  4636.9  318.58  4852.3  302.50
  4888.1  297.90  4976.0  288.20  4987.4  289.19  4994.7  285.92  4997.4  285.42
  5000.7  285.92  5017.2  289.49  5069.8  287.91  5292.9  288.37  5317.9  289.41
  5343.8  293.53  5400.6  296.31  5531.1  296.71  5578.7  301.34  5695.0  306.82
  5772.2  306.59  5780.5  306.83  5880.2  309.16  6000.0  311.68  6092.5  310.70
#Mann=10,-1,0
  3415.4    0.05       0  3976.2    0.16       0  4888.1    0.12       0
  4994.7    0.07       0  5000.7    0.12       0  5400.6    0.16       0
  5772.2    0.12       0  5780.5    0.16       0  5880.2    0.12       0
  6000.0    0.16       0
Bank Sta=4994.7,5000.7
Exp/Cntr=0.3,0.1

Type RM Length L Ch R = 1,349,0,0,0
BEGIN DESCRIPTION:
UNT 145 IN UKCR 1.0
END DESCRIPTION:
XS GIS Cut Line= 4
      3666298.88     10563043.10      3667744.14     10562639.46
      3667965.50     10562274.88      3667587.90     10561116.04
#Sta/Elev= 30
  3372.3  340.94  3508.0  337.90  3586.7  335.19  3653.4  331.70  3699.6  327.25
  3757.2  319.41  3818.0  313.89  3920.2  305.28  3959.5  303.43  4111.7  292.12
  4145.9  290.96  4151.8  289.49  4219.4  285.64  4253.6  284.96  4335.6  280.71
  4338.4  280.21  4341.6  280.71  4440.5  280.71  5014.6  280.71  5497.1  281.21
  5587.9  282.32  5683.0  281.44  5903.8  282.31  6045.2  281.48  6124.7  284.61
  6229.9  290.45  6324.5  297.18  6401.0  304.72  6508.4  313.35  6518.2  313.47
#Mann=9,-1,0
  3372.3    0.16       0  3818.0    0.12       0  4335.6   0.035       0
  4341.6    0.12       0  4440.5    0.05       0  5014.6    0.16       0
  5497.1    0.12       0  6401.0    0.16       0  6508.4    0.12       0
Bank Sta=4335.6,4341.6
Exp/Cntr=0.3,0.1

Chan Stop Cuts=-1