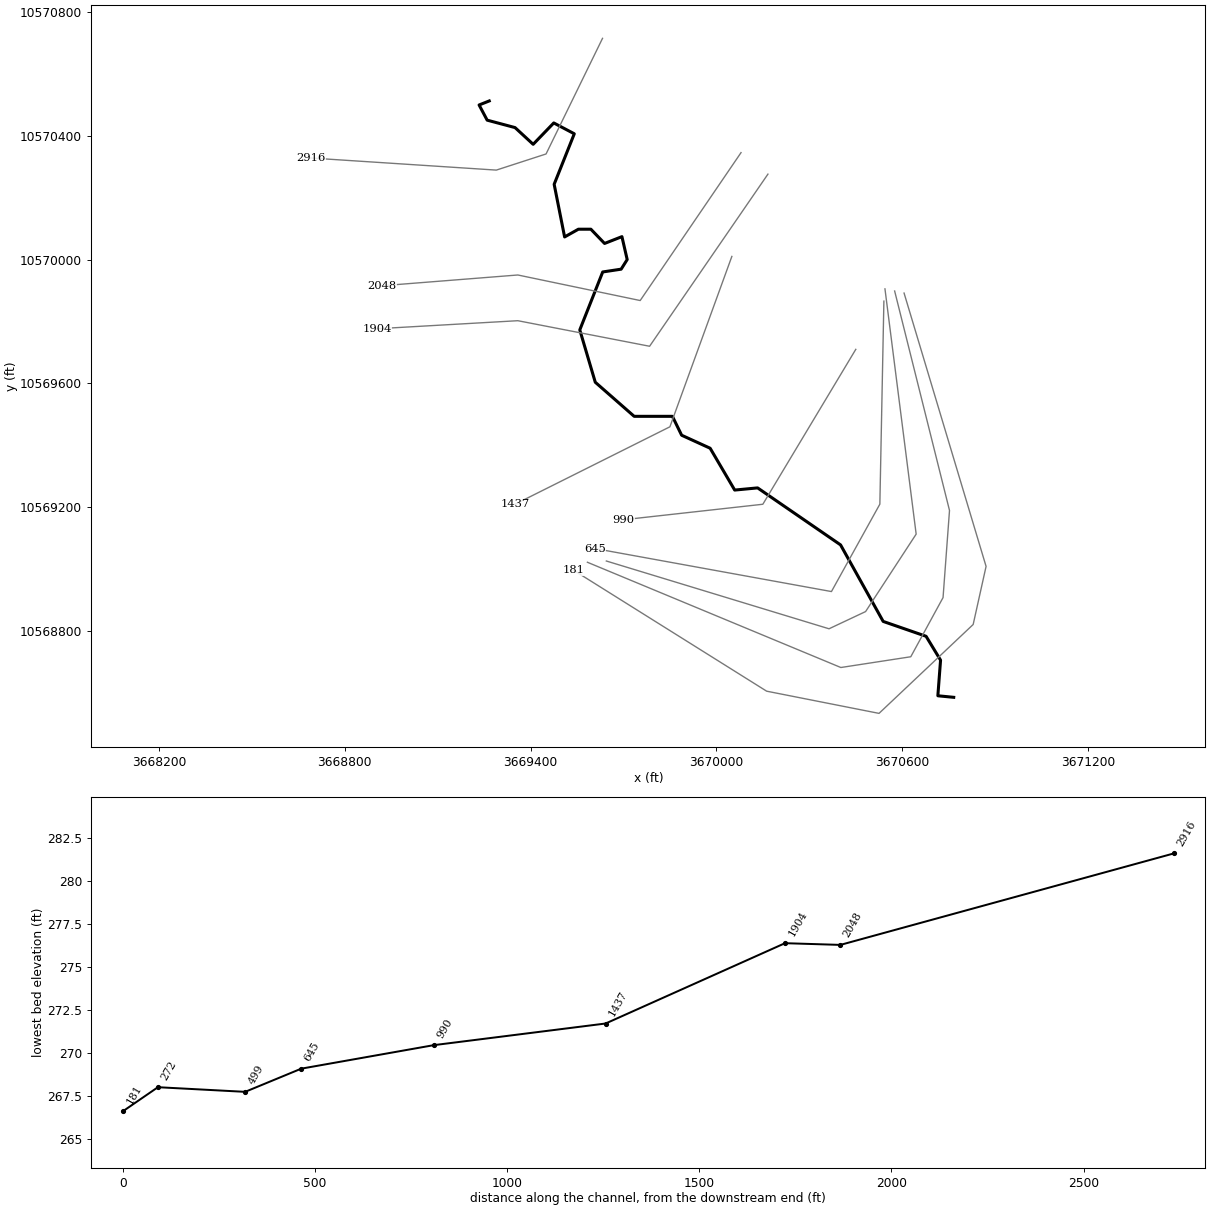
--- UNT 150 IN UKCR.prj (project) ---

Proj Title=UNT 150 IN UKCR Base Level Engineering
Current Plan=p01
Default Exp/Contr=0.3,0.1
English Units
Geom File=g01
Flow File=f01
Plan File=p01
BEGIN DESCRIPTION:
UNT 150 IN UKCR
END DESCRIPTION:

--- UNT 150 IN UKCR.p01 (plan) ---

Plan Title=Multiple Run
Short Identifier=Multiple
Geom File=g01
Flow File=f01
Subcritical Flow
K Sum by GR= 0
Std Step Tol= 0.01
Critical Tol= 0.01
Num of Std Step Trials= 20
Max Error Tol= 0.3
Flow Tol Ratio= 0.001
Split Flow NTrial= 30
Split Flow Tol= 0.02
Split Flow Ratio= 0.02
Log Output Level= 0
Friction Slope Method= 1
Unsteady Friction Slope Method= 2
Unsteady Bridges Friction Slope Method= 1
Parabolic Critical Depth
Global Vel Dist=  1 , 1 , 1
Global Log Level= 0
CheckData=True
Encroach Param= -1, 0, 0, 0
BEGIN DESCRIPTION:
Multiple Run
END DESCRIPTION:

--- UNT 150 IN UKCR.f01 (steady flow) ---

Flow Title=Multiple
Number of Profiles=7
Profile Names=10-year,25-year,50-year,1pct_min,100-year,1pct_plu,500-year
River Rch & RM= UNT 150 IN UKCR,Reach-1,2916
     428     569     684     604     817    1105    1170
Boundary for River Rch & Prof#=UNT 150 IN UKCR,Reach-1,1
Up Type=0
Dn Type=3
Dn Slope=0.005
Boundary for River Rch & Prof#=UNT 150 IN UKCR,Reach-1,2
Up Type=0
Dn Type=3
Dn Slope=0.005
Boundary for River Rch & Prof#=UNT 150 IN UKCR,Reach-1,3
Up Type=0
Dn Type=3
Dn Slope=0.005
Boundary for River Rch & Prof#=UNT 150 IN UKCR,Reach-1,4
Up Type=0
Dn Type=3
Dn Slope=0.005
Boundary for River Rch & Prof#=UNT 150 IN UKCR,Reach-1,5
Up Type=0
Dn Type=3
Dn Slope=0.005
Boundary for River Rch & Prof#=UNT 150 IN UKCR,Reach-1,6
Up Type=0
Dn Type=3
Dn Slope=0.005
Boundary for River Rch & Prof#=UNT 150 IN UKCR,Reach-1,7
Up Type=0
Dn Type=3
Dn Slope=0.005

--- UNT 150 IN UKCR.g01 (geometry) ---

Geom Title=Existing Conditions

River Reach=UNT 150 IN UKCR,Reach-1
Reach XY= 30
      3669266.50     10570512.00      3669233.75     10570499.00
      3669259.75     10570450.00      3669349.75     10570426.00
      3669408.25     10570372.00      3669474.75     10570441.00
      3669541.00     10570406.00      3669476.00     10570243.00
      3669509.75     10570073.00      3669554.25     10570098.00
      3669594.50     10570098.00      3669638.75     10570052.00
      3669694.75     10570074.00      3669711.75     10570000.00
      3669692.25     10569969.00      3669632.75     10569960.00
      3669558.75     10569773.00      3669608.75     10569604.00
      3669734.25     10569494.00      3669857.75     10569494.00
      3669887.50     10569433.00      3669979.50     10569391.00
      3670058.75     10569256.00      3670132.75     10569263.00
      3670400.50     10569079.00      3670538.00     10568832.00
      3670676.50     10568784.00      3670723.25     10568707.00
      3670714.50     10568592.00      3670765.75     10568587.00

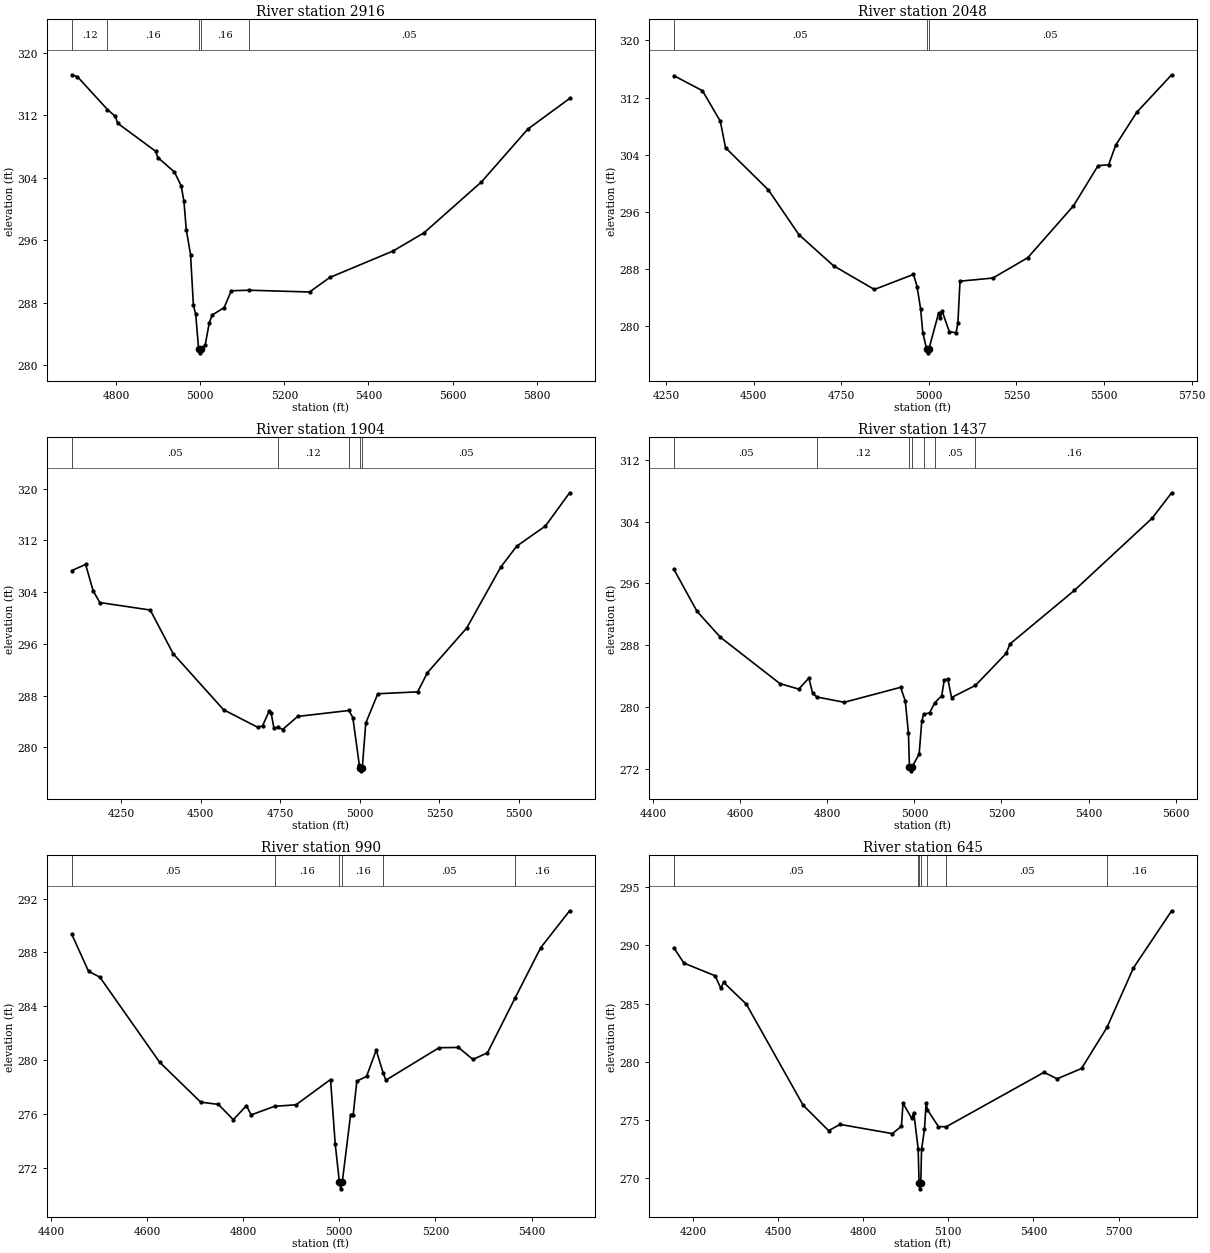
Type RM Length L Ch R = 1,2916,868,868,868
BEGIN DESCRIPTION:
UNT 150 IN UKCR 5.0
END DESCRIPTION:
XS GIS Cut Line= 4
      3669632.15     10570714.09      3669449.87     10570340.85
      3669289.28     10570288.77      3668690.35     10570327.83
#Sta/Elev= 30
  4694.1  317.17  4707.6  316.93  4779.1  312.72  4797.7  311.86  4803.3  310.97
  4893.4  307.40  4899.0  306.59  4938.4  304.73  4954.4  302.97  4961.0  300.99
  4966.5  297.37  4976.7  294.18  4983.5  287.70  4989.0  286.54  4995.9  282.11
  4998.7  281.61  5001.9  282.11  5011.6  282.61  5021.2  285.44  5028.5  286.46
  5056.6  287.39  5073.6  289.55  5115.9  289.62  5259.8  289.39  5308.0  291.25
  5458.4  294.63  5532.1  296.96  5668.8  303.47  5779.0  310.22  5878.5  314.14
#Mann=5,-1,0
  4694.1    0.12       0  4779.1    0.16       0  4995.9    0.07       0
  5001.9    0.16       0  5115.9    0.05       0
Bank Sta=4995.9,5001.9
Exp/Cntr=0.3,0.1

Type RM Length L Ch R = 1,2048,144,144,144
BEGIN DESCRIPTION:
Mapping XS a4256677
END DESCRIPTION:
XS GIS Cut Line= 4
      3670079.21     10570345.18      3669753.69     10569867.76
      3669358.73     10569950.23      3668920.31     10569915.50
#Sta/Elev= 30
  4271.8  315.08  4353.7  312.97  4404.6  308.70  4419.5  304.99  4542.1  299.07
  4628.8  292.83  4727.7  288.47  4844.3  285.15  4956.0  287.26  4966.2  285.56
  4976.4  282.39  4982.7  279.05  4993.8  276.78  4996.6  276.28  4999.8  276.78
  5027.5  281.81  5032.7  281.14  5037.8  282.11  5058.1  279.26  5077.6  279.08
  5082.7  280.44  5088.8  286.31  5182.7  286.75  5282.3  289.60  5412.7  296.86
  5482.9  302.48  5513.0  302.60  5533.1  305.34  5593.3  309.95  5692.9  315.20
#Mann=3,-1,0
  4271.8    0.05       0  4993.8    0.03       0  4999.8    0.05       0
Bank Sta=4993.8,4999.8
Exp/Cntr=0.3,0.1

Type RM Length L Ch R = 1,1904,467,467,467
BEGIN DESCRIPTION:
UNT 150 IN UKCR 4.0
END DESCRIPTION:
XS GIS Cut Line= 4
      3670166.04     10570275.78      3669784.07     10569720.19
      3669358.73     10569802.66      3668903.76     10569776.66
#Sta/Elev= 30
  4095.6  307.34  4139.1  308.29  4162.9  304.20  4183.8  302.40  4342.1  301.24
  4413.8  294.51  4572.2  285.83  4679.7  283.11  4694.6  283.34  4715.6  285.63
  4721.6  285.33  4730.5  282.96  4742.8  283.13  4757.7  282.77  4804.9  284.79
  4965.9  285.71  4978.1  284.62  4998.5  277.28  5001.9  276.88  5004.6  276.38
  5007.9  276.88  5018.8  283.77  5056.6  288.30  5181.8  288.59  5212.2  291.55
  5335.7  298.46  5442.6  307.88  5492.7  311.12  5582.8  314.23  5658.8  319.37
#Mann=5,-1,0
  4095.6    0.05       0  4742.8    0.12       0  4965.9    0.05       0
  5001.9    0.03       0  5007.9    0.05       0
Bank Sta=5001.9,5007.9
Exp/Cntr=0.3,0.1

Type RM Length L Ch R = 1,1437,447,447,447
BEGIN DESCRIPTION:
UNT 150 IN UKCR 3.0
END DESCRIPTION:
XS GIS Cut Line= 3
      3670049.59     10570010.15      3669849.61     10569460.19
      3669349.62     10569210.19
#Sta/Elev= 30
  4446.9  297.86  4500.1  292.40  4553.9  289.03  4690.9  283.01  4734.2  282.30
  4757.4  283.74  4766.1  281.73  4776.3  281.27  4838.6  280.59  4968.2  282.53
  4978.9  280.76  4986.2  276.57  4988.5  272.20  4991.3  271.70  4994.5  272.20
  5010.8  273.88  5016.8  278.13  5021.0  279.03  5034.9  279.23  5046.7  280.52
  5062.8  281.46  5068.4  283.47  5076.8  283.60  5085.2  281.21  5140.2  282.78
  5211.0  286.94  5219.4  288.15  5367.5  295.10  5546.4  304.47  5591.1  307.76
#Mann=7,-1,0
  4446.9    0.05       0  4776.3    0.12       0  4988.5    0.07       0
  4994.5    0.12       0  5021.0    0.16       0  5046.7    0.05       0
  5140.2    0.16       0
Bank Sta=4988.5,4994.5
Exp/Cntr=0.3,0.1

Type RM Length L Ch R = 1,990,345,345,345
BEGIN DESCRIPTION:
UNT 150 IN UKCR 2.0
END DESCRIPTION:
XS GIS Cut Line= 3
      3670449.60     10569710.17      3670149.61     10569210.19
      3669699.65     10569160.19
#Sta/Elev= 30
  4443.3  289.35  4478.3  286.59  4501.6  286.17  4626.0  279.85  4711.5  276.88
  4748.4  276.71  4779.5  275.57  4806.7  276.62  4816.5  275.93  4865.3  276.57
  4909.8  276.68  4981.7  278.56  4991.4  273.79  5000.1  270.94  5002.8  270.44
  5006.1  270.94  5023.5  275.96  5028.9  275.96  5036.4  278.44  5056.6  278.79
  5076.7  280.74  5091.3  279.03  5096.8  278.51  5207.5  280.92  5247.7  280.94
  5277.9  280.05  5308.1  280.54  5365.6  284.61  5418.8  288.34  5479.1  291.09
#Mann=6,-1,0
  4443.3    0.05       0  4865.3    0.16       0  5000.1    0.07       0
  5006.1    0.16       0  5091.3    0.05       0  5365.6    0.16       0
Bank Sta=5000.1,5006.1
Exp/Cntr=0.3,0.1

Type RM Length L Ch R = 1,645,146,146,146
BEGIN DESCRIPTION:
Mapping XS 3c494733
END DESCRIPTION:
XS GIS Cut Line= 4
      3670540.32     10569865.86      3670527.30     10569210.51
      3670371.05     10568928.39      3669607.16     10569067.28
#Sta/Elev= 30
  4132.6  289.81  4168.3  288.48  4278.3  287.39  4298.3  286.32  4308.3  286.82
  4388.3  284.95  4588.4  276.26  4678.4  274.07  4718.4  274.61  4902.8  273.82
  4934.7  274.45  4940.4  276.43  4971.3  275.12  4978.2  275.63  4993.7  272.53
  4997.0  269.57  4999.7  269.07  5003.0  269.57  5005.7  272.46  5016.0  274.19
  5021.7  276.43  5026.6  275.86  5065.2  274.42  5092.7  274.41  5437.3  279.09
  5483.5  278.53  5569.4  279.42  5659.1  282.95  5752.4  288.07  5887.0  292.98
#Mann=7,-1,0
  4132.6    0.05       0  4993.7    0.16       0  4997.0    0.07       0
  5003.0    0.16       0  5026.6    0.12       0  5092.7    0.05       0
  5659.1    0.16       0
Bank Sta=4997,5003
Exp/Cntr=0.3,0.1

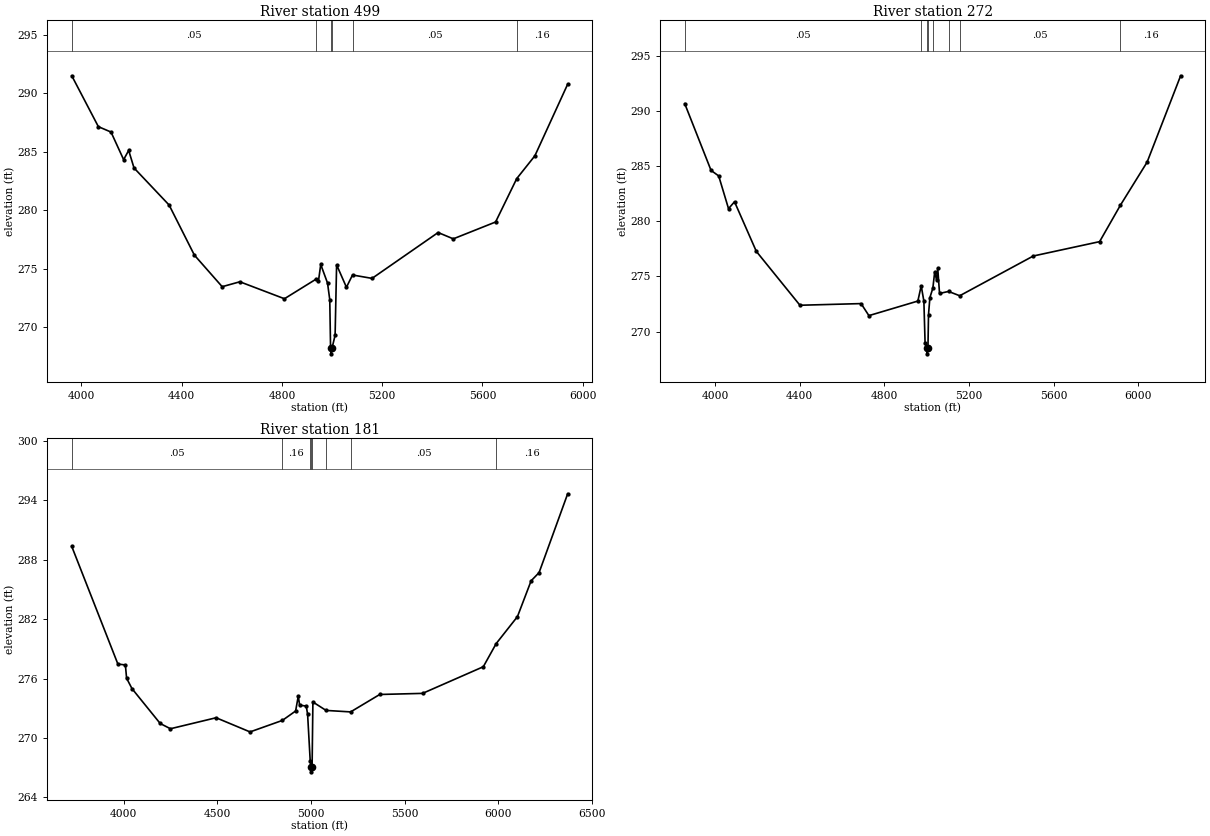
Type RM Length L Ch R = 1,499,227,227,227
BEGIN DESCRIPTION:
Mapping XS 0c2734c4
END DESCRIPTION:
XS GIS Cut Line= 5
      3670543.79     10569905.41      3670644.48     10569113.80
      3670481.28     10568863.80      3670363.23     10568808.24
      3669644.50     10569026.98
#Sta/Elev= 30
  3961.7  291.49  4067.8  287.14  4118.2  286.68  4168.6  284.32  4188.7  285.11
  4210.0  283.61  4350.0  280.44  4450.8  276.16  4561.7  273.46  4632.3  273.88
  4810.1  272.43  4936.6  274.11  4945.8  273.93  4954.9  275.36  4982.0  273.77
  4990.9  272.35  4994.1  268.22  4996.8  267.72  5000.1  268.22  5012.2  269.31
  5018.2  275.33  5057.4  273.41  5081.7  274.46  5159.6  274.17  5423.2  278.09
  5483.7  277.55  5652.4  278.99  5736.8  282.70  5809.2  284.65  5940.0  290.77
#Mann=6,-1,0
  3961.7    0.05       0  4936.6    0.12       0  4994.1    0.07       0
  5000.1    0.12       0  5081.7    0.05       0  5736.8    0.16       0
Bank Sta=4994.1,5000.1
Exp/Cntr=0.3,0.1

Type RM Length L Ch R = 1,272,91,91,91
BEGIN DESCRIPTION:
Mapping XS 9a79aca3
END DESCRIPTION:
XS GIS Cut Line= 6
      3670575.03     10569898.53      3670752.12     10569190.18
      3670731.28     10568908.93      3670627.12     10568717.96
      3670401.42     10568683.24      3669583.31     10569022.97
#Sta/Elev= 30
  3856.2  290.65  3980.7  284.60  4016.8  284.10  4063.2  281.14  4091.6  281.76
  4194.6  277.27  4400.8  272.39  4689.8  272.54  4726.7  271.45  4958.1  272.77
  4974.0  274.15  4986.6  272.76  4992.3  268.95  4999.8  268.49  5002.5  267.99
  5005.8  268.49  5008.5  271.55  5015.0  273.08  5029.0  273.94  5037.8  275.42
  5046.4  274.68  5052.1  275.74  5060.6  273.46  5103.3  273.64  5156.0  273.25
  5503.8  276.85  5817.2  278.15  5915.8  281.46  6041.7  285.35  6200.1  293.17
#Mann=8,-1,0
  3856.2    0.05       0  4974.0    0.16       0  4999.8    0.07       0
  5005.8    0.16       0  5029.0    0.12       0  5103.3    0.16       0
  5156.0    0.05       0  5915.8    0.16       0
Bank Sta=4999.8,5005.8
Exp/Cntr=0.3,0.1

Type RM Length L Ch R = 1,181,0,0,0
BEGIN DESCRIPTION:
UNT 150 IN UKCR 1.0
END DESCRIPTION:
XS GIS Cut Line= 6
      3670605.44     10569891.89      3670870.17     10569009.63
      3670828.51     10568822.13      3670524.61     10568535.19
      3670161.84     10568606.85      3669537.71     10568997.84
#Sta/Elev= 30
  3722.6  289.34  3968.9  277.47  4008.9  277.38  4015.4  276.04  4044.2  274.99
  4194.9  271.47  4249.6  270.94  4493.4  272.05  4674.7  270.62  4847.2  271.78
  4918.1  272.73  4932.3  274.23  4939.6  273.32  4974.8  273.23  4982.1  272.41
  4996.2  267.65  5000.1  267.09  5002.8  266.59  5006.1  267.09  5010.4  273.64
  5080.7  272.79  5211.9  272.64  5367.4  274.40  5596.1  274.51  5920.5  277.20
  5989.4  279.54  6102.9  282.26  6176.0  285.88  6218.4  286.70  6371.1  294.66
#Mann=8,-1,0
  3722.6    0.05       0  4847.2    0.16       0  4996.2    0.12       0
  5000.1    0.07       0  5006.1    0.12       0  5080.7    0.16       0
  5211.9    0.05       0  5989.4    0.16       0
Bank Sta=5000.1,5006.1
Exp/Cntr=0.3,0.1

Chan Stop Cuts=-1