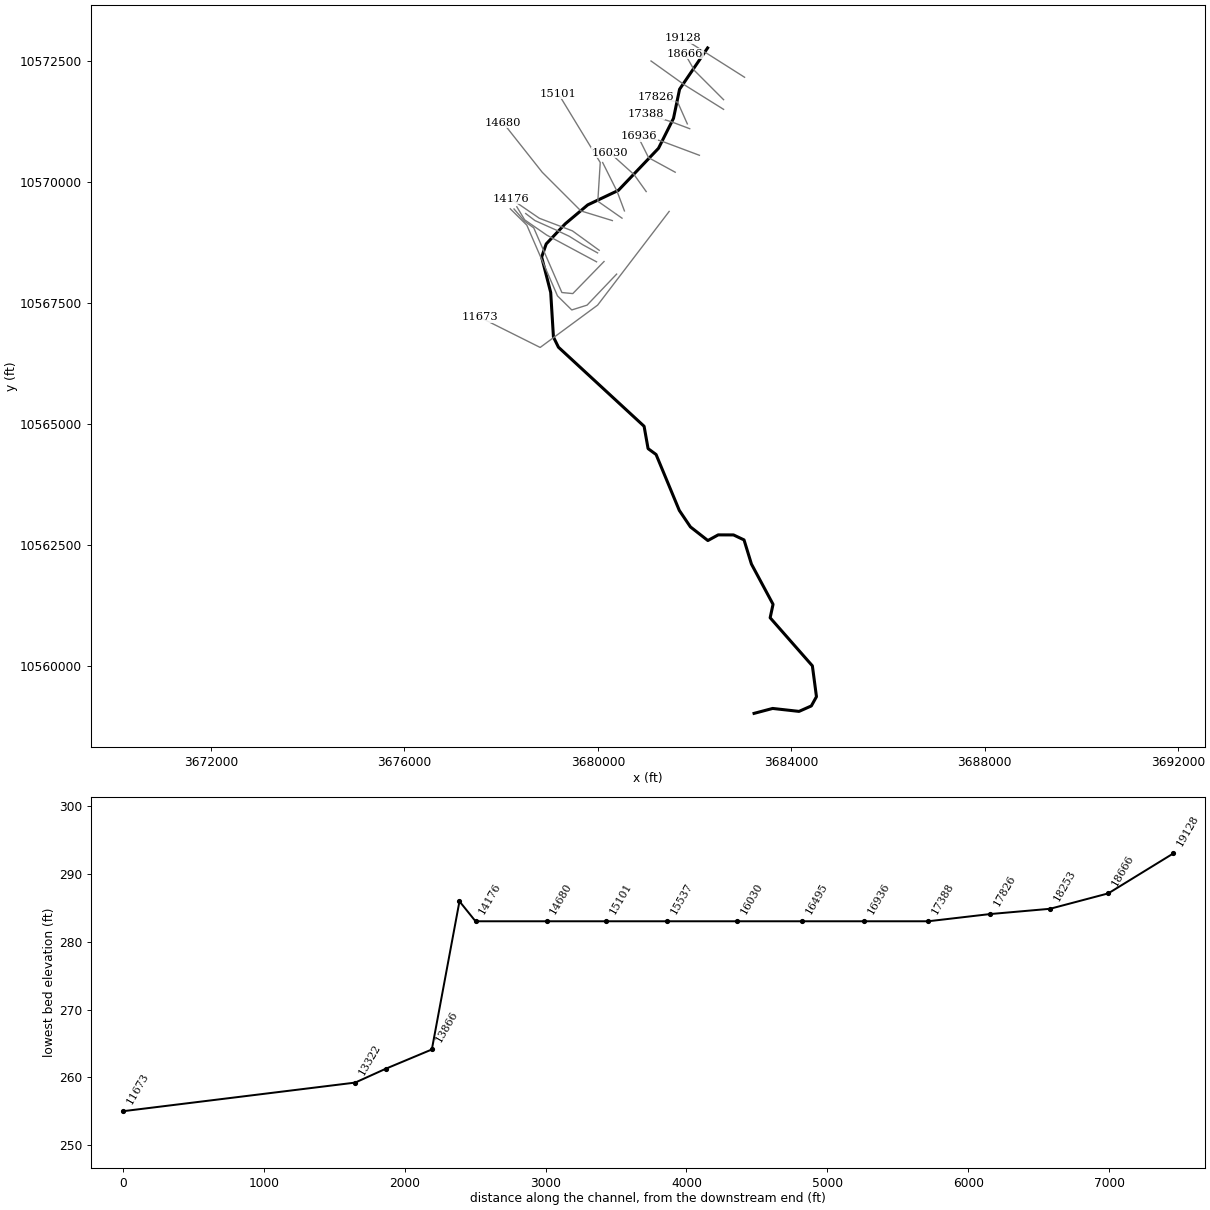
--- UNT 154 IN UKCR.prj (project) ---

Proj Title=UNT 154 IN UKCR Base Level Engineering
Current Plan=p01
Default Exp/Contr=0.3,0.1
English Units
Geom File=g01
Flow File=f01
Plan File=p01
BEGIN DESCRIPTION:
UNT 154 IN UKCR
END DESCRIPTION:

--- UNT 154 IN UKCR.p01 (plan) ---

Plan Title=Multiple Run
Short Identifier=Multiple
Geom File=g01
Flow File=f01
Subcritical Flow
K Sum by GR= 0
Std Step Tol= 0.01
Critical Tol= 0.01
Num of Std Step Trials= 20
Max Error Tol= 0.3
Flow Tol Ratio= 0.001
Split Flow NTrial= 30
Split Flow Tol= 0.02
Split Flow Ratio= 0.02
Log Output Level= 0
Friction Slope Method= 1
Unsteady Friction Slope Method= 2
Unsteady Bridges Friction Slope Method= 1
Parabolic Critical Depth
Global Vel Dist=  1 , 1 , 1
Global Log Level= 0
CheckData=True
Encroach Param= -1, 0, 0, 0
BEGIN DESCRIPTION:
Multiple Run
END DESCRIPTION:

--- UNT 154 IN UKCR.f01 (steady flow) ---

Flow Title=Multiple
Number of Profiles=7
Profile Names=10-year,25-year,50-year,1pct_min,100-year,1pct_plu,500-year
River Rch & RM= UNT 154 IN UKCR,Reach-1,19128
     774    1067    1313    1186    1604    2169    2404
Boundary for River Rch & Prof#=UNT 154 IN UKCR,Reach-1,1
Up Type=0
Dn Type=3
Dn Slope=0.005
Boundary for River Rch & Prof#=UNT 154 IN UKCR,Reach-1,2
Up Type=0
Dn Type=3
Dn Slope=0.005
Boundary for River Rch & Prof#=UNT 154 IN UKCR,Reach-1,3
Up Type=0
Dn Type=3
Dn Slope=0.005
Boundary for River Rch & Prof#=UNT 154 IN UKCR,Reach-1,4
Up Type=0
Dn Type=3
Dn Slope=0.005
Boundary for River Rch & Prof#=UNT 154 IN UKCR,Reach-1,5
Up Type=0
Dn Type=3
Dn Slope=0.005
Boundary for River Rch & Prof#=UNT 154 IN UKCR,Reach-1,6
Up Type=0
Dn Type=3
Dn Slope=0.005
Boundary for River Rch & Prof#=UNT 154 IN UKCR,Reach-1,7
Up Type=0
Dn Type=3
Dn Slope=0.005

--- UNT 154 IN UKCR.g01 (geometry) ---

Geom Title=Existing Conditions

River Reach=UNT 154 IN UKCR,Reach-1
Reach XY= 30
      3682269.50     10572780.00      3681689.75     10571926.00
      3681564.00     10571324.00      3681254.25     10570705.00
      3680424.75     10569835.00      3679791.75     10569535.00
      3679325.00     10569142.00      3678932.50     10568727.00
      3678838.00     10568456.00      3679025.50     10567724.00
      3679082.00     10566803.00      3679185.25     10566592.00
      3680956.25     10564957.00      3681038.50     10564495.00
      3681204.00     10564373.00      3681684.00     10563217.00
      3681914.00     10562876.00      3682274.75     10562594.00
      3682488.00     10562711.00      3682804.75     10562710.00
      3683022.25     10562607.00      3683175.25     10562108.00
      3683622.25     10561275.00      3683562.25     10560997.00
      3684435.25     10560003.00      3684519.75     10559365.00
      3684413.75     10559174.00      3684159.25     10559061.00
      3683614.25     10559122.00      3683229.50     10559020.00

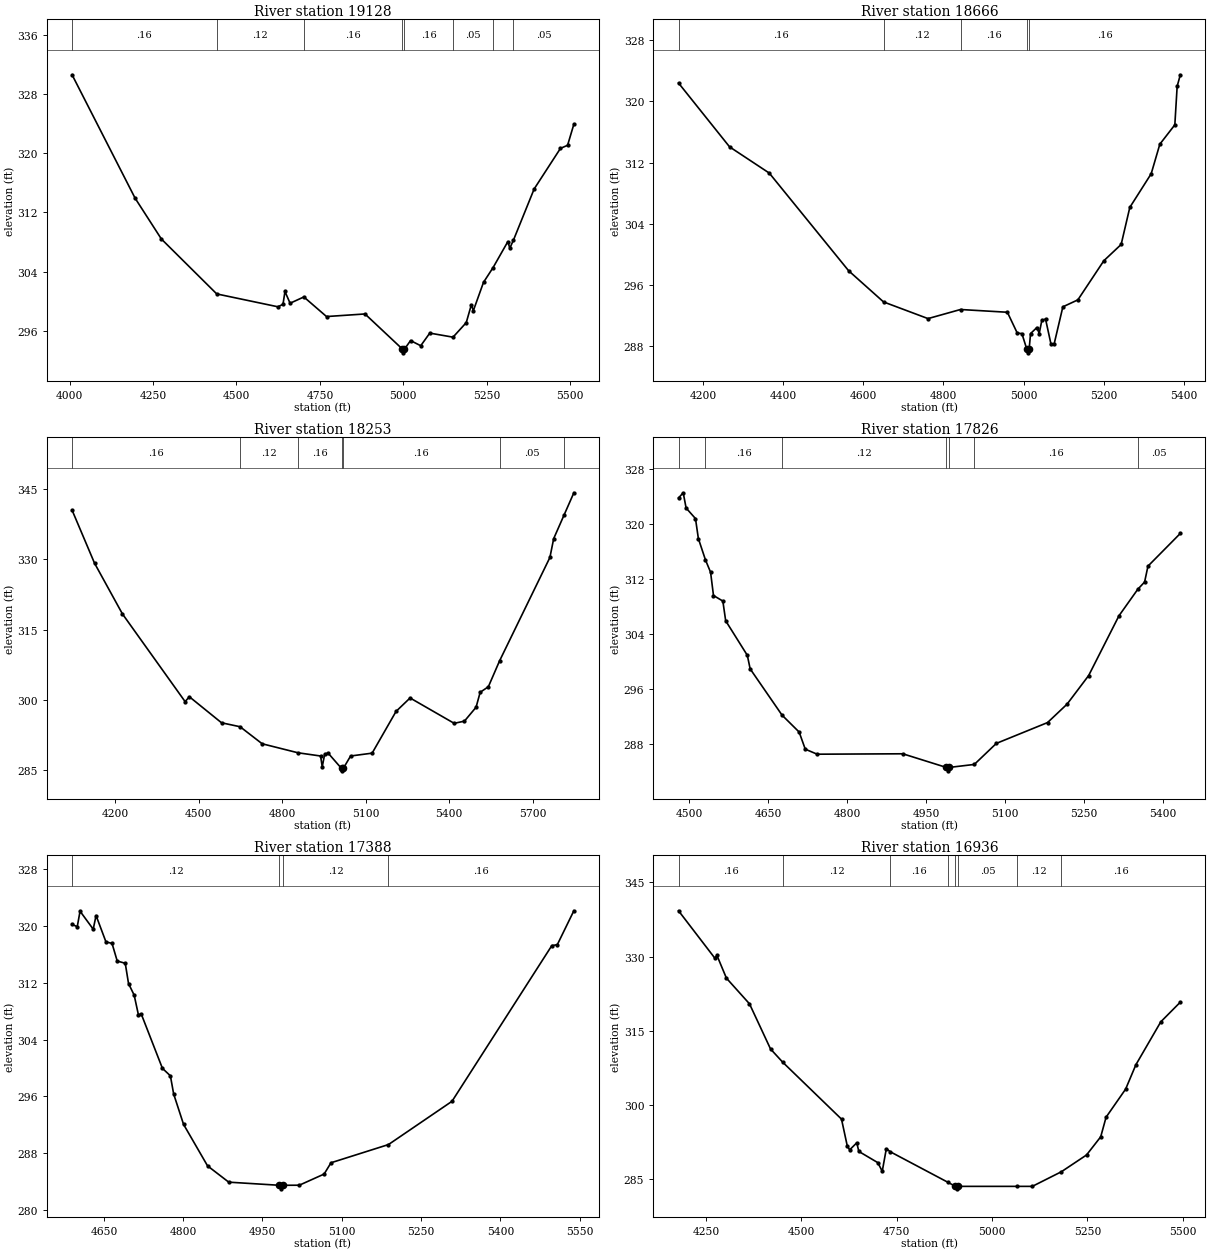
Type RM Length L Ch R = 1,19128,462,462,462
BEGIN DESCRIPTION:
UNT 154 IN UKCR 17.0
END DESCRIPTION:
XS GIS Cut Line= 2
      3683033.56     10572173.73      3681763.69     10572978.68
#Sta/Elev= 30
  4007.4  330.62  4196.2  313.93  4275.0  308.40  4440.9  300.97  4624.2  299.23
  4639.4  299.57  4645.3  301.30  4660.6  299.71  4701.9  300.56  4769.8  297.91
  4885.1  298.26  4997.4  293.50  5000.1  293.00  5003.4  293.50  5021.6  294.66
  5052.1  293.96  5079.2  295.67  5148.8  295.12  5188.5  297.09  5203.8  299.51
  5209.7  298.70  5240.2  302.54  5268.8  304.53  5313.1  308.05  5319.0  307.16
  5329.9  308.25  5391.9  315.17  5470.7  320.66  5492.1  321.08  5510.9  323.93
#Mann=8,-1,0
  4007.4    0.16       0  4440.9    0.12       0  4701.9    0.16       0
  4997.4    0.07       0  5003.4    0.16       0  5148.8    0.05       0
  5268.8    0.16       0  5329.9    0.05       0
Bank Sta=4997.4,5003.4
Exp/Cntr=0.3,0.1

Type RM Length L Ch R = 1,18666,413,413,413
BEGIN DESCRIPTION:
UNT 154 IN UKCR 16.0
END DESCRIPTION:
XS GIS Cut Line= 3
      3682599.64     10571710.16      3681999.61     10572310.19
      3681799.60     10572660.21
#Sta/Elev= 30
  4139.4  322.41  4266.7  314.06  4365.7  310.63  4563.7  297.85  4650.8  293.77
  4761.7  291.59  4842.8  292.78  4959.7  292.42  4984.4  289.69  4995.9  289.63
  5008.0  287.61  5010.8  287.11  5014.0  287.61  5017.5  289.63  5033.3  290.42
  5039.1  289.64  5045.6  291.35  5054.9  291.53  5068.6  288.22  5076.5  288.31
  5098.1  293.13  5135.5  294.04  5200.3  299.16  5243.5  301.29  5265.1  306.14
  5318.4  310.54  5340.0  314.41  5377.4  316.94  5383.2  321.98  5391.1  323.49
#Mann=5,-1,0
  4139.4    0.16       0  4650.8    0.12       0  4842.8    0.16       0
  5008.0    0.07       0  5014.0    0.16       0
Bank Sta=5008,5014
Exp/Cntr=0.3,0.1

Type RM Length L Ch R = 1,18253,427,427,427
BEGIN DESCRIPTION:
UNT 154 IN UKCR 15.0
END DESCRIPTION:
XS GIS Cut Line= 3
      3682599.64     10571510.17      3681799.61     10572010.19
      3681099.58     10572510.21
#Sta/Elev= 30
  4044.7  340.54  4125.5  329.20  4225.7  318.37  4451.0  299.63  4466.3  300.67
  4581.9  295.11  4648.7  294.26  4728.1  290.62  4856.6  288.70  4938.0  288.01
  4943.9  285.70  4952.8  288.41  4965.1  288.63  5013.4  285.34  5016.1  284.84
  5019.4  285.34  5045.9  288.01  5123.3  288.62  5209.3  297.54  5259.7  300.41
  5418.2  294.99  5455.1  295.46  5496.9  298.43  5511.6  301.62  5541.1  302.81
  5581.3  308.33  5762.3  330.43  5775.9  334.46  5813.3  339.51  5848.4  344.25
#Mann=7,-1,0
  4044.7    0.16       0  4648.7    0.12       0  4856.6    0.16       0
  5013.4    0.07       0  5019.4    0.16       0  5581.3    0.05       0
  5813.3    0.16       0
Bank Sta=5013.4,5019.4
Exp/Cntr=0.3,0.1

Type RM Length L Ch R = 1,17826,438,438,438
BEGIN DESCRIPTION:
UNT 154 IN UKCR 14.0
END DESCRIPTION:
XS GIS Cut Line= 3
      3681849.63     10571210.15      3681649.61     10571660.19
      3681199.57     10571760.20
#Sta/Elev= 30
  4479.4  323.75  4488.3  324.50  4493.8  322.28  4511.6  320.75  4517.1  317.84
  4530.5  314.75  4540.3  312.94  4545.8  309.56  4563.6  308.75  4569.0  305.88
  4610.1  300.86  4615.5  298.89  4676.1  292.16  4708.6  289.70  4720.2  287.21
  4742.8  286.48  4905.5  286.54  4988.1  284.56  4990.8  284.06  4994.1  284.56
  5041.4  284.99  5083.3  288.05  5180.6  291.08  5217.7  293.76  5258.7  297.92
  5316.3  306.61  5352.2  310.48  5365.0  311.52  5371.4  313.83  5432.9  318.59
#Mann=7,-1,0
  4479.4    0.12       0  4530.5    0.16       0  4676.1    0.12       0
  4988.1    0.07       0  4994.1    0.12       0  5041.4    0.16       0
  5352.2    0.05       0
Bank Sta=4988.1,4994.1
Exp/Cntr=0.3,0.1

Type RM Length L Ch R = 1,17388,452,452,452
BEGIN DESCRIPTION:
UNT 154 IN UKCR 13.0
END DESCRIPTION:
XS GIS Cut Line= 3
      3681899.61     10571110.19      3681499.61     10571260.19
      3680999.62     10571410.18
#Sta/Elev= 30
  4589.8  320.21  4599.6  319.89  4604.9  322.07  4629.8  319.54  4635.2  321.46
  4653.9  317.75  4665.4  317.54  4675.2  315.06  4690.4  314.74  4696.6  311.89
  4707.3  310.25  4715.3  307.49  4720.6  307.62  4760.7  299.96  4775.8  298.90
  4782.0  296.34  4800.7  292.07  4846.1  286.23  4886.2  283.94  4982.0  283.50
  4984.7  283.00  4988.0  283.50  5019.6  283.51  5066.6  285.08  5079.6  286.67
  5188.3  289.23  5308.5  295.32  5497.3  317.23  5507.7  317.36  5539.0  322.13
#Mann=4,-1,0
  4589.8    0.12       0  4982.0    0.07       0  4988.0    0.12       0
  5188.3    0.16       0
Bank Sta=4982,4988
Exp/Cntr=0.3,0.1

Type RM Length L Ch R = 1,16936,441,441,441
BEGIN DESCRIPTION:
UNT 154 IN UKCR 12.0
END DESCRIPTION:
XS GIS Cut Line= 3
      3682099.62     10570560.18      3681299.61     10570860.19
      3680849.60     10570960.19
#Sta/Elev= 30
  4178.2  339.27  4273.4  329.68  4278.8  330.25  4303.7  325.64  4364.2  320.44
  4419.4  311.30  4451.5  308.61  4605.4  297.11  4620.5  291.69  4626.8  290.89
  4645.5  292.32  4650.8  290.57  4700.6  288.30  4712.2  286.55  4722.9  291.12
  4733.6  290.49  4884.7  284.31  4904.1  283.50  4906.9  283.00  4910.1  283.50
  5066.5  283.50  5105.6  283.50  5181.8  286.46  5247.7  289.85  5284.9  293.53
  5299.0  297.50  5350.2  303.18  5377.1  308.11  5442.4  316.80  5493.6  320.78
#Mann=8,-1,0
  4178.2    0.16       0  4451.5    0.12       0  4733.6    0.16       0
  4884.7    0.05       0  4904.1   0.033       0  4910.1    0.05       0
  5066.5    0.12       0  5181.8    0.16       0
Bank Sta=4904.1,4910.1
Exp/Cntr=0.3,0.1

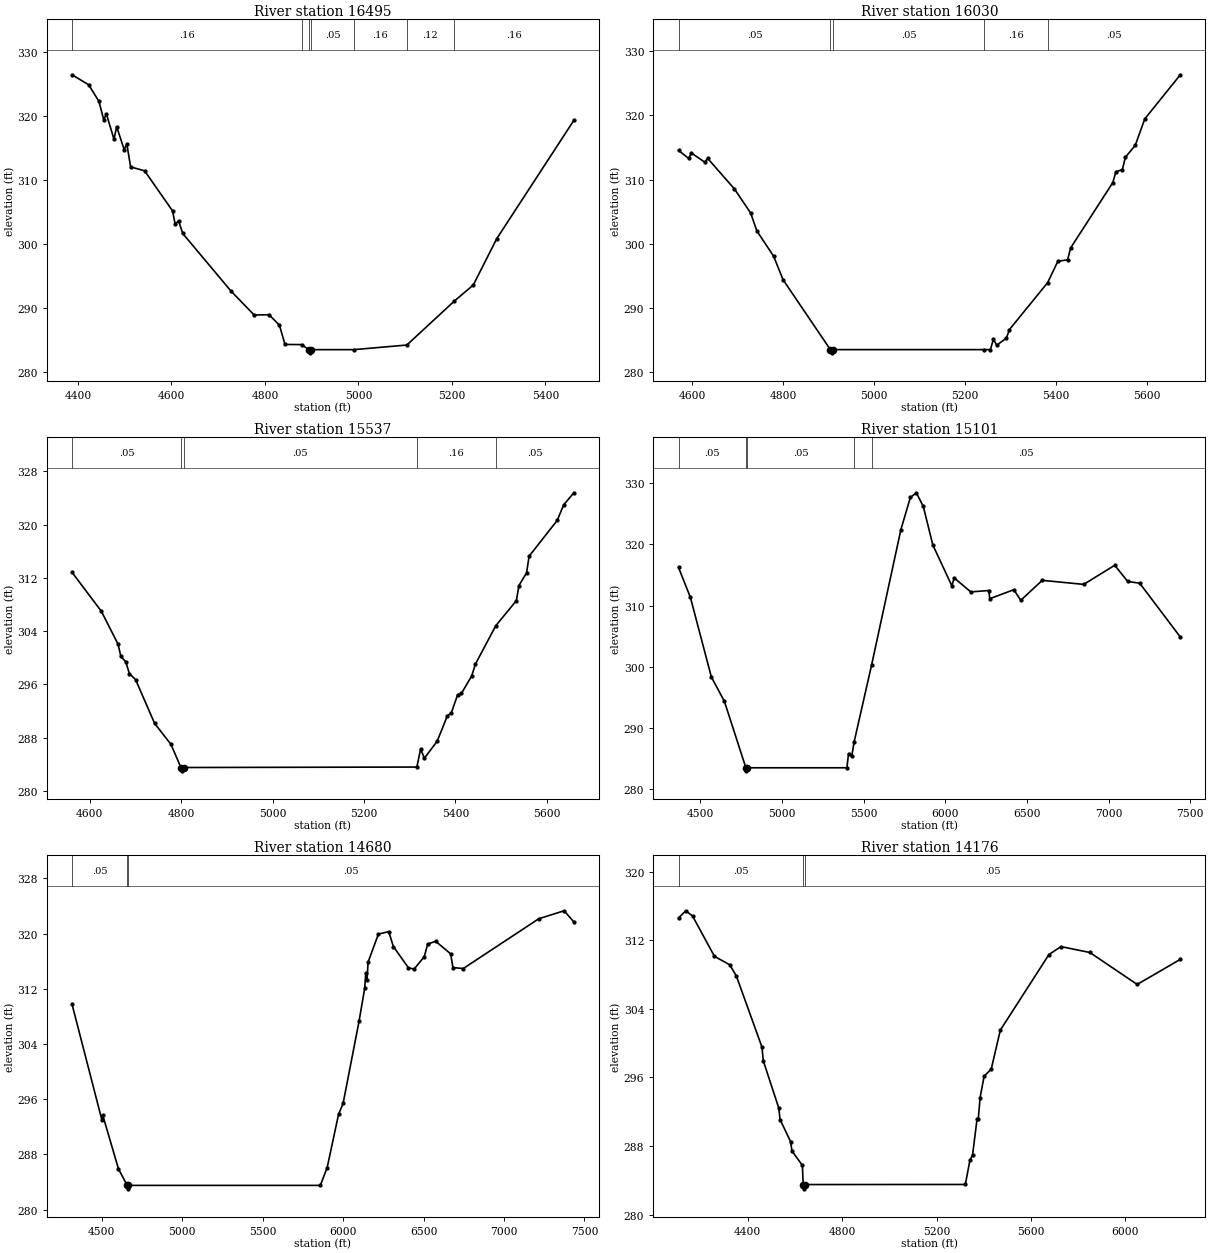
Type RM Length L Ch R = 1,16495,465,465,465
BEGIN DESCRIPTION:
UNT 154 IN UKCR 11.0
END DESCRIPTION:
XS GIS Cut Line= 3
      3681599.58     10570210.21      3681049.61     10570510.19
      3680849.60     10570910.21
#Sta/Elev= 30
  4387.3  326.49  4422.9  324.92  4444.7  322.34  4455.1  319.45  4460.8  320.36
  4477.0  316.40  4482.7  318.38  4498.8  314.79  4504.5  315.65  4512.6  312.08
  4542.5  311.47  4602.3  305.20  4608.0  303.08  4615.1  303.66  4624.1  301.67
  4727.6  292.64  4776.9  288.92  4808.7  288.96  4831.0  287.33  4842.9  284.31
  4878.8  284.29  4893.5  283.50  4896.3  283.00  4899.5  283.50  4990.2  283.50
  5103.6  284.22  5204.4  291.04  5245.8  293.61  5296.1  300.87  5461.0  319.36
#Mann=7,-1,0
  4387.3    0.16       0  4878.8    0.05       0  4893.5    0.07       0
  4899.5    0.05       0  4990.2    0.16       0  5103.6    0.12       0
  5204.4    0.16       0
Bank Sta=4893.5,4899.5
Exp/Cntr=0.3,0.1

Type RM Length L Ch R = 1,16030,493,493,493
BEGIN DESCRIPTION:
UNT 154 IN UKCR 10.0
END DESCRIPTION:
XS GIS Cut Line= 3
      3680999.61     10569810.19      3680749.61     10570160.19
      3680249.61     10570610.19
#Sta/Elev= 30
  4570.0  314.55  4592.1  313.29  4598.3  314.13  4627.8  312.70  4633.9  313.30
  4692.9  308.53  4728.5  304.78  4742.1  302.00  4778.9  298.06  4799.8  294.38
  4903.7  283.50  4906.5  283.00  4909.7  283.50  5241.6  283.50  5255.4  283.50
  5262.1  285.14  5269.2  284.17  5290.5  285.30  5297.2  286.62  5381.2  293.94
  5403.7  297.27  5425.0  297.49  5431.8  299.35  5524.4  309.52  5531.2  311.20
  5545.4  311.55  5552.1  313.47  5573.8  315.34  5594.7  319.45  5672.8  326.32
#Mann=5,-1,0
  4570.0    0.05       0  4903.7   0.033       0  4909.7    0.05       0
  5241.6    0.16       0  5381.2    0.05       0
Bank Sta=4903.7,4909.7
Exp/Cntr=0.3,0.1

Type RM Length L Ch R = 1,15537,436,436,436
BEGIN DESCRIPTION:
UNT 154 IN UKCR 9.0
END DESCRIPTION:
XS GIS Cut Line= 3
      3680549.62     10569410.15      3680399.61     10569810.19
      3680099.59     10570410.22
#Sta/Elev= 30
  4561.1  312.83  4625.2  306.98  4661.7  302.04  4667.9  300.20  4678.6  299.38
  4686.6  297.60  4700.0  296.72  4741.8  290.12  4777.4  286.99  4799.3  283.50
  4802.1  283.00  4805.3  283.50  5315.6  283.57  5323.8  286.27  5332.1  284.90
  5360.1  287.45  5382.5  291.29  5390.8  291.66  5404.8  294.43  5413.2  294.64
  5435.6  297.26  5443.9  299.06  5488.3  304.81  5533.4  308.58  5539.0  310.85
  5555.7  312.75  5561.3  315.26  5622.8  320.64  5636.8  322.96  5659.2  324.79
#Mann=5,-1,0
  4561.1    0.05       0  4799.3   0.033       0  4805.3    0.05       0
  5315.6    0.16       0  5488.3    0.05       0
Bank Sta=4799.3,4805.3
Exp/Cntr=0.3,0.1

Type RM Length L Ch R = 1,15101,421,421,421
BEGIN DESCRIPTION:
UNT 154 IN UKCR 8.0
END DESCRIPTION:
XS GIS Cut Line= 4
      3680499.60     10569260.19      3679999.61     10569610.19
      3680049.61     10570410.19      3679186.41     10571829.42
#Sta/Elev= 30
  4365.6  316.21  4438.4  311.32  4566.6  298.33  4646.3  294.36  4778.0  283.50
  4780.8  283.00  4784.0  283.50  5396.7  283.50  5406.8  285.83  5426.8  285.45
  5440.3  287.65  5547.7  300.26  5727.4  322.40  5785.2  327.64  5822.0  328.41
  5864.7  326.17  5922.8  319.89  6039.0  313.24  6054.5  314.49  6155.3  312.22
  6265.7  312.45  6271.6  311.11  6418.8  312.58  6461.4  310.85  6593.1  314.11
  6847.0  313.45  7036.8  316.57  7116.3  313.93  7189.9  313.64  7438.6  304.85
#Mann=5,-1,0
  4365.6    0.05       0  4778.0   0.033       0  4784.0    0.05       0
  5440.3    0.16       0  5547.7    0.05       0
Bank Sta=4778,4784
Exp/Cntr=0.3,0.1

Type RM Length L Ch R = 1,14680,504,504,504
BEGIN DESCRIPTION:
UNT 154 IN UKCR 7.0
END DESCRIPTION:
XS GIS Cut Line= 4
      3680299.60     10569210.19      3679649.61     10569410.19
      3678849.61     10570210.19      3678039.21     10571235.32
#Sta/Elev= 30
  4316.0  309.73  4501.0  293.01  4506.3  293.70  4604.4  285.89  4658.3  283.50
  4661.0  283.00  4664.3  283.50  5858.7  283.50  5901.2  286.07  5971.9  293.79
  6000.2  295.38  6099.1  307.26  6134.7  312.11  6141.0  314.30  6149.1  313.26
  6155.5  315.86  6219.6  319.92  6283.7  320.28  6312.6  318.12  6405.6  315.06
  6440.8  314.83  6504.9  316.66  6525.7  318.47  6575.4  318.88  6668.4  317.06
  6682.8  315.07  6747.0  314.93  7216.6  322.15  7373.7  323.30  7434.2  321.68
#Mann=3,-1,0
  4316.0    0.05       0  4658.3   0.033       0  4664.3    0.05       0
Bank Sta=4658.3,4664.3
Exp/Cntr=0.3,0.1

Type RM Length L Ch R = 1,14176,114,114,114
BEGIN DESCRIPTION:
UNT 154 IN UKCR 6.0
END DESCRIPTION:
XS GIS Cut Line= 4
      3680027.87     10568595.96      3679474.50     10568997.43
      3678790.91     10569257.84      3678204.94     10569659.34
#Sta/Elev= 30
  4107.0  314.62  4137.7  315.46  4166.6  314.84  4259.1  310.14  4324.1  309.15
  4351.9  307.85  4460.1  299.57  4466.3  297.92  4531.2  292.47  4537.4  291.07
  4581.5  288.52  4587.7  287.41  4631.8  285.73  4634.9  283.50  4637.7  283.00
  4640.9  283.50  5321.8  283.51  5341.2  286.33  5352.4  286.94  5371.3  291.11
  5376.7  291.19  5384.5  293.66  5401.4  296.15  5431.5  296.98  5470.1  301.53
  5676.0  310.35  5726.8  311.28  5849.3  310.59  6049.7  306.86  6232.5  309.79
#Mann=3,-1,0
  4107.0    0.05       0  4634.9   0.033       0  4640.9    0.05       0
Bank Sta=4634.9,4640.9
Exp/Cntr=0.3,0.1

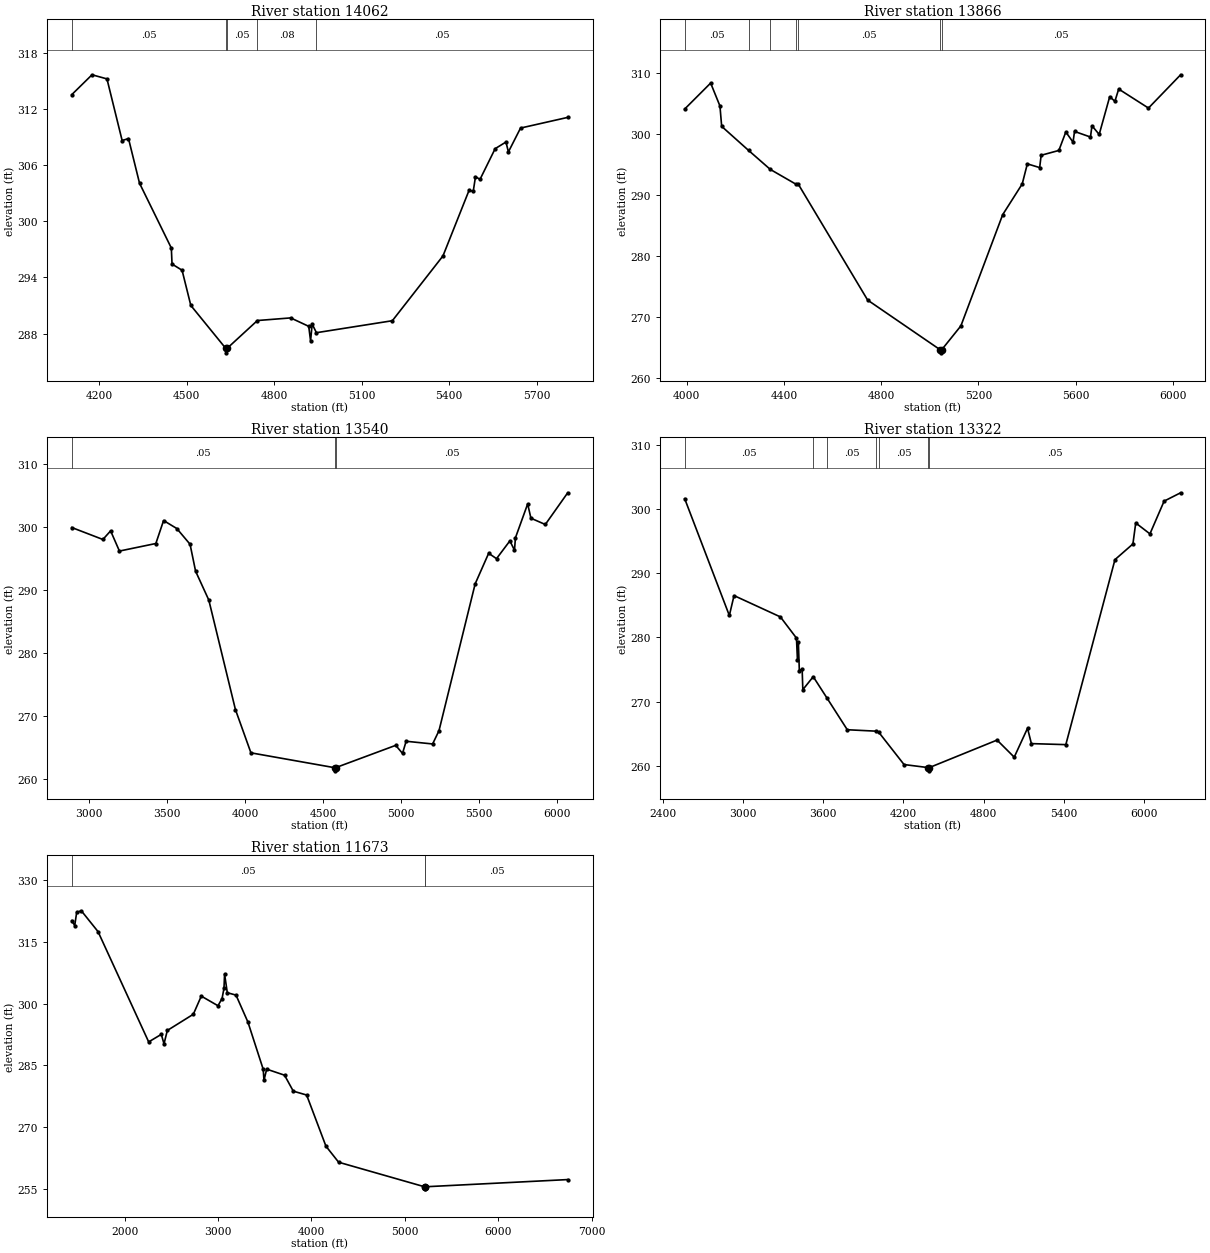
Type RM Length L Ch R = 1,14062,196,196,196
BEGIN DESCRIPTION:
UNT 154 IN UKCR 5.0
END DESCRIPTION:
XS GIS Cut Line= 6
      3679995.30     10568541.72      3679693.87     10568707.50
      3679408.57     10568885.71      3679127.28     10569019.13
      3678699.49     10569210.57      3678508.96     10569355.37
#Sta/Elev= 30
  4106.8  313.51  4176.2  315.63  4227.4  315.19  4279.4  308.61  4301.2  308.82
  4339.0  304.05  4448.0  297.13  4450.4  295.42  4484.8  294.76  4514.8  291.00
  4633.9  286.44  4636.6  285.94  4639.9  286.44  4743.0  289.39  4857.0  289.67
  4918.9  288.77  4925.2  287.22  4930.7  289.01  4945.2  288.09  5205.5  289.37
  5379.0  296.29  5468.5  303.30  5482.7  303.18  5490.4  304.75  5505.9  304.46
  5557.8  307.74  5594.9  308.45  5603.2  307.39  5644.8  309.94  5806.5  311.08
#Mann=5,-1,0
  4106.8    0.05       0  4633.9    0.03       0  4639.9    0.05       0
  4743.0    0.08       0  4945.2    0.05       0
Bank Sta=4633.9,4639.9
Exp/Cntr=0.3,0.1

Type RM Length L Ch R = 1,13866,326,326,326
BEGIN DESCRIPTION:
UNT 154 IN UKCR 4.0
END DESCRIPTION:
XS GIS Cut Line= 4
      3679973.60     10568357.25      3678942.82     10568910.62
      3678487.09     10569225.29      3678324.89     10569495.63
#Sta/Elev= 30
  3992.0  304.09  4098.8  308.35  4137.0  304.59  4144.1  301.25  4254.6  297.31
  4344.0  294.19  4448.0  291.80  4458.6  291.80  4744.3  272.76  5042.6  264.61
  5045.3  264.11  5048.6  264.61  5127.6  268.53  5299.5  286.77  5379.8  291.81
  5400.8  295.10  5451.5  294.49  5457.6  296.51  5530.4  297.30  5559.0  300.33
  5588.7  298.66  5594.8  300.42  5660.4  299.50  5666.5  301.35  5696.2  299.93
  5739.5  306.12  5760.8  305.36  5776.4  307.37  5898.8  304.25  6031.0  309.71
#Mann=7,-1,0
  3992.0    0.05       0  4254.6    0.08       0  4344.0    0.05       0
  4448.0    0.08       0  4458.6    0.05       0  5042.6    0.03       0
  5048.6    0.05       0
Bank Sta=5042.6,5048.6
Exp/Cntr=0.3,0.1

Type RM Length L Ch R = 1,13540,218,218,218
BEGIN DESCRIPTION:
Mapping XS 69dcf94d
END DESCRIPTION:
XS GIS Cut Line= 6
      3680128.08     10568363.64      3679482.44     10567700.64
      3679256.74     10567722.34      3678675.14     10569059.15
      3678484.17     10569198.03      3678267.17     10569449.75
#Sta/Elev= 30
  2889.6  299.94  3089.0  298.04  3138.5  299.41  3195.0  296.20  3428.4  297.40
  3478.0  301.05  3562.8  299.78  3647.7  297.28  3683.0  293.01  3767.9  288.41
  3938.4  271.02  4037.8  264.14  4574.2  261.78  4577.0  261.28  4580.2  261.78
  4965.7  265.33  5009.3  264.05  5032.5  265.98  5202.3  265.55  5243.1  267.66
  5474.9  290.99  5561.5  295.85  5611.7  294.99  5697.5  297.82  5726.9  296.33
  5733.1  298.31  5811.4  303.69  5832.3  301.42  5924.5  300.42  6068.1  305.46
#Mann=3,-1,0
  2889.6    0.05       0  4574.2    0.03       0  4580.2    0.05       0
Bank Sta=4574.2,4580.2
Exp/Cntr=0.3,0.1

Type RM Length L Ch R = 1,13322,1649,1649,1649
BEGIN DESCRIPTION:
Mapping XS f3ec0af0
END DESCRIPTION:
XS GIS Cut Line= 6
      3680388.47     10568103.20      3679777.58     10567461.92
      3679460.73     10567362.10      3679165.60     10567652.90
      3678531.92     10569115.57      3678189.03     10569454.12
#Sta/Elev= 30
  2565.2  301.61  2899.1  283.42  2934.3  286.52  3280.9  283.20  3401.1  279.90
  3408.3  276.51  3415.2  279.22  3422.5  274.82  3443.5  275.07  3448.6  271.87
  3526.4  273.89  3628.8  270.58  3781.0  265.63  3994.5  265.41  4016.7  265.23
  4205.3  260.21  4387.6  259.73  4390.4  259.23  4393.6  259.73  4900.9  264.02
  5029.2  261.36  5128.6  265.86  5157.5  263.47  5415.0  263.31  5782.4  292.12
  5916.6  294.56  5937.7  297.83  6043.9  296.13  6149.9  301.23  6273.3  302.53
#Mann=7,-1,0
  2565.2    0.05       0  3526.4    0.08       0  3628.8    0.05       0
  3994.5    0.08       0  4016.7    0.05       0  4387.6    0.03       0
  4393.6    0.05       0
Bank Sta=4387.6,4393.6
Exp/Cntr=0.3,0.1

Type RM Length L Ch R = 1,11673,0,0,0
BEGIN DESCRIPTION:
UNT 154 IN UKCR 3.0
END DESCRIPTION:
XS GIS Cut Line= 4
      3681474.52     10569399.36      3679995.34     10567461.84
      3678807.84     10566586.84      3677557.85     10567211.83
#Sta/Elev= 30
  1433.7  320.20  1465.3  319.01  1486.1  322.19  1536.0  322.59  1714.7  317.53
  2257.1  290.72  2392.2  292.55  2421.3  290.25  2456.7  293.50  2735.1  297.44
  2820.4  301.85  2999.1  299.51  3042.6  301.24  3063.5  303.74  3069.8  307.22
  3098.8  302.68  3192.3  302.09  3319.8  295.54  3483.4  284.07  3491.6  281.38
  3520.6  284.10  3711.9  282.63  3805.4  278.75  3948.4  277.81  4155.1  265.38
  4290.8  261.48  5211.0  255.51  5213.8  255.01  5217.0  255.51  6743.9  257.26
#Mann=3,-1,0
  1433.7    0.05       0  5211.0    0.03       0  5217.0    0.05       0
Bank Sta=5211,5217
Exp/Cntr=0.3,0.1

Chan Stop Cuts=-1