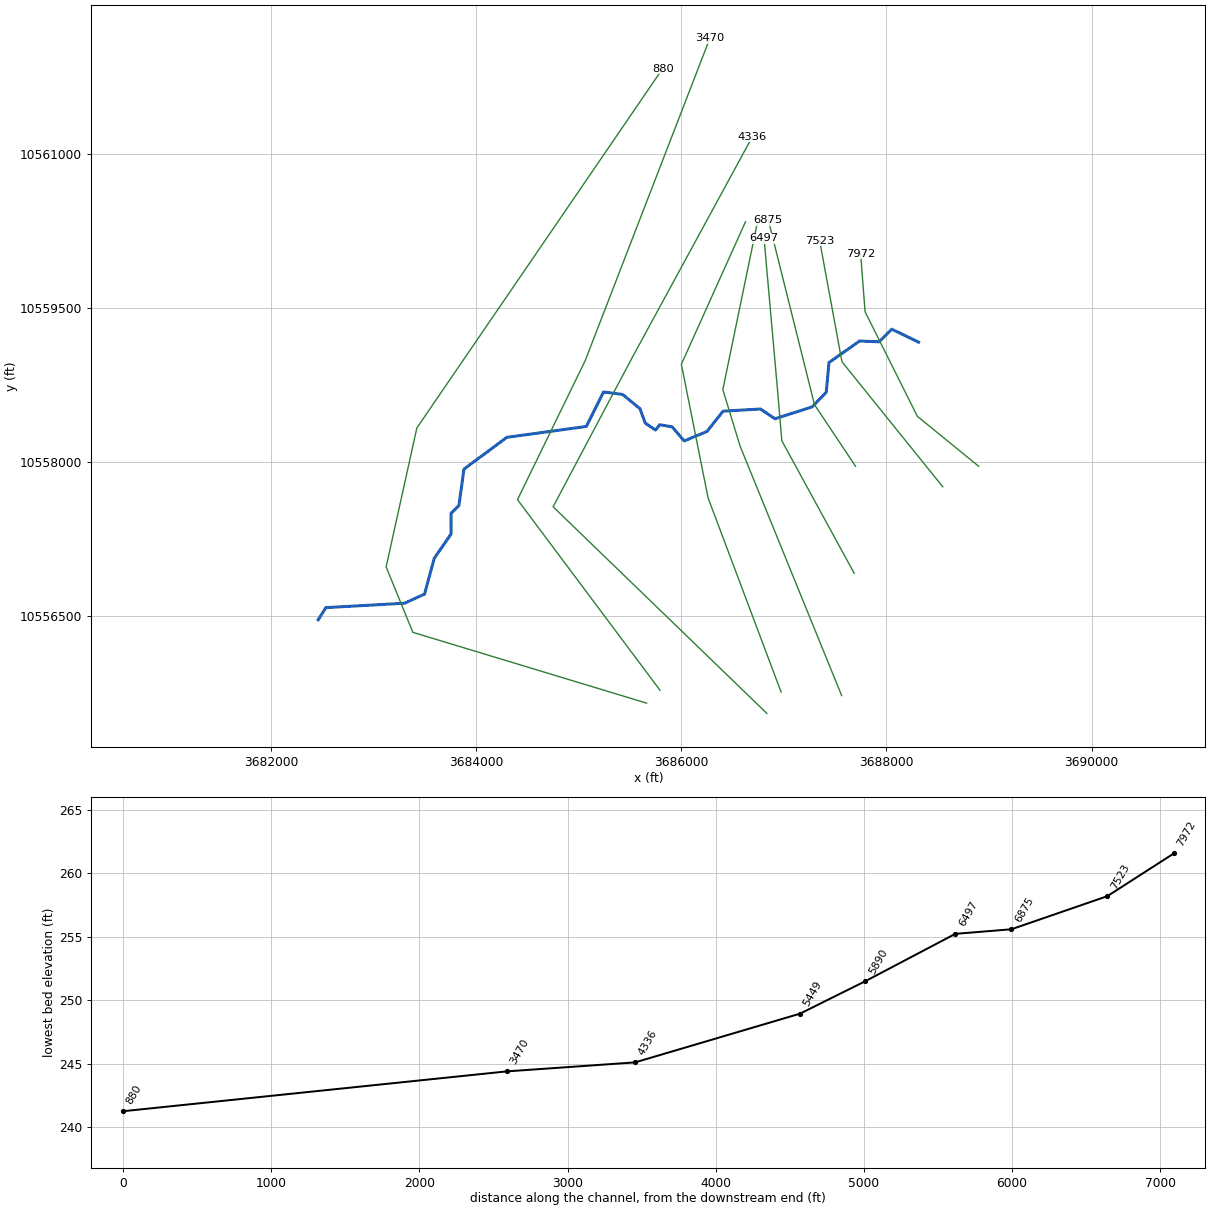
--- UNT 158 IN UKCR.prj (project) ---

Proj Title=UNT 158 IN UKCR Base Level Engineering
Current Plan=p01
Default Exp/Contr=0.3,0.1
English Units
Geom File=g01
Flow File=f01
Plan File=p01
BEGIN DESCRIPTION:
UNT 158 IN UKCR
END DESCRIPTION:

--- UNT 158 IN UKCR.p01 (plan) ---

Plan Title=Multiple Run
Short Identifier=Multiple
Geom File=g01
Flow File=f01
Subcritical Flow
K Sum by GR= 0
Std Step Tol= 0.01
Critical Tol= 0.01
Num of Std Step Trials= 20
Max Error Tol= 0.3
Flow Tol Ratio= 0.001
Split Flow NTrial= 30
Split Flow Tol= 0.02
Split Flow Ratio= 0.02
Log Output Level= 0
Friction Slope Method= 1
Unsteady Friction Slope Method= 2
Unsteady Bridges Friction Slope Method= 1
Parabolic Critical Depth
Global Vel Dist=  1 , 1 , 1
Global Log Level= 0
CheckData=True
Encroach Param= -1, 0, 0, 0
BEGIN DESCRIPTION:
Multiple Run
END DESCRIPTION:

--- UNT 158 IN UKCR.f01 (steady flow) ---

Flow Title=Multiple
Number of Profiles=7
Profile Names=10-year,25-year,50-year,1pct_min,100-year,1pct_plu,500-year
River Rch & RM= UNT 158 IN UKCR,Reach-1,7972
     678     933    1146    1035    1399    1892    2094
Boundary for River Rch & Prof#=UNT 158 IN UKCR,Reach-1,1
Up Type=0
Dn Type=3
Dn Slope=0.005
Boundary for River Rch & Prof#=UNT 158 IN UKCR,Reach-1,2
Up Type=0
Dn Type=3
Dn Slope=0.005
Boundary for River Rch & Prof#=UNT 158 IN UKCR,Reach-1,3
Up Type=0
Dn Type=3
Dn Slope=0.005
Boundary for River Rch & Prof#=UNT 158 IN UKCR,Reach-1,4
Up Type=0
Dn Type=3
Dn Slope=0.005
Boundary for River Rch & Prof#=UNT 158 IN UKCR,Reach-1,5
Up Type=0
Dn Type=3
Dn Slope=0.005
Boundary for River Rch & Prof#=UNT 158 IN UKCR,Reach-1,6
Up Type=0
Dn Type=3
Dn Slope=0.005
Boundary for River Rch & Prof#=UNT 158 IN UKCR,Reach-1,7
Up Type=0
Dn Type=3
Dn Slope=0.005

--- UNT 158 IN UKCR.g01 (geometry) ---

Geom Title=Existing Conditions

River Reach=UNT 158 IN UKCR,Reach-1
Reach XY= 30
      3688314.25     10559170.00      3688052.75     10559296.00
      3687928.75     10559173.00      3687739.50     10559181.00
      3687440.75     10558971.00      3687414.25     10558681.00
      3687275.75     10558538.00      3686914.00     10558423.00
      3686773.25     10558518.00      3686408.50     10558497.00
      3686251.75     10558299.00      3686029.25     10558207.00
      3685912.25     10558344.00      3685791.25     10558365.00
      3685749.75     10558313.00      3685649.50     10558381.00
      3685598.75     10558521.00      3685429.50     10558660.00
      3685243.75     10558684.00      3685076.00     10558348.00
      3684301.50     10558242.00      3683882.75     10557932.00
      3683833.75     10557578.00      3683756.75     10557501.00
      3683756.75     10557299.00      3683593.25     10557063.00
      3683498.50     10556714.00      3683304.25     10556625.00
      3682536.75     10556582.00      3682462.00     10556463.00

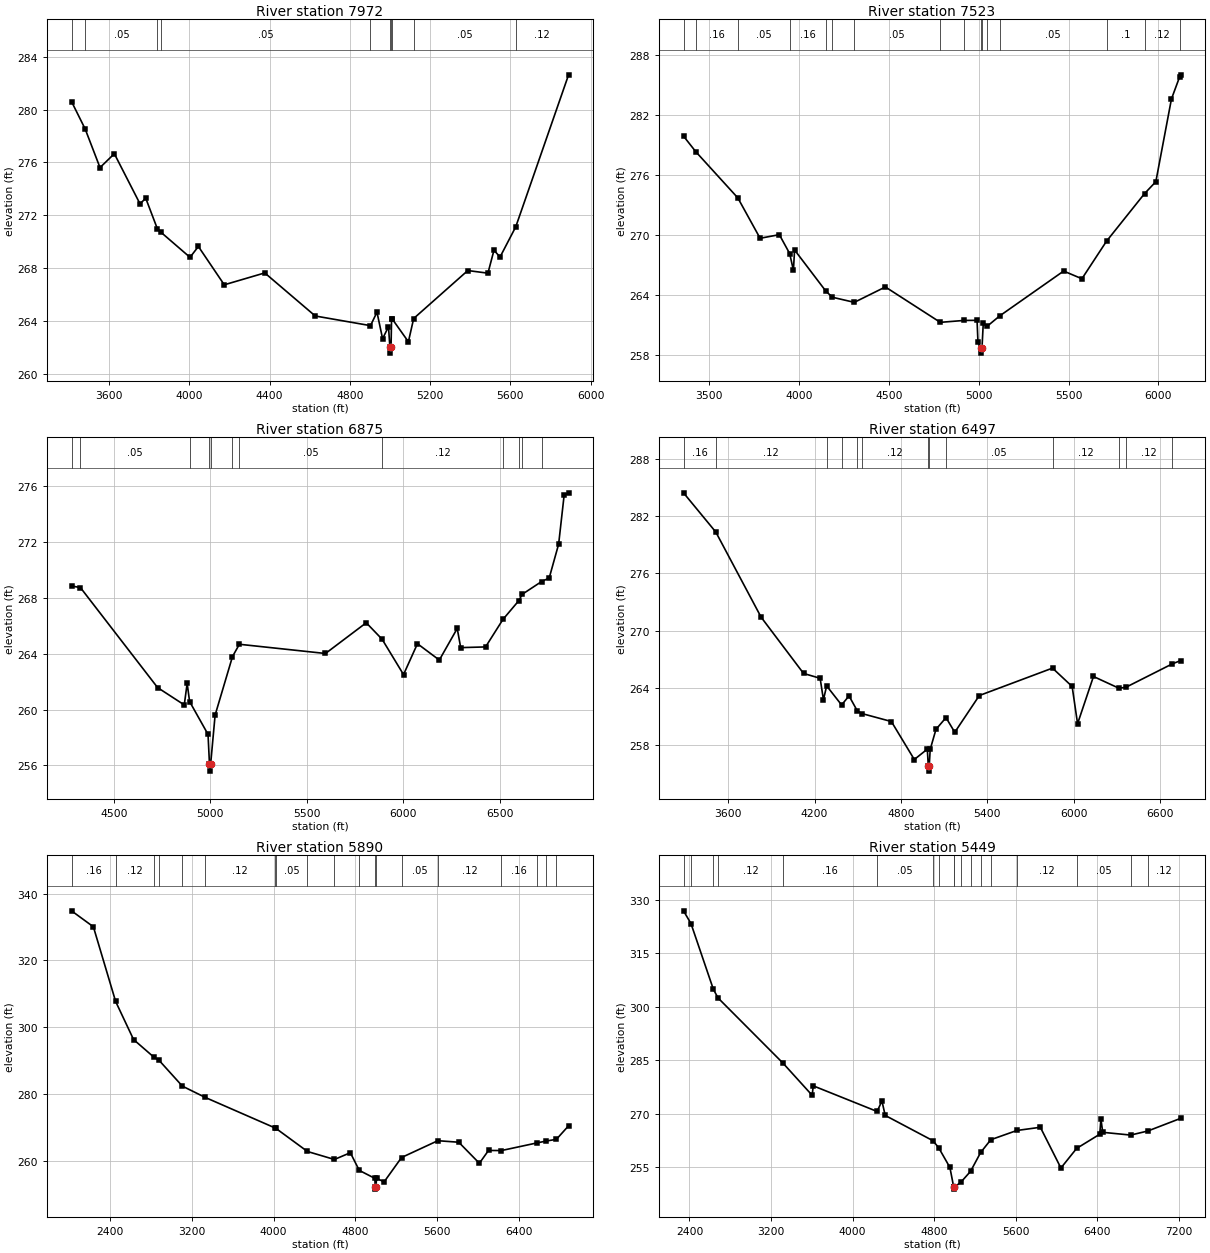
Type RM Length L Ch R = 1,7972,449,449,449
BEGIN DESCRIPTION:
UNT 158 IN UKCR 7.0
END DESCRIPTION:
XS GIS Cut Line= 4
      3688899.60     10557960.20      3688302.67     10558446.47
      3687792.68     10559466.44      3687749.28     10560030.69
#Sta/Elev= 30
  3413.5  280.61  3481.8  278.52  3555.4  275.61  3626.8  276.66  3754.6  272.87
  3783.3  273.29  3841.4  270.97  3859.5  270.71  4003.8  268.82  4045.5  269.64
  4174.5  266.74  4376.2  267.64  4627.8  264.38  4902.9  263.65  4935.2  264.67
  4963.2  262.66  4992.6  263.57  4999.3  262.07  5002.0  261.57  5005.3  262.07
  5007.9  264.17  5010.4  264.17  5091.7  262.43  5118.0  264.19  5387.7  267.82
  5488.0  267.62  5518.1  269.36  5548.2  268.84  5626.6  271.13  5889.7  282.63
#Mann=10,-1,0
  3413.5    0.12       0  3481.8    0.05       0  3841.4    0.16       0
  3859.5    0.05       0  4902.9    0.16       0  4999.3    0.07       0
  5005.3    0.16       0  5010.4    0.12       0  5118.0    0.05       0
  5626.6    0.12       0
Bank Sta=4999.3,5005.3
Exp/Cntr=0.3,0.1

Type RM Length L Ch R = 1,7523,648,648,648
BEGIN DESCRIPTION:
UNT 158 IN UKCR 6.0
END DESCRIPTION:
XS GIS Cut Line= 3
      3688549.64     10557760.16      3687567.24     10558978.62
      3687349.61     10560160.18
#Sta/Elev= 30
  3356.3  279.91  3425.1  278.34  3658.6  273.73  3782.6  269.69  3889.7  270.05
  3947.3  268.16  3968.1  266.48  3974.5  268.52  4148.2  264.41  4184.9  263.79
  4307.0  263.28  4479.9  264.82  4785.6  261.28  4918.0  261.47  4990.2  261.48
  4995.3  259.28  5011.6  258.70  5014.3  258.20  5017.6  258.70  5024.7  261.17
  5045.3  260.87  5116.7  261.93  5472.1  266.41  5573.8  265.64  5710.9  269.40
  5922.5  274.16  5985.3  275.35  6072.1  283.62  6118.2  285.86  6122.9  286.04
#Mann=16,-1,0
  3356.3    0.12       0  3425.1    0.16       0  3658.6    0.05       0
  3947.3    0.16       0  4148.2    0.12       0  4184.9    0.16       0
  4307.0    0.05       0  4785.6    0.16       0  4918.0    0.12       0
  5011.6    0.07       0  5017.6    0.12       0  5045.3    0.16       0
  5116.7    0.05       0  5710.9     0.1       0  5922.5    0.12       0
  6118.2    0.05       0
Bank Sta=5011.6,5017.6
Exp/Cntr=0.3,0.1

Type RM Length L Ch R = 1,6875,378,378,378
BEGIN DESCRIPTION:
UNT 158 IN UKCR 5.0
END DESCRIPTION:
XS GIS Cut Line= 3
      3687699.62     10557960.17      3687299.61     10558560.19
      3686849.62     10560360.16
#Sta/Elev= 30
  4280.2  268.84  4326.2  268.73  4726.4  261.57  4864.6  260.33  4879.6  261.87
  4892.3  260.57  4987.8  258.22  4995.3  256.09  4998.1  255.59  5001.3  256.09
  5024.5  259.60  5114.6  263.79  5150.3  264.67  5596.6  264.01  5807.9  266.21
  5890.1  265.03  6001.2  262.50  6073.3  264.71  6186.7  263.54  6279.5  265.80
  6297.5  264.43  6426.4  264.48  6516.6  266.45  6598.0  267.78  6616.7  268.25
  6716.9  269.16  6756.2  269.41  6805.2  271.84  6833.5  275.32  6856.7  275.51
#Mann=12,-1,0
  4280.2    0.12       0  4326.2    0.05       0  4892.3    0.12       0
  4995.3    0.07       0  5001.3    0.12       0  5114.6    0.16       0
  5150.3    0.05       0  5890.1    0.12       0  6516.6    0.05       0
  6598.0    0.12       0  6616.7    0.16       0  6716.9    0.05       0
Bank Sta=4995.3,5001.3
Exp/Cntr=0.3,0.1

Type RM Length L Ch R = 1,6497,607,607,607
BEGIN DESCRIPTION:
UNT 158 IN UKCR 4.0
END DESCRIPTION:
XS GIS Cut Line= 4
      3687686.60     10556916.99      3686981.30     10558208.22
      3686937.90     10558718.20      3686807.70     10560183.01
#Sta/Elev= 30
  3289.3  284.46  3513.8  280.34  3828.5  271.40  4123.5  265.49  4238.7  264.98
  4261.5  262.73  4284.0  264.18  4387.7  262.18  4439.4  263.13  4497.2  261.55
  4527.9  261.28  4733.6  260.44  4893.0  256.45  4983.4  257.54  4990.4  255.73
  4993.2  255.23  4996.4  255.73  5003.4  257.51  5043.6  259.62  5113.2  260.85
  5174.1  259.31  5344.7  263.17  5853.2  266.05  5989.7  264.12  6027.4  260.21
  6137.8  265.17  6314.4  263.94  6362.2  264.03  6683.4  266.48  6743.0  266.84
#Mann=13,-1,0
  3289.3    0.16       0  3513.8    0.12       0  4284.0    0.16       0
  4387.7    0.12       0  4497.2    0.16       0  4527.9    0.12       0
  4990.4    0.07       0  4996.4    0.12       0  5113.2    0.05       0
  5853.2    0.12       0  6314.4    0.16       0  6362.2    0.12       0
  6683.4    0.16       0
Bank Sta=4990.4,4996.4
Exp/Cntr=0.3,0.1

Type RM Length L Ch R = 1,5890,441,441,441
BEGIN DESCRIPTION:
UNT 158 IN UKCR 3.0
END DESCRIPTION:
XS GIS Cut Line= 4
      3687564.35     10555724.86      3686574.76     10558155.41
      3686406.22     10558707.35      3686742.59     10560334.97
#Sta/Elev= 30
  2023.5  334.83  2237.4  330.05  2455.1  307.69  2630.6  296.29  2827.6  291.06
  2879.6  290.08  3108.1  282.34  3333.1  278.94  4017.3  269.79  4019.4  269.78
  4332.0  262.77  4595.7  260.38  4751.6  262.40  4839.0  257.11  4991.7  254.72
  4994.8  252.00  4997.6  251.50  5000.8  252.00  5008.3  254.76  5081.5  253.65
  5252.9  260.97  5607.7  266.00  5812.4  265.54  6014.1  259.24  6103.6  263.08
  6229.8  263.05  6573.4  265.31  6666.6  265.89  6767.6  266.41  6886.9  270.46
#Mann=19,-1,0
  2023.5    0.16       0  2455.1    0.12       0  2827.6    0.16       0
  2879.6    0.12       0  3108.1    0.16       0  3333.1    0.12       0
  4017.3    0.16       0  4019.4    0.05       0  4332.0    0.16       0
  4595.7    0.05       0  4839.0    0.12       0  4994.8    0.07       0
  5000.8    0.12       0  5252.9    0.05       0  5607.7    0.12       0
  6229.8    0.16       0  6573.4    0.12       0  6666.6    0.16       0
  6767.6    0.05       0
Bank Sta=4994.8,5000.8
Exp/Cntr=0.3,0.1

Type RM Length L Ch R = 1,5449,1113,1113,1113
BEGIN DESCRIPTION:
UNT 158 IN UKCR 2.0
END DESCRIPTION:
XS GIS Cut Line= 4
      3686974.08     10555759.55      3686262.26     10557651.94
      3686001.85     10558954.02      3686626.83     10560342.88
#Sta/Elev= 30
  2341.7  326.83  2415.3  323.24  2634.0  304.90  2680.1  302.45  3317.7  284.18
  3603.1  275.19  3613.4  277.85  4239.4  270.68  4286.9  273.61  4318.9  269.57
  4787.2  262.49  4842.8  260.54  4953.2  255.01  4991.0  249.44  4993.8  248.94
  4997.0  249.44  5064.6  251.00  5155.7  253.92  5254.9  259.21  5354.2  262.77
  5609.0  265.35  5839.8  266.25  6041.4  254.85  6195.4  260.33  6421.9  264.30
  6433.8  268.54  6451.4  264.84  6725.3  264.07  6893.8  265.21  7214.4  268.74
#Mann=18,-1,0
  2341.7    0.16       0  2415.3    0.12       0  2634.0    0.16       0
  2680.1    0.12       0  3317.7    0.16       0  4239.4    0.05       0
  4787.2    0.16       0  4842.8    0.12       0  4991.0    0.07       0
  4997.0    0.12       0  5064.6    0.16       0  5155.7    0.12       0
  5254.9    0.16       0  5354.2    0.05       0  5609.0    0.12       0
  6195.4    0.05       0  6725.3    0.16       0  6893.8    0.12       0
Bank Sta=4991,4997
Exp/Cntr=0.3,0.1

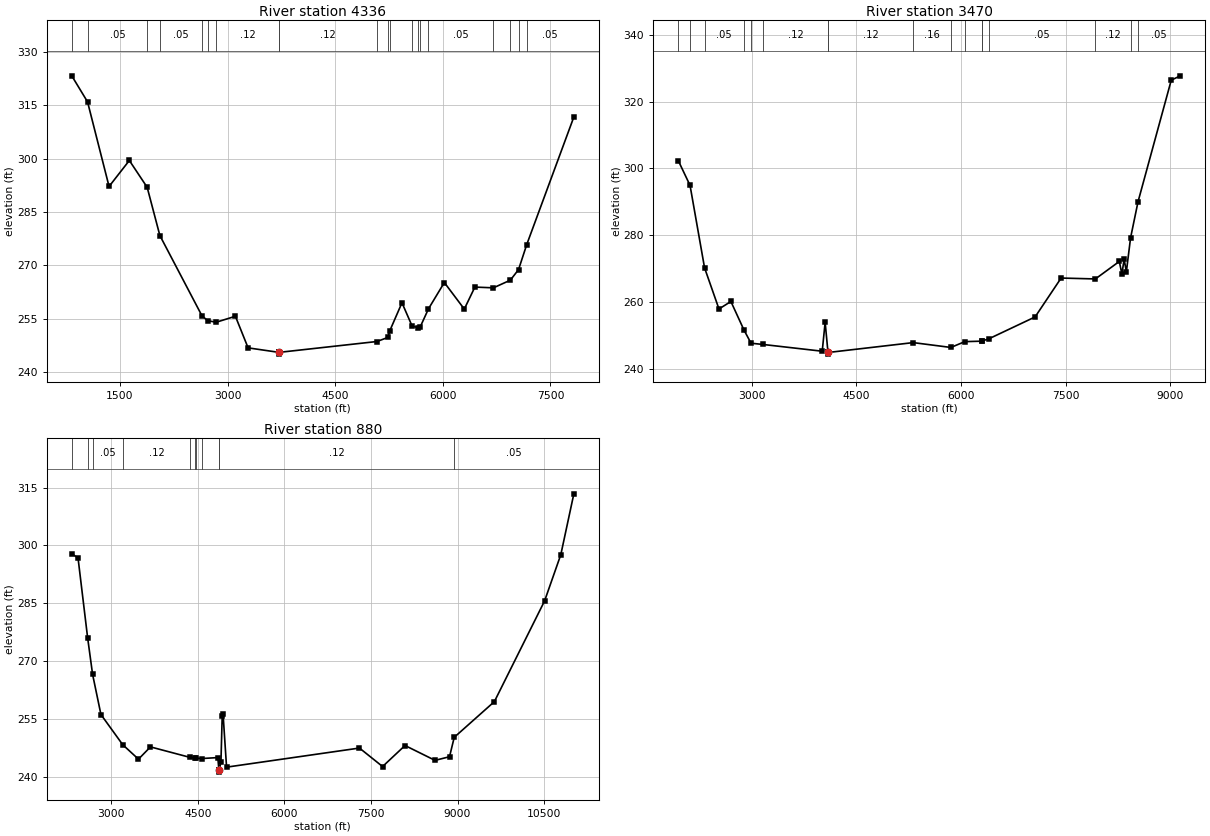
Type RM Length L Ch R = 1,4336,866,866,866
BEGIN DESCRIPTION:
Mapping XS 05df46a1
END DESCRIPTION:
XS GIS Cut Line= 4
      3686835.20     10555551.23      3684751.85     10557565.14
      3685515.74     10559006.11      3686695.19     10561174.21
#Sta/Elev= 30
   829.8  323.22  1049.8  315.91  1349.4  292.16  1632.1  299.46  1880.5  291.93
  2057.5  278.39  2642.8  255.91  2723.2  254.48  2843.4  254.06  3110.2  255.73
  3286.9  246.86  3715.3  245.60  3718.1  245.10  3721.3  245.60  5081.9  248.64
  5236.9  249.80  5257.9  251.48  5431.3  259.52  5572.8  252.97  5658.8  252.52
  5686.9  252.79  5801.0  257.83  6021.6  265.20  6299.9  257.74  6447.2  263.92
  6705.4  263.71  6941.7  265.86  7055.8  268.83  7169.9  275.85  7826.5  311.67
#Mann=20,-1,0
   829.8    0.05       0  1049.8    0.05       0  1880.5    0.16       0
  2057.5    0.05       0  2642.8    0.12       0  2723.2    0.16       0
  2843.4    0.12       0  3715.3    0.07       0  3721.3    0.12       0
  5081.9    0.16       0  5236.9    0.12       0  5257.9    0.16       0
  5572.8    0.05       0  5658.8    0.12       0  5686.9    0.16       0
  5801.0    0.05       0  6705.4    0.12       0  6941.7    0.05       0
  7055.8    0.07       0  7169.9    0.05       0
Bank Sta=3715.3,3721.3
Exp/Cntr=0.3,0.1

Type RM Length L Ch R = 1,3470,2590,2590,2590
BEGIN DESCRIPTION:
Mapping XS c93b895a
END DESCRIPTION:
XS GIS Cut Line= 4
      3685793.54     10555776.90      3684404.63     10557634.58
      3685064.35     10558988.75      3686279.63     10562131.12
#Sta/Elev= 30
  1947.4  302.37  2116.6  294.93  2324.5  270.25  2531.1  257.91  2702.0  260.16
  2888.8  251.64  2990.4  247.66  3164.6  247.28  4010.9  245.26  4052.6  253.94
  4093.4  244.89  4096.1  244.39  4099.4  244.89  5314.8  247.84  5854.7  246.39
  6053.9  248.13  6294.1  248.27  6303.1  248.33  6400.9  249.00  7061.4  255.53
  7434.3  267.18  7925.3  266.91  8268.3  272.15  8305.1  268.39  8337.3  272.79
  8369.4  269.09  8429.6  279.22  8536.2  290.01  9012.5  326.45  9142.4  327.75
#Mann=17,-1,0
  1947.4    0.05       0  2116.6    0.12       0  2324.5    0.05       0
  2888.8    0.12       0  2990.4    0.16       0  3164.6    0.12       0
  4093.4    0.07       0  4099.4    0.12       0  5314.8    0.16       0
  5854.7    0.05       0  6053.9    0.16       0  6294.1    0.05       0
  6303.1    0.16       0  6400.9    0.05       0  7925.3    0.12       0
  8429.6    0.16       0  8536.2    0.05       0
Bank Sta=4093.4,4099.4
Exp/Cntr=0.3,0.1

Type RM Length L Ch R = 1,880,0,0,0
BEGIN DESCRIPTION:
UNT 158 IN UKCR 1.0
END DESCRIPTION:
XS GIS Cut Line= 5
      3685663.35     10555651.06      3683384.66     10556341.18
      3683124.24     10556979.20      3683423.72     10558333.36
      3685819.32     10561835.62
#Sta/Elev= 30
  2315.7  297.84  2424.1  296.78  2589.9  276.14  2676.4  266.59  2821.1  256.18
  3198.9  248.35  3471.3  244.61  3679.3  247.79  4367.3  245.06  4457.8  244.86
  4471.8  244.85  4576.4  244.78  4846.7  245.02  4865.3  241.75  4868.1  241.25
  4871.3  241.75  4900.8  243.98  4922.4  255.75  4936.7  256.43  4998.0  242.54
  7300.7  247.49  7701.7  242.70  8090.2  248.15  8610.3  244.30  8861.5  245.24
  8943.0  250.27  9638.9  259.53 10509.0  285.63 10790.0  297.62 11015.8  313.38
#Mann=11,-1,0
  2315.7    0.05       0  2589.9    0.16       0  2676.4    0.05       0
  3198.9    0.12       0  4367.3    0.16       0  4457.8    0.12       0
  4471.8    0.16       0  4576.4    0.12       0  4865.3    0.07       0
  4871.3    0.12       0  8943.0    0.05       0
Bank Sta=4865.3,4871.3
Exp/Cntr=0.3,0.1

Chan Stop Cuts=-1