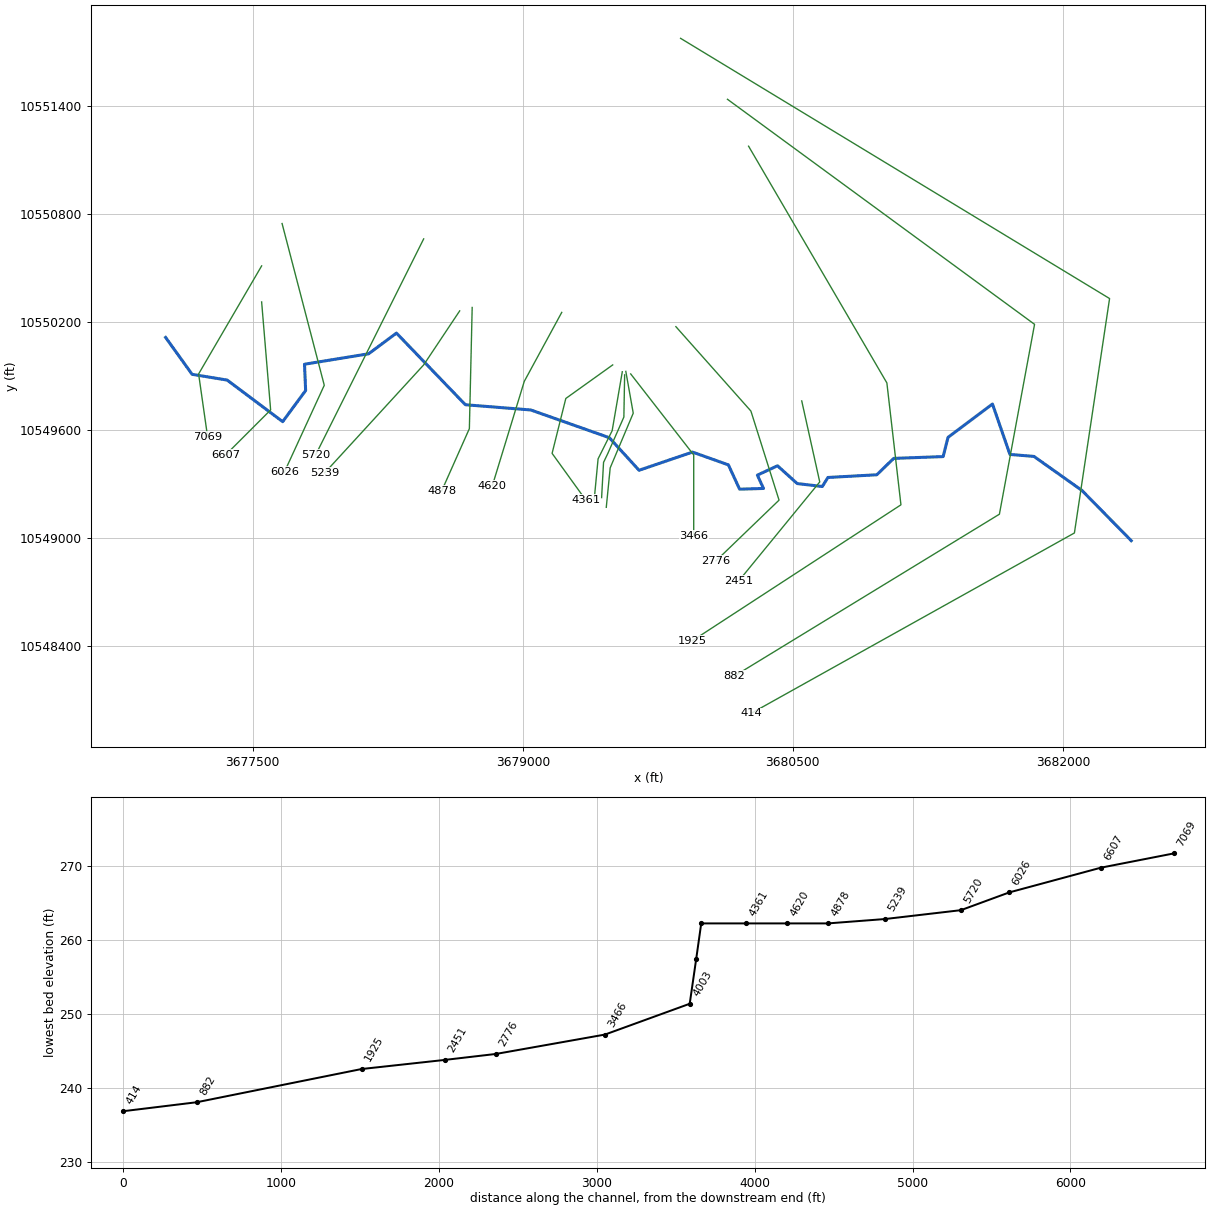
--- UNT 164 IN UKCR.prj (project) ---

Proj Title=UNT 164 IN UKCR Base Level Engineering
Current Plan=p01
Default Exp/Contr=0.3,0.1
English Units
Geom File=g01
Flow File=f01
Plan File=p01
BEGIN DESCRIPTION:
UNT 164 IN UKCR
END DESCRIPTION:

--- UNT 164 IN UKCR.p01 (plan) ---

Plan Title=Multiple Run
Short Identifier=Multiple
Geom File=g01
Flow File=f01
Subcritical Flow
K Sum by GR= 0
Std Step Tol= 0.01
Critical Tol= 0.01
Num of Std Step Trials= 20
Max Error Tol= 0.3
Flow Tol Ratio= 0.001
Split Flow NTrial= 30
Split Flow Tol= 0.02
Split Flow Ratio= 0.02
Log Output Level= 0
Friction Slope Method= 1
Unsteady Friction Slope Method= 2
Unsteady Bridges Friction Slope Method= 1
Parabolic Critical Depth
Global Vel Dist=  1 , 1 , 1
Global Log Level= 0
CheckData=True
Encroach Param= -1, 0, 0, 0
BEGIN DESCRIPTION:
Multiple Run
END DESCRIPTION:

--- UNT 164 IN UKCR.f01 (steady flow) ---

Flow Title=Multiple
Number of Profiles=7
Profile Names=10-year,25-year,50-year,1pct_min,100-year,1pct_plu,500-year
River Rch & RM= UNT 164 IN UKCR,Reach-1,7069
     527     717     874     783    1059    1433    1564
River Rch & RM= UNT 164 IN UKCR,Reach-1,4878
     716     987    1215    1099    1486    2009    2231
Boundary for River Rch & Prof#=UNT 164 IN UKCR,Reach-1,1
Up Type=0
Dn Type=3
Dn Slope=0.005
Boundary for River Rch & Prof#=UNT 164 IN UKCR,Reach-1,2
Up Type=0
Dn Type=3
Dn Slope=0.005
Boundary for River Rch & Prof#=UNT 164 IN UKCR,Reach-1,3
Up Type=0
Dn Type=3
Dn Slope=0.005
Boundary for River Rch & Prof#=UNT 164 IN UKCR,Reach-1,4
Up Type=0
Dn Type=3
Dn Slope=0.005
Boundary for River Rch & Prof#=UNT 164 IN UKCR,Reach-1,5
Up Type=0
Dn Type=3
Dn Slope=0.005
Boundary for River Rch & Prof#=UNT 164 IN UKCR,Reach-1,6
Up Type=0
Dn Type=3
Dn Slope=0.005
Boundary for River Rch & Prof#=UNT 164 IN UKCR,Reach-1,7
Up Type=0
Dn Type=3
Dn Slope=0.005

--- UNT 164 IN UKCR.g01 (geometry) ---

Geom Title=Existing Conditions

River Reach=UNT 164 IN UKCR,Reach-1
Reach XY= 30
      3677016.25     10550113.00      3677163.25     10549908.00
      3677358.00     10549876.00      3677666.50     10549645.00
      3677794.00     10549818.00      3677787.75     10549964.00
      3678143.75     10550022.00      3678298.50     10550137.00
      3678681.25     10549739.00      3679044.50     10549710.00
      3679480.75     10549556.00      3679646.00     10549375.00
      3679942.75     10549476.00      3680142.25     10549405.00
      3680204.50     10549270.00      3680337.25     10549274.00
      3680303.25     10549348.00      3680415.00     10549400.00
      3680524.75     10549301.00      3680664.00     10549285.00
      3680695.00     10549335.00      3680966.50     10549350.00
      3681060.50     10549441.00      3681335.00     10549451.00
      3681362.25     10549558.00      3681609.00     10549743.00
      3681706.00     10549463.00      3681839.50     10549452.00
      3682106.00     10549263.00      3682379.75     10548984.00

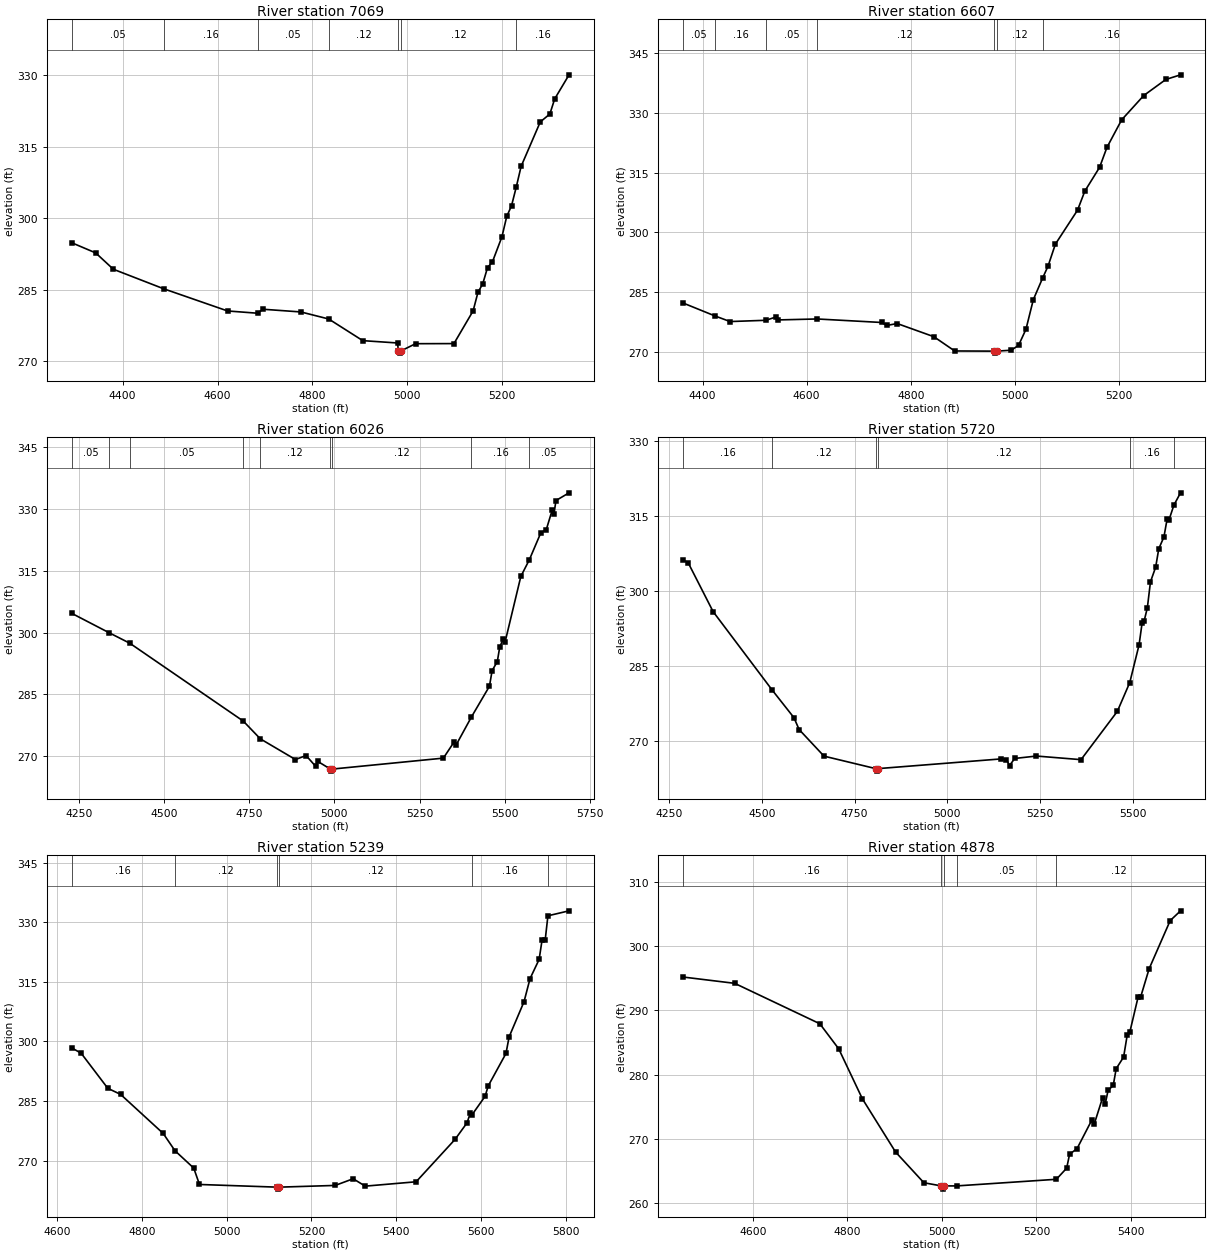
Type RM Length L Ch R = 1,7069,462,462,462
BEGIN DESCRIPTION:
UNT 164 IN UKCR 13.0
END DESCRIPTION:
XS GIS Cut Line= 3
      3677549.61     10550510.19      3677199.61     10549910.19
      3677249.61     10549560.17
#Sta/Elev= 30
  4292.4  294.88  4343.3  292.73  4380.5  289.30  4486.9  285.19  4621.1  280.55
  4684.7  280.07  4695.5  280.91  4775.7  280.34  4834.3  278.86  4906.0  274.32
  4979.2  273.83  4981.1  272.20  4983.9  271.70  4987.1  272.20  5017.3  273.68
  5098.1  273.70  5138.5  280.57  5148.6  284.43  5158.8  286.26  5168.9  289.66
  5179.0  290.81  5199.2  296.11  5209.3  300.38  5219.4  302.62  5229.6  306.64
  5239.6  310.89  5280.0  320.22  5300.2  321.88  5310.3  325.04  5340.6  330.10
#Mann=7,-1,0
  4292.4    0.05       0  4486.9    0.16       0  4684.7    0.05       0
  4834.3    0.12       0  4981.1    0.07       0  4987.1    0.12       0
  5229.6    0.16       0
Bank Sta=4981.1,4987.1
Exp/Cntr=0.3,0.1

Type RM Length L Ch R = 1,6607,581,581,581
BEGIN DESCRIPTION:
UNT 164 IN UKCR 12.0
END DESCRIPTION:
XS GIS Cut Line= 3
      3677549.61     10550310.20      3677599.61     10549710.19
      3677349.64     10549460.22
#Sta/Elev= 30
  4362.6  282.33  4423.9  279.09  4452.9  277.68  4522.0  278.00  4540.7  278.82
  4545.7  278.09  4620.1  278.33  4743.9  277.45  4754.0  276.71  4774.0  277.18
  4844.3  273.89  4884.4  270.31  4959.2  270.27  4961.9  269.77  4965.2  270.27
  4993.0  270.50  5007.1  271.72  5021.3  275.75  5035.4  283.16  5053.1  288.53
  5063.7  291.57  5077.8  297.08  5120.3  305.58  5134.4  310.37  5162.7  316.32
  5176.8  321.31  5205.1  328.22  5247.5  334.31  5290.0  338.34  5318.2  339.50
#Mann=7,-1,0
  4362.6    0.05       0  4423.9    0.16       0  4522.0    0.05       0
  4620.1    0.12       0  4959.2    0.07       0  4965.2    0.12       0
  5053.1    0.16       0
Bank Sta=4959.2,4965.2
Exp/Cntr=0.3,0.1

Type RM Length L Ch R = 1,6026,306,306,306
BEGIN DESCRIPTION:
UNT 164 IN UKCR 11.0
END DESCRIPTION:
XS GIS Cut Line= 3
      3677663.16     10550745.54      3677897.54     10549847.11
      3677676.18     10549365.32
#Sta/Elev= 30
  4229.2  304.68  4340.2  299.92  4400.1  297.41  4732.8  278.54  4782.8  274.24
  4885.8  269.23  4916.8  270.20  4945.3  267.55  4950.5  268.81  4988.0  266.92
  4990.7  266.42  4994.0  266.92  5319.4  269.57  5351.6  273.58  5357.1  272.80
  5401.6  279.53  5454.5  286.99  5462.4  290.80  5477.5  292.94  5484.5  296.41
  5495.0  298.54  5500.5  297.76  5546.5  313.59  5571.7  317.68  5605.5  324.24
  5620.9  324.87  5638.4  329.64  5643.9  328.83  5649.5  331.99  5687.9  333.86
#Mann=9,-1,0
  4229.2    0.05       0  4340.2    0.16       0  4400.1    0.05       0
  4732.8    0.16       0  4782.8    0.12       0  4988.0    0.07       0
  4994.0    0.12       0  5401.6    0.16       0  5571.7    0.05       0
Bank Sta=4988,4994
Exp/Cntr=0.3,0.1

Type RM Length L Ch R = 1,5720,481,481,481
BEGIN DESCRIPTION:
UNT 164 IN UKCR 10.0
END DESCRIPTION:
XS GIS Cut Line= 3
      3678449.62     10550660.21      3678149.61     10550060.19
      3677849.59     10549460.16
#Sta/Elev= 30
  4287.1  306.18  4301.1  305.59  4368.2  295.86  4526.8  280.27  4586.2  274.69
  4600.2  272.32  4667.3  267.01  4806.8  264.52  4809.6  264.02  4812.8  264.52
  5145.2  266.46  5159.2  266.32  5167.6  265.13  5181.6  266.55  5240.3  267.03
  5360.4  266.31  5458.3  275.94  5491.9  281.71  5517.0  289.24  5525.3  293.68
  5530.9  294.08  5539.3  296.62  5547.7  301.81  5561.7  304.73  5570.1  308.41
  5584.0  310.76  5592.4  314.26  5598.0  314.24  5611.0  317.14  5628.8  319.57
#Mann=6,-1,0
  4287.1    0.16       0  4526.8    0.12       0  4806.8    0.07       0
  4812.8    0.12       0  5491.9    0.16       0  5611.0    0.05       0
Bank Sta=4806.8,4812.8
Exp/Cntr=0.3,0.1

Type RM Length L Ch R = 1,5239,361,361,361
BEGIN DESCRIPTION:
UNT 164 IN UKCR 9.0
END DESCRIPTION:
XS GIS Cut Line= 3
      3678649.63     10550260.23      3678449.61     10549960.19
      3677899.64     10549360.22
#Sta/Elev= 30
  4633.7  298.38  4656.3  297.03  4719.4  288.18  4749.4  286.67  4850.1  276.83
  4877.9  272.48  4922.2  268.11  4935.7  263.99  5118.6  263.32  5121.4  262.82
  5124.6  263.32  5256.1  263.75  5298.6  265.43  5327.0  263.57  5447.2  264.67
  5539.1  275.34  5567.5  279.52  5574.9  281.91  5579.0  281.51  5610.0  286.17
  5617.4  288.80  5659.3  296.96  5666.7  301.13  5701.9  309.98  5716.1  315.79
  5737.6  320.63  5744.4  325.43  5751.8  325.41  5758.3  331.60  5808.2  332.85
#Mann=6,-1,0
  4633.7    0.16       0  4877.9    0.12       0  5118.6    0.07       0
  5124.6    0.12       0  5579.0    0.16       0  5758.3    0.05       0
Bank Sta=5118.6,5124.6
Exp/Cntr=0.3,0.1

Type RM Length L Ch R = 1,4878,258,258,258
BEGIN DESCRIPTION:
UNT 164 IN UKCR 8.0
END DESCRIPTION:
XS GIS Cut Line= 3
      3678719.12     10550279.35      3678703.46     10549606.35
      3678549.61     10549260.18
#Sta/Elev= 30
  4452.7  295.20  4561.9  294.22  4741.9  287.94  4781.9  284.04  4832.0  276.26
  4902.0  268.01  4962.0  263.22  4999.0  262.73  5001.8  262.23  5005.0  262.73
  5031.6  262.73  5242.1  263.76  5263.9  265.49  5270.1  267.66  5285.8  268.52
  5316.6  272.90  5322.1  272.32  5339.9  276.44  5345.3  275.42  5351.5  277.58
  5362.4  278.35  5368.6  280.95  5384.3  282.76  5391.8  286.12  5397.3  286.60
  5415.1  292.13  5420.6  292.16  5438.3  296.49  5482.8  303.97  5504.7  305.49
#Mann=5,-1,0
  4452.7    0.16       0  4999.0    0.07       0  5005.0    0.16       0
  5031.6    0.05       0  5242.1    0.12       0
Bank Sta=4999,5005
Exp/Cntr=0.3,0.1

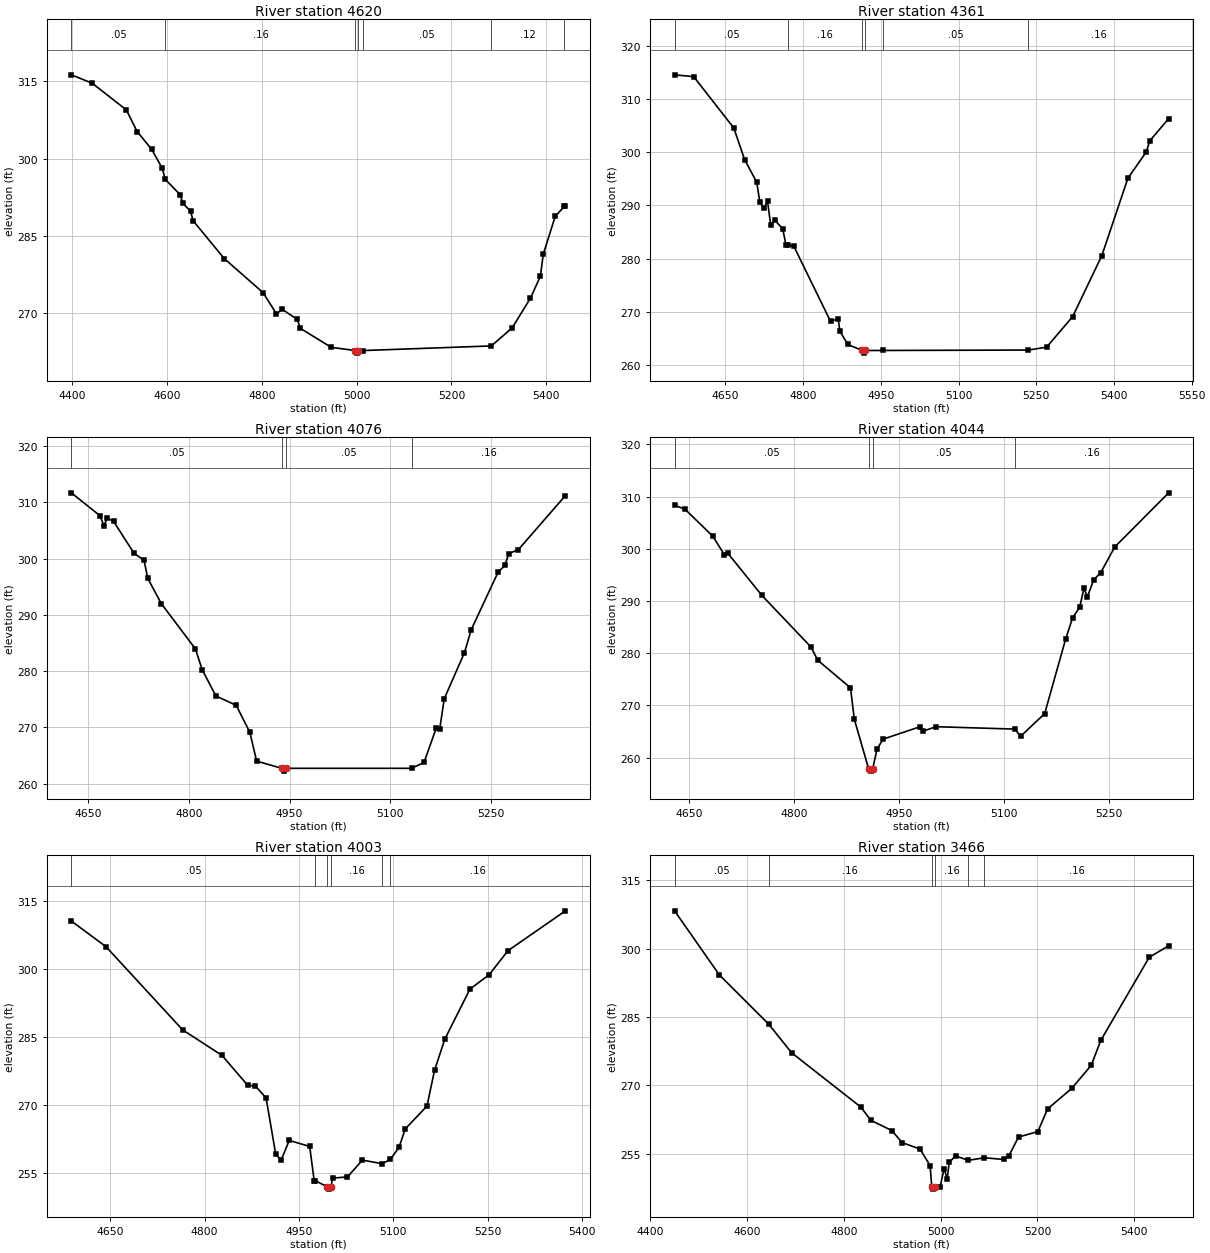
Type RM Length L Ch R = 1,4620,259,259,259
BEGIN DESCRIPTION:
Mapping XS 52c7006a
END DESCRIPTION:
XS GIS Cut Line= 3
      3679216.57     10550252.05      3679008.41     10549868.70
      3678831.18     10549289.63
#Sta/Elev= 30
  4398.7  316.28  4442.7  314.65  4514.6  309.46  4537.4  305.26  4568.1  301.80
  4590.0  298.19  4596.8  295.96  4628.0  293.02  4633.7  291.31  4649.9  289.83
  4655.6  287.91  4721.1  280.59  4802.9  273.98  4831.2  269.85  4843.2  270.74
  4875.2  268.77  4881.2  267.06  4946.8  263.35  4997.7  262.73  5000.4  262.23
  5003.7  262.73  5013.6  262.73  5284.2  263.63  5328.2  267.14  5366.7  272.90
  5387.6  277.16  5393.7  281.42  5419.0  288.82  5438.4  290.75  5440.5  290.75
#Mann=7,-1,0
  4398.7    0.05       0  4596.8    0.16       0  4997.7    0.07       0
  5003.7    0.16       0  5013.6    0.05       0  5284.2    0.12       0
  5438.4    0.16       0
Bank Sta=4997.7,5003.7
Exp/Cntr=0.3,0.1

Type RM Length L Ch R = 1,4361,285,285,285
BEGIN DESCRIPTION:
UNT 164 IN UKCR 7.0
END DESCRIPTION:
XS GIS Cut Line= 4
      3679499.61     10549960.19      3679239.22     10549773.90
      3679162.97     10549468.90      3679349.63     10549210.15
#Sta/Elev= 30
  4552.0  314.52  4588.9  314.18  4666.3  304.53  4687.3  298.56  4710.5  294.35
  4716.6  290.63  4724.1  289.44  4731.4  290.76  4737.5  286.33  4746.1  287.15
  4760.9  285.55  4767.0  282.49  4771.7  282.47  4781.7  282.41  4853.0  268.20
  4867.7  268.71  4871.1  266.34  4886.2  263.86  4914.2  262.73  4917.0  262.23
  4920.2  262.73  4953.6  262.73  5234.8  262.81  5270.0  263.35  5320.3  269.09
  5376.7  280.57  5427.0  295.11  5462.6  300.05  5468.8  302.08  5505.6  306.29
#Mann=6,-1,0
  4552.0    0.05       0  4771.7    0.16       0  4914.2   0.033       0
  4920.2    0.16       0  4953.6    0.05       0  5234.8    0.16       0
Bank Sta=4914.2,4920.2
Exp/Cntr=0.3,0.1

Type RM Length L Ch R = 1,4076,32,32,32
BEGIN DESCRIPTION:
Mapping XS 4cabd620
END DESCRIPTION:
XS GIS Cut Line= 4
      3679552.93     10549922.22      3679496.51     10549594.55
      3679418.39     10549438.30      3679396.69     10549210.42
#Sta/Elev= 30
  4625.0  311.72  4667.7  307.64  4673.4  305.89  4678.5  307.23  4687.9  306.64
  4718.4  300.96  4733.3  299.74  4738.7  296.53  4759.0  292.02  4809.7  283.98
  4819.9  280.28  4840.2  275.62  4870.6  273.92  4890.9  269.14  4901.0  264.01
  4938.6  262.73  4941.4  262.23  4944.6  262.73  5131.8  262.73  5150.4  263.77
  5168.7  269.93  5173.8  269.72  5180.5  275.10  5210.7  283.32  5220.7  287.38
  5260.9  297.64  5270.9  298.82  5276.7  300.92  5291.0  301.62  5361.1  311.24
#Mann=4,-1,0
  4625.0    0.05       0  4938.6    0.03       0  4944.6    0.05       0
  5131.8    0.16       0
Bank Sta=4938.6,4944.6
Exp/Cntr=0.3,0.1

Type RM Length L Ch R = 1,4044,41,41,41
BEGIN DESCRIPTION:
Mapping XS adaed6f3
END DESCRIPTION:
XS GIS Cut Line= 5
      3679565.96     10549904.84      3679561.62     10549670.50
      3679472.64     10549468.68      3679448.77     10549418.77
      3679438.03     10549223.23
#Sta/Elev= 30
  4629.1  308.33  4643.8  307.60  4683.8  302.40  4700.3  298.86  4705.3  299.13
  4753.8  291.08  4823.8  281.22  4833.8  278.64  4880.5  273.37  4886.0  267.34
  4906.3  257.91  4909.1  257.41  4912.3  257.91  4918.5  261.66  4927.2  263.54
  4979.3  265.89  4984.8  265.09  5002.6  265.92  5115.6  265.46  5123.5  264.07
  5158.0  268.42  5188.0  282.72  5198.0  286.81  5208.0  288.77  5214.1  292.43
  5219.1  290.80  5228.1  294.08  5238.1  295.42  5258.1  300.34  5335.2  310.72
#Mann=4,-1,0
  4629.1    0.05       0  4906.3    0.03       0  4912.3    0.05       0
  5115.6    0.16       0
Bank Sta=4906.3,4912.3
Exp/Cntr=0.3,0.1

Type RM Length L Ch R = 1,4003,537,537,537
BEGIN DESCRIPTION:
Mapping XS 23bddc1e
END DESCRIPTION:
XS GIS Cut Line= 4
      3679572.48     10549924.36      3679613.70     10549692.20
      3679485.66     10549388.38      3679463.97     10549169.24
#Sta/Elev= 30
  4588.1  310.54  4643.1  304.89  4765.0  286.52  4827.7  280.88  4868.6  274.26
  4880.3  274.17  4897.7  271.52  4912.9  259.21  4921.4  257.69  4934.6  262.11
  4967.1  260.78  4974.3  253.12  4976.2  253.23  4995.0  251.86  4997.8  251.36
  5001.0  251.86  5003.5  253.79  5027.2  254.05  5050.9  257.77  5082.4  256.97
  5095.3  257.91  5109.2  260.61  5119.1  264.67  5153.6  269.69  5165.6  277.57
  5181.9  284.46  5222.1  295.55  5252.3  298.66  5282.4  304.00  5373.8  312.80
#Mann=6,-1,0
  4588.1    0.05       0  4976.2    0.16       0  4995.0    0.07       0
  5001.0    0.16       0  5082.4    0.05       0  5095.3    0.16       0
Bank Sta=4995,5001
Exp/Cntr=0.3,0.1

Type RM Length L Ch R = 1,3466,690,690,690
BEGIN DESCRIPTION:
UNT 164 IN UKCR 6.0
END DESCRIPTION:
XS GIS Cut Line= 3
      3679599.60     10549910.19      3679949.61     10549460.19
      3679949.61     10549010.18
#Sta/Elev= 30
  4450.8  308.33  4543.1  294.27  4645.3  283.41  4692.4  277.15  4835.4  265.21
  4856.2  262.29  4899.6  260.05  4920.5  257.41  4957.6  255.99  4978.4  252.36
  4981.7  247.69  4984.4  247.19  4987.7  247.69  4999.2  247.75  5007.3  251.72
  5013.7  249.39  5017.7  253.04  5030.9  254.50  5057.1  253.51  5090.6  254.08
  5130.9  253.70  5140.9  254.48  5160.9  258.63  5200.9  259.83  5220.9  264.81
  5270.9  269.33  5310.9  274.37  5330.9  279.89  5430.9  298.14  5470.9  300.65
#Mann=6,-1,0
  4450.8    0.05       0  4645.3    0.16       0  4981.7    0.07       0
  4987.7    0.16       0  5057.1    0.12       0  5090.6    0.16       0
Bank Sta=4981.7,4987.7
Exp/Cntr=0.3,0.1

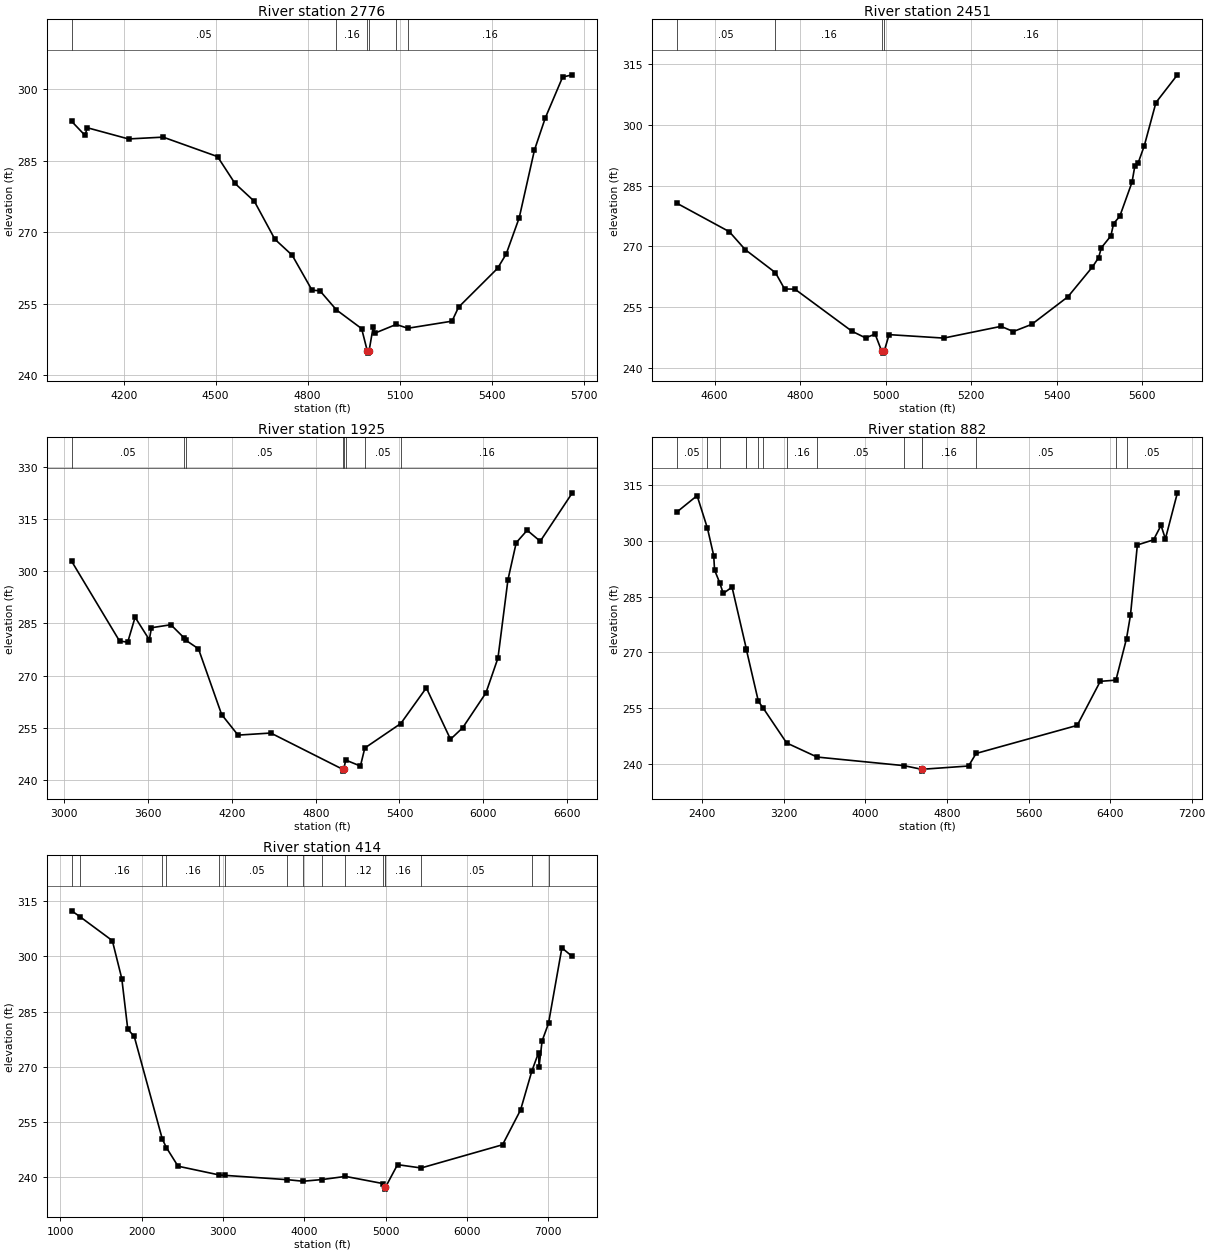
Type RM Length L Ch R = 1,2776,325,325,325
BEGIN DESCRIPTION:
UNT 164 IN UKCR 5.0
END DESCRIPTION:
XS GIS Cut Line= 4
      3679850.68     10550172.61      3680267.33     10549703.88
      3680423.58     10549209.09      3680073.30     10548871.78
#Sta/Elev= 30
  4030.6  293.29  4074.0  290.35  4081.2  291.96  4215.8  289.60  4328.7  289.98
  4506.0  285.89  4562.8  280.26  4626.4  276.46  4693.1  268.51  4749.5  265.15
  4814.2  257.80  4839.9  257.68  4893.9  253.65  4975.9  249.72  4994.2  245.07
  4996.9  244.57  5000.2  245.07  5013.5  250.04  5018.7  248.76  5088.4  250.60
  5126.5  249.80  5270.6  251.29  5291.9  254.23  5419.0  262.39  5447.3  265.42
  5489.7  273.03  5539.4  287.27  5574.6  294.00  5631.2  302.61  5662.9  303.08
#Mann=6,-1,0
  4030.6    0.05       0  4893.9    0.16       0  4994.2    0.07       0
  5000.2    0.16       0  5088.4    0.12       0  5126.5    0.16       0
Bank Sta=4994.2,5000.2
Exp/Cntr=0.3,0.1

Type RM Length L Ch R = 1,2451,526,526,526
BEGIN DESCRIPTION:
UNT 164 IN UKCR 4.0
END DESCRIPTION:
XS GIS Cut Line= 3
      3680549.60     10549760.22      3680649.61     10549310.19
      3680199.64     10548760.22
#Sta/Elev= 30
  4511.3  280.66  4634.3  273.64  4671.4  269.24  4742.3  263.55  4763.6  259.55
  4787.9  259.50  4921.1  249.16  4953.1  247.51  4975.5  248.45  4990.8  244.26
  4993.6  243.76  4996.8  244.26  5008.2  248.31  5136.0  247.46  5270.2  250.35
  5298.9  249.07  5342.0  250.84  5426.7  257.63  5484.1  264.97  5498.5  267.25
  5504.9  269.69  5527.2  272.60  5533.6  275.65  5548.0  277.42  5576.7  285.82
  5583.2  289.74  5591.1  290.57  5605.4  294.78  5632.7  305.42  5682.9  312.24
#Mann=4,-1,0
  4511.3    0.05       0  4742.3    0.16       0  4990.8    0.07       0
  4996.8    0.16       0
Bank Sta=4990.8,4996.8
Exp/Cntr=0.3,0.1

Type RM Length L Ch R = 1,1925,1043,1043,1043
BEGIN DESCRIPTION:
UNT 164 IN UKCR 3.0
END DESCRIPTION:
XS GIS Cut Line= 4
      3680254.33     10551175.20      3681022.54     10549860.13
      3681100.66     10549183.05      3679943.23     10548428.77
#Sta/Elev= 30
  3052.2  302.83  3394.7  279.94  3453.4  279.59  3506.3  286.76  3608.0  280.31
  3623.7  283.75  3762.6  284.61  3856.7  280.85  3871.2  280.11  3960.1  277.70
  4126.3  258.79  4243.7  252.88  4478.4  253.48  4994.9  243.03  4997.7  242.53
  5000.9  243.03  5014.8  245.71  5120.3  243.99  5151.8  249.18  5409.4  256.21
  5592.3  266.47  5765.5  251.69  5853.1  255.01  6019.1  265.00  6105.5  275.04
  6177.1  297.56  6236.4  308.20  6314.8  311.77  6408.3  308.61  6638.3  322.53
#Mann=8,-1,0
  3052.2    0.05       0  3856.7    0.16       0  3871.2    0.05       0
  4994.9    0.04       0  5000.9    0.05       0  5014.8    0.16       0
  5151.8    0.05       0  5409.4    0.16       0
Bank Sta=4994.9,5000.9
Exp/Cntr=0.3,0.1

Type RM Length L Ch R = 1,882,468,468,468
BEGIN DESCRIPTION:
UNT 164 IN UKCR 2.0
END DESCRIPTION:
XS GIS Cut Line= 4
      3680137.16     10551435.62      3681842.85     10550185.65
      3681647.54     10549130.96      3680176.14     10548232.50
#Sta/Elev= 30
  2148.7  307.81  2348.2  312.25  2449.7  303.47  2511.3  296.09  2519.5  292.22
  2569.0  288.85  2605.2  285.91  2690.9  287.62  2830.5  271.07  2832.6  270.66
  2949.4  256.84  2996.6  255.02  3226.7  245.63  3525.6  241.83  4376.7  239.52
  4550.7  238.54  4553.4  238.04  4556.7  238.54  5011.3  239.42  5085.0  242.80
  6076.9  250.36  6303.3  262.23  6456.9  262.55  6560.7  273.73  6599.6  280.05
  6667.2  298.97  6826.0  300.35  6899.5  304.24  6942.2  300.60  7060.0  313.01
#Mann=15,-1,0
  2148.7    0.05       0  2449.7    0.16       0  2569.0    0.05       0
  2830.5    0.16       0  2832.6    0.05       0  2949.4    0.16       0
  2996.6    0.05       0  3226.7    0.16       0  3525.6    0.05       0
  4376.7    0.16       0  4550.7    0.07       0  4556.7    0.16       0
  5085.0    0.05       0  6456.9    0.16       0  6560.7    0.05       0
Bank Sta=4550.7,4556.7
Exp/Cntr=0.3,0.1

Type RM Length L Ch R = 1,414,0,0,0
BEGIN DESCRIPTION:
UNT 164 IN UKCR 1.0
END DESCRIPTION:
XS GIS Cut Line= 4
      3679876.68     10551774.21      3682259.52     10550328.88
      3682064.20     10549026.80      3680268.23     10548024.69
#Sta/Elev= 30
  1138.3  312.33  1246.1  310.64  1638.3  304.24  1754.6  293.95  1828.3  280.20
  1907.8  278.25  2253.5  250.38  2303.7  248.08  2446.7  243.04  2956.3  240.65
  3027.7  240.55  3793.2  239.38  3985.7  238.96  4219.7  239.42  4507.0  240.27
  4965.5  238.34  4992.8  237.32  4995.5  236.82  4998.8  237.32  5147.4  243.46
  5438.0  242.56  6439.7  248.86  6661.3  258.29  6799.0  268.77  6883.0  273.86
  6888.7  269.98  6926.4  277.03  7005.1  281.79  7169.8  302.27  7298.5  299.94
#Mann=16,-1,0
  1138.3    0.05       0  1246.1    0.16       0  2253.5    0.05       0
  2303.7    0.16       0  2956.3    0.12       0  3027.7    0.05       0
  3793.2    0.12       0  3985.7    0.05       0  4219.7    0.16       0
  4507.0    0.12       0  4965.5    0.16       0  4992.8    0.07       0
  4998.8    0.16       0  5438.0    0.05       0  6799.0    0.16       0
  7005.1    0.05       0
Bank Sta=4992.8,4998.8
Exp/Cntr=0.3,0.1

Chan Stop Cuts=-1