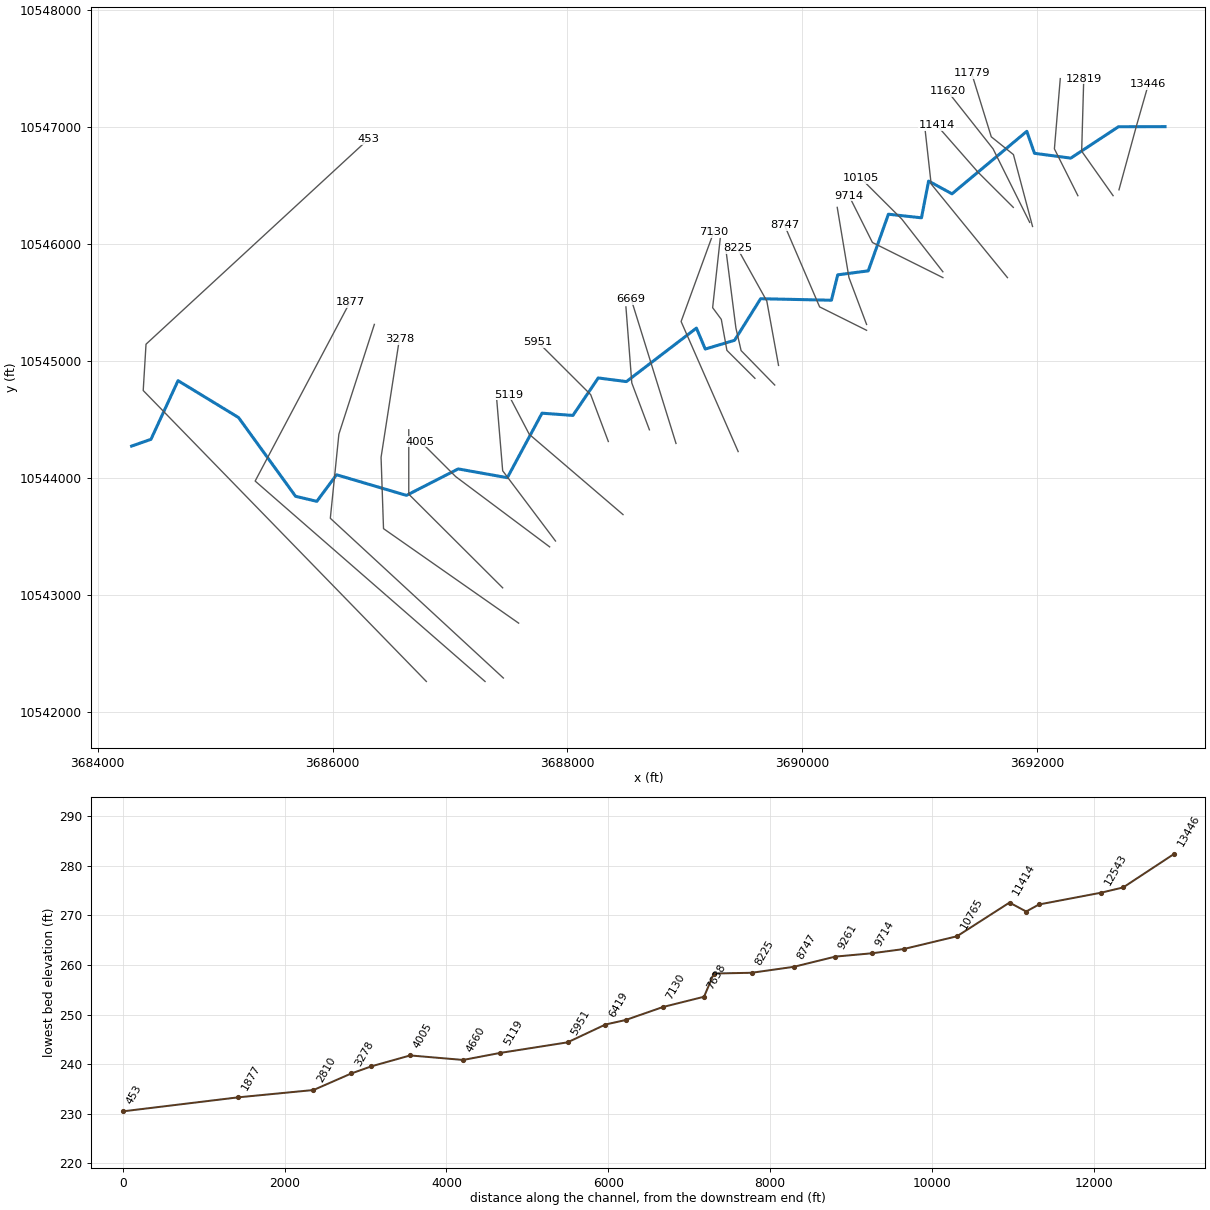
--- UNT 165 IN UKCR.prj (project) ---

Proj Title=UNT 165 IN UKCR Base Level Engineering
Current Plan=p01
Default Exp/Contr=0.3,0.1
English Units
Geom File=g01
Geom File=g02
Flow File=f01
Plan File=p01
Plan File=p02
Y Axis Title=Elevation
X Axis Title(PF)=Main Channel Distance
X Axis Title(XS)=Station
BEGIN DESCRIPTION:
UNT 165 IN UKCR
END DESCRIPTION:
DSS Export Rating Curves= 0
DSS Export Rating Curve Sorted= 0
DSS Export Volume Flow Curves= 0
DXF OffsetX= 0
DXF OffsetY= 0
DXF ScaleX= 1
DXF ScaleY= 10

--- UNT 165 IN UKCR.p01 (plan) ---

Plan Title=Multiple Run
Program Version=4.10
Short Identifier=Multiple
Geom File=g01
Flow File=f01
Subcritical Flow
K Sum by GR= 0
Std Step Tol= 0.01
Critical Tol= 0.01
Num of Std Step Trials= 20
Max Error Tol= 0.3
Flow Tol Ratio= 0.001
Split Flow NTrial= 30
Split Flow Tol= 0.02
Split Flow Ratio= 0.02
Log Output Level= 0
Friction Slope Method= 1
Unsteady Friction Slope Method= 2
Unsteady Bridges Friction Slope Method= 1
Parabolic Critical Depth
Global Vel Dist= 1 , 1 , 1
Global Log Level= 0
CheckData=True
Encroach Param=-1 ,0,0, 0
BEGIN DESCRIPTION:
Multiple Run
END DESCRIPTION:
Computation Interval=1HOUR
Output Interval=1HOUR
Run HTab= 0
Run UNet= 0
Run PostProcess= 0
Run WQNet= 0
UNET Theta= 1
UNET Theta Warmup= 1
UNET ZTol= 0.02
UNET ZSATol= 0.05
UNET MxIter= 20
UNET MaxInSteps= 0
UNET DtIC= 0
UNET DtMin= 0
UNET MaxCRTS= 20
UNET WFStab= 2
UNET SFStab= 1
UNET WFX= 1
UNET SFX= 1
UNET DSS MLevel= 4
UNET DZMax Abort= 100
UNET Convert EG Bridges= 0
UNET Use Existing IB Tables=-1
UNET Froude Reduction=False
UNET Froude Limit= 1
UNET Froude Power= 10
UNET Time Slicing=0,0, 5
UNET Junction Losses=0
Instantaneous Interval=1HOUR
Write IC File= 0
Write IC File at Sim End=0
Echo Input=False
Echo Parameters=False
Echo Output=False
Write Detailed= 0
WQ AD Non Conservative
WQ ULTIMATE=-1
WQ Max Comp Step=1HOUR
WQ Output Interval=15MIN
WQ Output Selected Increments= 0
WQ Output face flow=0
WQ Output face velocity=0
WQ Output face area=0
WQ Output face dispersion=0
WQ Output cell volume=0
WQ Output cell surface area=0
WQ Output cell continuity=0
WQ Output cumulative cell continuity=0
WQ Output face conc=0
WQ Output face dconc_dx=0
WQ Output face courant=0
WQ Output face peclet=0
WQ Output face adv mass=0
WQ Output face disp mass=0
WQ Output cell mass=0
WQ Output cell source sink temp=0
WQ Output cell source sink nsm=0
WQ Output MaxMinRange=-1
WQ Daily Max Min Mean=-1
WQ Daily Range=0
WQ Daily Time=0
WQ Create Restart=0
WQ Fixed Restart=0
WQ System Summary=0
WQ Use Fixed Temperature=0
Sorting and Armoring Iterations= 10
XS Update Threshold= 0.02
Hydraulics Update Threshold= 0.02
Energy Slope Method= 1
Volume Change Method= 0
XS Weighting Method= 0
Number of US Weighted Cross Sections= 1
Number of DS Weighted Cross Sections= 1
Upstream XS Weight=0.25
Main XS Weight=0.5
Downstream XS Weight=0.25
Number of DS XS's Weighted with US Boundary= 1
Upstream Boundary Weight= 1
Weight of XSs Associated with US Boundary= 0
Number of US XS's Weighted with DS Boundary= 1
Downstream Boundary Weight= 0.5
Weight of XSs Associated with DS Boundary= 0.5
Sediment Output Level= 4
Mass or Volume Output= 0
Output Increment Type= 1
Profile and TS Output Increment= 10
XS Output Flag= 0
XS Output Increment= 10
Disregard all LS=0
Disregard all Conn=0
Disregard all Breaches=0
Disregard all Pumps=0

--- UNT 165 IN UKCR.p02 (plan) ---

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Plan Title=ARC
Short Identifier=arc
Geom File=g02
Flow File=f01

--- UNT 165 IN UKCR.f01 (steady flow) ---

Flow Title=Multiple
Number of Profiles=7
Profile Names=10-year,25-year,50-year,1pct_min,100-year,1pct_plu,500-year
River Rch & RM= UNT 165 IN UKCR,Reach-1,13446
     649     899    1110    1009    1365    1846    2070
River Rch & RM= UNT 165 IN UKCR,Reach-1,12819
     893    1250    1554    1418    1918    2594    2936
River Rch & RM= UNT 165 IN UKCR,Reach-1,7130
     982    1372    1703    1551    2098    2838    3199
Boundary for River Rch & Prof#=UNT 165 IN UKCR,Reach-1,1
Up Type=0
Dn Type=3
Dn Slope=0.005
Boundary for River Rch & Prof#=UNT 165 IN UKCR,Reach-1,2
Up Type=0
Dn Type=3
Dn Slope=0.005
Boundary for River Rch & Prof#=UNT 165 IN UKCR,Reach-1,3
Up Type=0
Dn Type=3
Dn Slope=0.005
Boundary for River Rch & Prof#=UNT 165 IN UKCR,Reach-1,4
Up Type=0
Dn Type=3
Dn Slope=0.005
Boundary for River Rch & Prof#=UNT 165 IN UKCR,Reach-1,5
Up Type=0
Dn Type=3
Dn Slope=0.005
Boundary for River Rch & Prof#=UNT 165 IN UKCR,Reach-1,6
Up Type=0
Dn Type=3
Dn Slope=0.005
Boundary for River Rch & Prof#=UNT 165 IN UKCR,Reach-1,7
Up Type=0
Dn Type=3
Dn Slope=0.005

--- UNT 165 IN UKCR.g01 (geometry) ---

Geom Title=Existing Conditions
Program Version=4.10

River Reach=UNT 165 IN UKCR ,Reach-1
Reach XY= 30
      3693092.25       10547000.        3692695.       10546999.
      3692289.25       10546731.        3691980.       10546772.
       3691914.5       10546960.      3691277.25       10546426.
        3691078.       10546535.      3691017.25       10546221.
      3690735.75       10546252.        3690564.       10545768.
        3690304.       10545734.      3690250.25       10545517.
        3689647.       10545530.       3689425.5       10545175.
       3689175.5       10545100.        3689100.       10545279.
      3688503.75       10544822.      3688263.75       10544853.
        3688048.       10544533.      3687784.75       10544552.
       3687489.5       10544001.       3687070.5       10544076.
      3686629.75       10543850.       3686034.5       10544026.
       3685866.5       10543799.       3685685.5       10543842.
       3685199.5       10544515.      3684684.25       10544830.
      3684453.75       10544329.        3684289.       10544271.

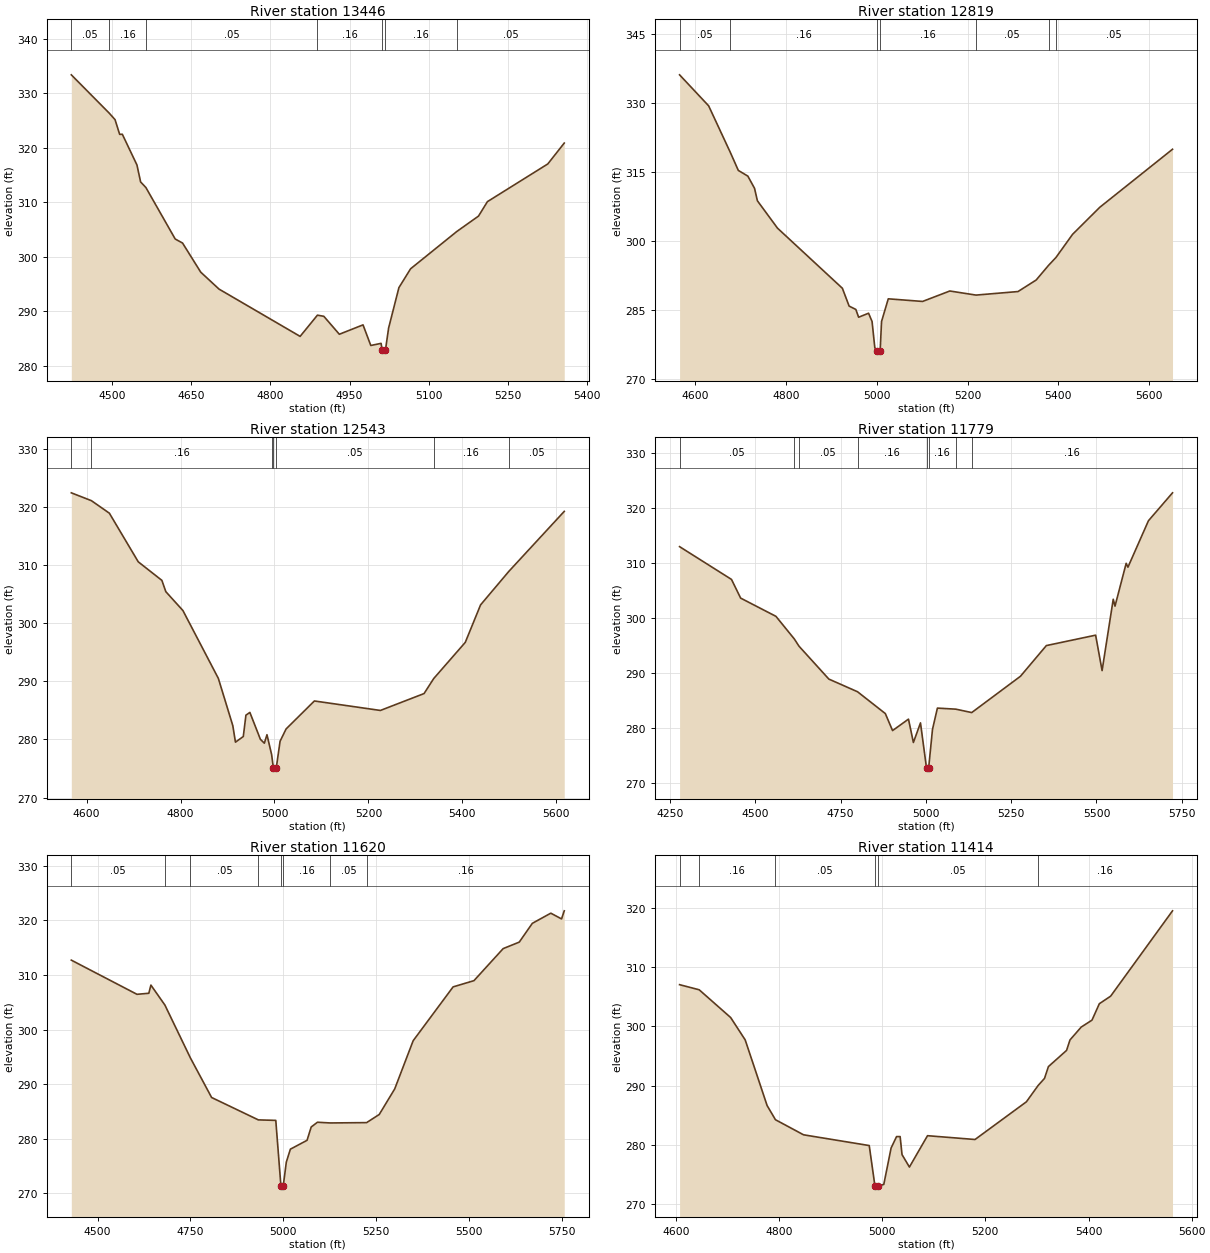
Type RM Length L Ch R = 1 ,13446   ,627,627,627
BEGIN DESCRIPTION:
UNT 165 IN UKCR 24.0
END DESCRIPTION:
XS GIS Cut Line= 3
      3692699.61     10546460.19      3692849.61     10547010.19
      3692949.61      10547360.2
#Sta/Elev= 30
  4422.8  333.37  4494.6  326.35  4505.7  325.15  4514.4  322.46  4519.5  322.47
  4547.2  316.84  4554.1  313.74  4564.1  312.71  4619.7  303.27  4633.6  302.53
  4668.1  297.19  4702.7  294.09  4856.4  285.42  4889.2  289.31  4901.3   289.1
  4930.7  285.81  4975.6  287.53  4990.3  283.75  5009.8  284.14    5012  282.85
  5014.7  282.35    5018  282.85  5024.1  286.96  5043.6  294.36  5065.7  297.81
  5153.2  304.64  5194.4  307.47  5211.3  310.12  5325.7  317.03  5356.9  320.86
#Mann= 7 ,-1 , 0
  4422.8     .05       0  4494.6     .16       0  4564.1     .05       0
  4889.2     .16       0    5012     .07       0    5018     .16       0
  5153.2     .05       0
Bank Sta=5012,5018
XS Rating Curve= 0 ,0
Exp/Cntr=0.3,0.1

Type RM Length L Ch R = 1 ,12819   ,276,276,276
BEGIN DESCRIPTION:
UNT 165 IN UKCR 23.0
END DESCRIPTION:
XS GIS Cut Line= 3
      3692649.62     10546410.18      3692381.91     10546790.07
      3692399.61     10547410.18
#Sta/Elev= 30
  4566.1  336.09  4630.1  329.35    4678  319.19  4695.4  315.32  4716.4  314.08
  4731.1  311.43  4737.4  308.72  4781.7  302.77  4924.5  289.71  4939.3  285.84
  4954.1  285.11  4960.2  283.42  4982.1  284.29  4989.8   282.5  4995.9  276.78
  5001.6  276.12  5004.3  275.62  5007.6  276.12  5010.7   282.5  5025.5  287.42
    5101  286.85    5161  289.12  5218.6  288.23  5311.1     289  5351.1  291.51
  5378.3  294.69  5394.6   296.4  5431.1  301.42  5491.1  307.31  5651.2  319.92
#Mann= 7 ,-1 , 0
  4566.1     .05       0    4678     .16       0  5001.6     .07       0
  5007.6     .16       0  5218.6     .05       0  5378.3     .16       0
  5394.6     .05       0
Bank Sta=5001.6,5007.6
XS Rating Curve= 0 ,0
Exp/Cntr=0.3,0.1

Type RM Length L Ch R = 1 ,12543   ,764,764,764
BEGIN DESCRIPTION:
UNT 165 IN UKCR 22.0
END DESCRIPTION:
XS GIS Cut Line= 3
       3692349.6      10546410.2      3692149.61     10546810.19
      3692199.61     10547410.21
#Sta/Elev= 30
  4567.5  322.39  4610.3  321.04  4648.5  318.89    4710  310.53  4760.3  307.34
  4768.7   305.4  4805.1  302.15  4880.5  290.49  4911.3  282.36  4916.9  279.53
  4933.6   280.5  4939.2  284.17  4947.6  284.64    4970  280.02  4978.4  279.35
    4984  280.81  4993.9  277.39  4997.7  275.05  5000.5  274.55  5003.7  275.05
  5011.9  279.69  5024.7   281.8  5084.9  286.61  5225.4  284.98  5318.3  287.88
    5339  290.47  5406.1  296.68  5438.7  303.13  5498.9  308.89  5616.8   319.2
#Mann= 7 ,-1 , 0
  4567.5     .05       0  4610.3     .16       0  4993.9     .05       0
  4997.7     .03       0  5003.7     .05       0    5339     .16       0
  5498.9     .05       0
Bank Sta=4997.7,5003.7
XS Rating Curve= 0 ,0
Exp/Cntr=0.3,0.1

Type RM Length L Ch R = 1 ,11779   ,159,159,159
BEGIN DESCRIPTION:
UNT 165 IN UKCR 21.0
END DESCRIPTION:
XS GIS Cut Line= 4
      3691963.36     10546147.15       3691800.6     10546761.27
       3691611.8     10546913.18      3691444.76      10547455.6
#Sta/Elev= 30
  4277.7  312.94  4429.9  306.99  4456.7   303.6  4560.2  300.29    4614  296.19
  4627.7  294.88  4715.3   288.9  4799.4   286.6  4880.9  282.64  4902.1  279.55
  4948.8  281.63  4963.2  277.39    4984  280.95  5001.8  272.69  5004.5  272.19
  5007.8  272.69  5019.2  279.77  5033.6  283.63  5087.5  283.44  5134.2  282.82
  5277.1  289.41    5353  294.98  5497.5  296.87  5516.4  290.44  5549.1  303.39
  5554.3  302.14    5587  309.91  5592.2  309.21  5652.3  317.64  5722.9  322.71
#Mann= 8 ,-1 , 0
  4277.7     .05       0    4614     .16       0  4627.7     .05       0
  4799.4     .16       0  5001.8     .07       0  5007.8     .16       0
  5087.5     .05       0  5134.2     .16       0
Bank Sta=5001.8,5007.8
XS Rating Curve= 0 ,0
Exp/Cntr=0.3,0.1

Type RM Length L Ch R = 1 ,11620   ,206,206,206
BEGIN DESCRIPTION:
Mapping XS 2d181167
END DESCRIPTION:
XS GIS Cut Line= 3
      3691939.16     10546181.93      3691627.09     10546810.58
      3691240.41     10547301.28
#Sta/Elev= 30
  4429.5  312.71  4606.2  306.45  4638.1  306.64  4643.7  308.14  4681.4  304.48
    4750   294.8  4807.1  287.55  4932.9  283.45  4979.8  283.36  4993.7  271.27
  4996.4  270.77  4999.7  271.27  5008.1  275.71  5019.1  278.09  5063.9  279.71
  5075.1  282.15  5091.9  283.02  5125.9  282.89  5224.2  282.95  5258.2  284.44
  5299.8  289.12  5349.5  297.95    5457  307.81  5513.1  308.95  5591.7  314.82
    5635  316.01  5670.2  319.45  5719.9  321.31  5748.8  320.26  5756.1  321.74
#Mann= 8 ,-1 , 0
  4429.5     .05       0  4681.4     .16       0    4750     .05       0
  4932.9     .16       0  4993.7     .07       0  4999.7     .16       0
  5125.9     .05       0  5224.2     .16       0
Bank Sta=4993.7,4999.7
XS Rating Curve= 0 ,0
Exp/Cntr=0.3,0.1

Type RM Length L Ch R = 1 ,11414   ,649,649,649
BEGIN DESCRIPTION:
UNT 165 IN UKCR 20.0
END DESCRIPTION:
XS GIS Cut Line= 3
      3691799.59     10546310.21      3691499.61     10546610.19
      3691149.63     10547010.16
#Sta/Elev= 30
  4607.2  307.01  4645.2  306.15  4706.2  301.48  4734.4  297.71  4776.9  286.65
  4793.1  284.26  4847.6  281.72  4974.9  279.91    4986  273.07  4988.8  272.57
    4992  273.07  5003.1  273.36  5017.3   279.5  5027.9  281.42  5034.8  281.42
  5038.5  278.38  5052.8  276.29  5087.9  281.57    5180  280.93  5279.6  287.28
  5302.3  290.02  5314.7  291.22  5322.3  293.21  5357.5  295.94  5364.1   297.7
  5385.9  299.87  5406.8  301.04    5421   303.8  5442.9  305.07  5562.9  319.45
#Mann= 6 ,-1 , 0
  4607.2     .05       0  4645.2     .16       0  4793.1     .05       0
    4986     .03       0    4992     .05       0  5302.3     .16       0
Bank Sta=4986,4992
XS Rating Curve= 0 ,0
Exp/Cntr=0.3,0.1

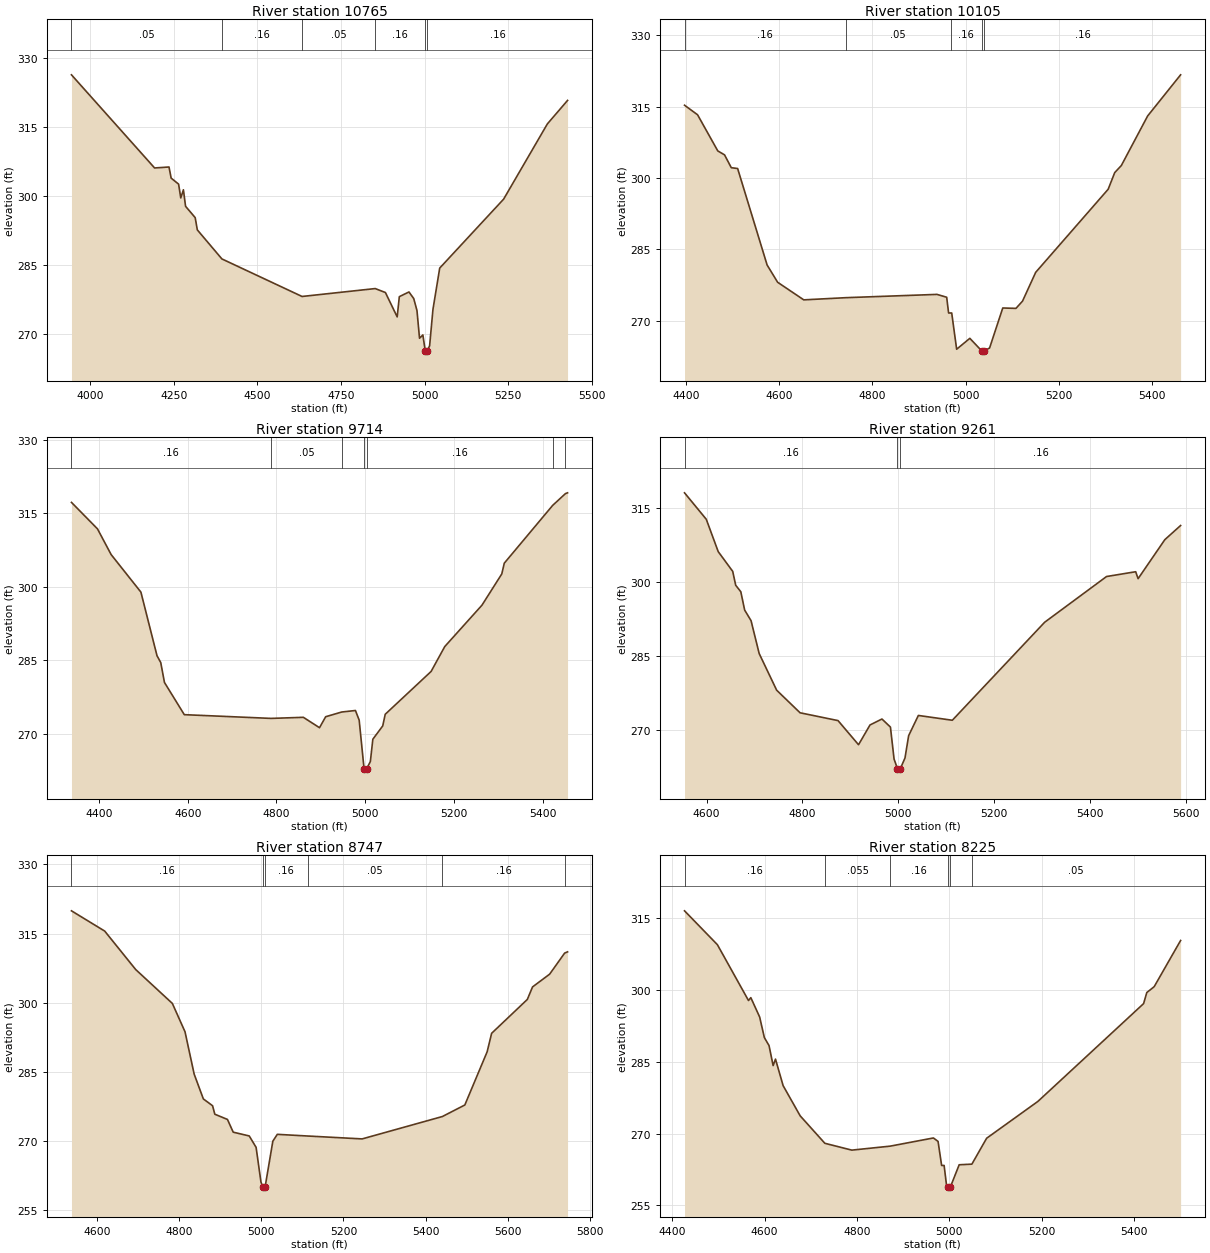
Type RM Length L Ch R = 1 ,10765   ,660,660,660
BEGIN DESCRIPTION:
UNT 165 IN UKCR 19.0
END DESCRIPTION:
XS GIS Cut Line= 3
      3691749.64     10545710.15      3691099.61     10546510.19
      3691049.61     10546960.19
#Sta/Elev= 30
  3943.9  326.35  4192.5  306.08  4235.6  306.29    4242  303.87  4264.3  302.56
  4270.8  299.56  4278.7  301.33  4285.1  297.74  4313.9  295.27  4320.3   292.6
  4393.8  286.28  4633.5  278.11  4852.3  279.83  4882.8  278.97    4918  273.67
  4924.4  278.07  4953.2  279.09  4967.5  277.66  4977.2  275.04  4984.8  269.02
  4994.8  269.73  5001.9  266.28  5004.7  265.78  5007.9  266.28    5015  267.38
    5025  275.31  5045.2  284.29  5236.3  299.29  5367.1  315.66  5427.5  320.78
#Mann= 6 ,-1 , 0
  3943.9     .05       0  4393.8     .16       0  4633.5     .05       0
  4852.3     .16       0  5001.9     .07       0  5007.9     .16       0
Bank Sta=5001.9,5007.9
XS Rating Curve= 0 ,0
Exp/Cntr=0.3,0.1

Type RM Length L Ch R = 1 ,10105   ,391,391,391
BEGIN DESCRIPTION:
UNT 165 IN UKCR 18.0
END DESCRIPTION:
XS GIS Cut Line= 3
      3691199.58     10545760.23      3690849.61     10546210.19
      3690499.62     10546560.18
#Sta/Elev= 30
  4396.8  315.33  4424.8  313.32  4468.2  305.72  4482.7  304.89  4497.2  302.19
  4510.8  302.02  4574.1  281.73  4596.7   278.1  4652.8   274.4  4743.3  274.86
  4938.8  275.55  4959.6  274.95  4963.7  271.64  4968.2  271.64  4970.4  271.64
    4981  264.02  5009.3  266.31  5034.6   263.7  5037.3   263.2  5040.6   263.7
  5051.7  264.28    5080  272.69  5108.3  272.61  5122.4  274.13  5150.7  280.19
  5306.3  297.66  5320.4  301.17  5334.5  302.64  5391.1  313.08  5461.8  321.72
#Mann= 5 ,-1 , 0
  4396.8     .16       0  4743.3     .05       0  4968.2     .16       0
  5034.6     .07       0  5040.6     .16       0
Bank Sta=5034.6,5040.6
XS Rating Curve= 0 ,0
Exp/Cntr=0.3,0.1

Type RM Length L Ch R = 1 ,9714    ,453,453,453
BEGIN DESCRIPTION:
UNT 165 IN UKCR 17.0
END DESCRIPTION:
XS GIS Cut Line= 3
      3691199.57     10545710.21      3690599.61     10546010.19
       3690399.6      10546410.2
#Sta/Elev= 30
    4338  317.19  4396.6  311.79  4427.4  306.54  4494.5  298.88  4530.8  285.89
  4539.2  284.51  4547.6  280.44  4592.3  273.87  4787.8  273.11  4860.6  273.33
    4897  271.21  4910.9  273.45    4947  274.41    4978  274.72  4986.4  272.75
  4997.4  262.85  5000.1  262.35  5003.4  262.85  5011.6  264.31  5017.2  268.86
  5039.5  271.58  5045.1  273.95  5148.5  282.69  5179.3  287.77  5263.1  296.21
  5307.8  302.59  5313.4  304.78  5422.4  316.57  5451.3  318.98    5456  319.14
#Mann= 7 ,-1 , 0
    4338     .16       0  4787.8     .05       0    4947     .16       0
  4997.4     .07       0  5003.4     .16       0  5422.4      .1       0
  5451.3     .16       0
Bank Sta=4997.4,5003.4
XS Rating Curve= 0 ,0
Exp/Cntr=0.3,0.1

Type RM Length L Ch R = 1 ,9261    ,514,514,514
BEGIN DESCRIPTION:
UNT 165 IN UKCR 16.0
END DESCRIPTION:
XS GIS Cut Line= 3
      3690549.62     10545310.15      3690399.61     10545710.19
      3690299.61     10546310.17
#Sta/Elev= 30
  4553.9  317.97  4599.3  312.62  4624.2  306.08  4654.5  302.08  4660.7  299.28
  4671.4  297.96  4679.4  294.26  4692.8   292.1  4709.7  285.47  4746.2  278.05
  4795.1  273.48  4874.3   271.9  4917.1  267.02  4941.1  271.02    4966  272.22
  4983.7  270.59  4991.3  264.11  4998.4  262.18  5001.2  261.68  5004.4  262.18
  5014.1  264.34  5021.7  268.85    5042  272.94  5112.9  271.97  5305.6  291.79
  5434.8  301.04  5495.6  302.01  5500.7  300.61  5556.5   308.5  5589.4  311.36
#Mann= 3 ,-1 , 0
  4553.9     .16       0  4998.4     .07       0  5004.4     .16       0
Bank Sta=4998.4,5004.4
XS Rating Curve= 0 ,0
Exp/Cntr=0.3,0.1

Type RM Length L Ch R = 1 ,8747    ,522,522,522
BEGIN DESCRIPTION:
UNT 165 IN UKCR 15.0
END DESCRIPTION:
XS GIS Cut Line= 3
      3690549.57     10545260.21      3690149.61     10545460.19
      3689849.59     10546160.23
#Sta/Elev= 30
  4537.3  319.92  4618.3  315.53  4693.8   307.2  4783.2  299.85    4814  293.71
  4836.3  284.53  4858.7  279.16  4881.1  277.69  4886.6  275.85  4917.4  274.72
  4931.4  271.96  4970.5  271.14  4987.2  268.67    4999  261.18  5003.2  260.12
    5006  259.62  5009.2  260.12    5028  270.01  5038.9  271.49  5112.6  271.13
  5245.6   270.5  5441.1  275.35  5495.8  277.85  5550.2  289.38  5561.1  293.38
  5648.1  300.72  5660.8  303.43  5702.5   306.2    5739  310.76  5746.1  311.03
#Mann= 6 ,-1 , 0
  4537.3     .16       0  5003.2     .07       0  5009.2     .16       0
  5112.6     .05       0  5441.1     .16       0    5739     .05       0
Bank Sta=5003.2,5009.2
XS Rating Curve= 0 ,0
Exp/Cntr=0.3,0.1

Type RM Length L Ch R = 1 ,8225    ,466,466,466
BEGIN DESCRIPTION:
UNT 165 IN UKCR 14.0
END DESCRIPTION:
XS GIS Cut Line= 3
       3689799.6     10544960.21      3689699.61     10545510.19
       3689449.6     10545960.21
#Sta/Elev= 30
  4426.7  316.58  4497.8  309.51  4565.2  297.83  4570.2  298.44  4589.3  294.39
  4599.5  290.09  4609.6  288.42  4618.5  284.24  4623.6  285.59  4640.1  280.05
    4677  273.74  4730.4     268  4788.8  266.57  4871.7   267.4  4965.4  269.11
  4975.5  268.39  4983.2  263.37  4988.6  263.37  4993.7  259.32  4996.4  258.92
  4999.2  258.42  5002.4  258.92  5021.2  263.51  5048.7  263.64  5080.6  269.05
  5191.6  276.75  5420.4  297.19  5427.3   299.5  5443.3  300.73  5500.5  310.38
#Mann= 6 ,-1 , 0
  4426.7     .16       0  4730.4    .055       0  4871.7     .16       0
  4996.4     .07       0  5002.4     .16       0  5048.7     .05       0
Bank Sta=4996.4,5002.4
XS Rating Curve= 0 ,0
Exp/Cntr=0.3,0.1

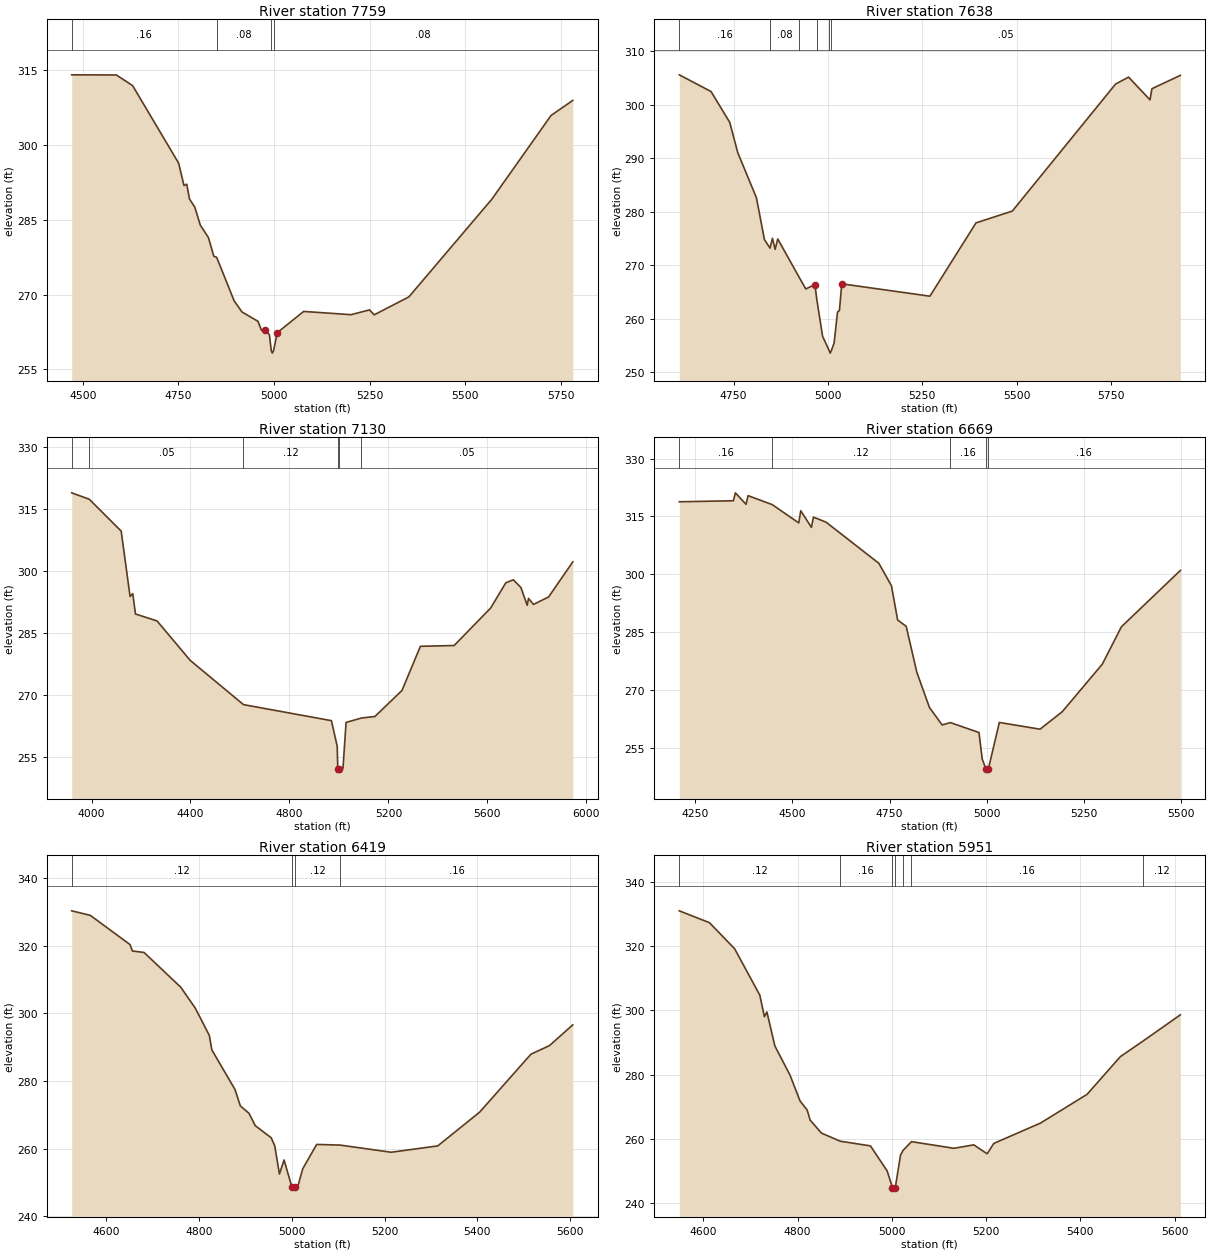
Type RM Length L Ch R = 1 ,7759    ,121,121,121
BEGIN DESCRIPTION:
UNT 165 IN UKCR 13.0
END DESCRIPTION:
XS GIS Cut Line= 4
      3689767.13     10544792.71      3689480.69     10545086.96
      3689436.42     10545279.67      3689347.88     10545974.98
#Sta/Elev= 30
  4471.3  314.01    4588  313.98  4630.4  311.85  4750.6  296.33  4764.7  291.83
  4771.9   292.1  4778.9  289.17    4793   287.5  4807.2  283.93  4828.5  281.42
  4842.6  277.67  4850.1  277.46  4895.5  268.78    4916  266.53    4958  264.64
  4967.3  262.84  4977.6  262.91  4987.9  261.95  4992.7  258.77  4995.5  258.27
  4998.7  258.77  5008.4  262.37  5077.4  266.62  5201.2  265.97  5249.4  266.93
  5261.7  265.94  5352.4  269.54  5569.1   289.1  5723.8  305.87  5780.6  308.89
#Mann= 4 ,-1 , 0
  4471.3     .16       0  4850.1     .08       0  4992.7     .05       0
  4998.7     .08       0
Bank Sta=4977.6,5008.4
XS Rating Curve= 0 ,0
Exp/Cntr=0.3,0.1

Type RM Length L Ch R = 1 ,7638    ,508,508,508
BEGIN DESCRIPTION:
Mapping XS f07aacb7
END DESCRIPTION:
XS GIS Cut Line= 5
      3689598.53     10544850.08      3689359.78     10545088.83
      3689312.03     10545353.59      3689238.25     10545453.41
      3689303.19     10546046.56
#Sta/Elev= 30
  4606.1  305.55  4690.3  302.43  4739.8  296.67    4761  291.03  4810.5  282.59
  4831.7  274.78  4846.5   273.2  4852.9  275.03    4860  272.96    4867   274.9
  4923.8  267.74  4941.2  265.57  4965.4  266.39  4970.7   263.5  4985.8  256.72
  5003.1  254.09  5005.8  253.59  5009.1  254.09  5016.3  255.47  5025.3  261.27
  5030.3  261.53  5036.6  266.53  5270.1  264.22  5392.2  277.91  5488.4  280.11
    5762  303.83  5796.4  305.12  5853.2  300.88  5858.3  302.96  5933.6  305.45
#Mann= 6 ,-1 , 0
  4606.1     .16       0  4846.5     .08       0  4923.8     .16       0
  4970.7     .05       0  5003.1     .03       0  5009.1     .05       0
Bank Sta=4965.4,5036.6
XS Rating Curve= 0 ,0
Exp/Cntr=0.3,0.1

Type RM Length L Ch R = 1 ,7130    ,461,461,461
BEGIN DESCRIPTION:
UNT 165 IN UKCR 12.0
END DESCRIPTION:
XS GIS Cut Line= 3
       3689455.7      10544224.1      3688969.59     10545335.21
      3689247.36     10546099.08
#Sta/Elev= 30
  3919.9  318.85  3991.1  317.29  4119.9  309.59  4155.8  293.79  4166.7  294.46
  4177.6  289.54  4264.9  287.85    4399  278.31  4614.3  267.61  4969.7  263.73
  4993.1  257.55  4995.6  252.02  4998.3  251.52  5001.6  252.02  5016.5  252.22
    5029   263.3  5091.3  264.37  5145.4  264.73    5255  271.03  5329.5  281.72
  5465.9  281.91  5613.5  290.98  5674.7  297.08  5705.3  297.81  5735.9  295.93
  5761.2  291.64  5766.5  293.31  5786.5  291.85  5847.6  293.65  5945.5  302.14
#Mann= 6 ,-1 , 0
  3919.9     .16       0  3991.1     .05       0  4614.3     .12       0
  4995.6     .07       0  5001.6     .12       0  5091.3     .05       0
Bank Sta=4995.6,5001.6
XS Rating Curve= 0 ,0
Exp/Cntr=0.3,0.1

Type RM Length L Ch R = 1 ,6669    ,250,250,250
BEGIN DESCRIPTION:
UNT 165 IN UKCR 11.0
END DESCRIPTION:
XS GIS Cut Line= 2
      3688926.19     10544293.51      3688544.56     10545525.13
#Sta/Elev= 30
  4208.7  318.79  4347.9  319.05  4353.1  321.11  4380.5  318.13  4385.7  320.38
  4447.9  318.05  4516.1  313.31  4521.3  316.46  4548.7  312.15  4553.9  314.81
  4586.5  313.49  4722.2  302.83  4754.7  296.99  4770.6  288.11  4792.6  286.48
  4819.9  274.57  4852.5   265.4  4885.1  260.88  4906.3  261.49  4979.9  258.92
  4988.2  252.06  4997.9   249.4  5000.6   248.9  5003.9   249.4  5032.3  261.53
    5137  259.78  5194.2  264.32  5297.2  276.64  5346.4  286.35  5498.1  300.97
#Mann= 5 ,-1 , 0
  4208.7     .16       0  4447.9     .12       0  4906.3     .16       0
  4997.9     .07       0  5003.9     .16       0
Bank Sta=4997.9,5003.9
XS Rating Curve= 0 ,0
Exp/Cntr=0.3,0.1

Type RM Length L Ch R = 1 ,6419    ,468,468,468
BEGIN DESCRIPTION:
UNT 165 IN UKCR 10.0
END DESCRIPTION:
XS GIS Cut Line= 3
      3688699.61     10544410.17      3688549.61     10544810.19
      3688499.61     10545460.15
#Sta/Elev= 30
  4526.3  330.38  4566.4  329.03  4651.8   320.4  4657.1  318.49  4682.1  318.05
  4761.3  307.74  4792.4  301.58  4822.7  293.47    4828  289.23  4877.9  277.49
  4889.4  272.64  4908.1  270.43  4921.5  266.79    4956  263.18  4963.5  260.83
  4973.6  252.47  4983.6  256.62  5000.7  248.49  5003.4  247.99  5006.7  248.49
  5013.7  249.01  5023.7  253.98  5053.8  261.22  5104.1  261.03  5214.3  258.91
  5314.6  260.79  5404.8  270.78  5515.2  287.93  5555.3  290.49  5605.4  296.63
#Mann= 4 ,-1 , 0
  4526.3     .12       0  5000.7     .07       0  5006.7     .12       0
  5104.1     .16       0
Bank Sta=5000.7,5006.7
XS Rating Curve= 0 ,0
Exp/Cntr=0.3,0.1

Type RM Length L Ch R = 1 ,5951    ,832,832,832
BEGIN DESCRIPTION:
UNT 165 IN UKCR 9.0
END DESCRIPTION:
XS GIS Cut Line= 3
      3688349.61     10544310.19      3688199.61     10544710.19
       3687749.6     10545160.19
#Sta/Elev= 30
  4548.8   330.9  4612.9  327.21  4666.3  319.11  4719.7  304.69  4729.5  297.98
  4734.8  299.47  4751.7  288.89  4783.8  279.85  4805.1  271.81  4820.2  269.01
  4826.5  265.88  4850.5  261.82  4890.4   259.3  4954.6  257.84  4990.1  250.03
  5001.3   244.9    5004   244.4  5007.3   244.9  5018.4  254.95  5023.6  256.42
  5041.7  259.16  5131.6  257.09    5174  258.16  5202.3  255.38  5216.4  258.61
  5315.4  264.92  5414.4  273.86  5485.1  285.59  5532.6  290.36  5612.4  298.58
#Mann= 7 ,-1 , 0
  4548.8     .12       0  4890.4     .16       0  5001.3     .07       0
  5007.3     .16       0  5023.6     .12       0  5041.7     .16       0
  5532.6     .12       0
Bank Sta=5001.3,5007.3
XS Rating Curve= 0 ,0
Exp/Cntr=0.3,0.1

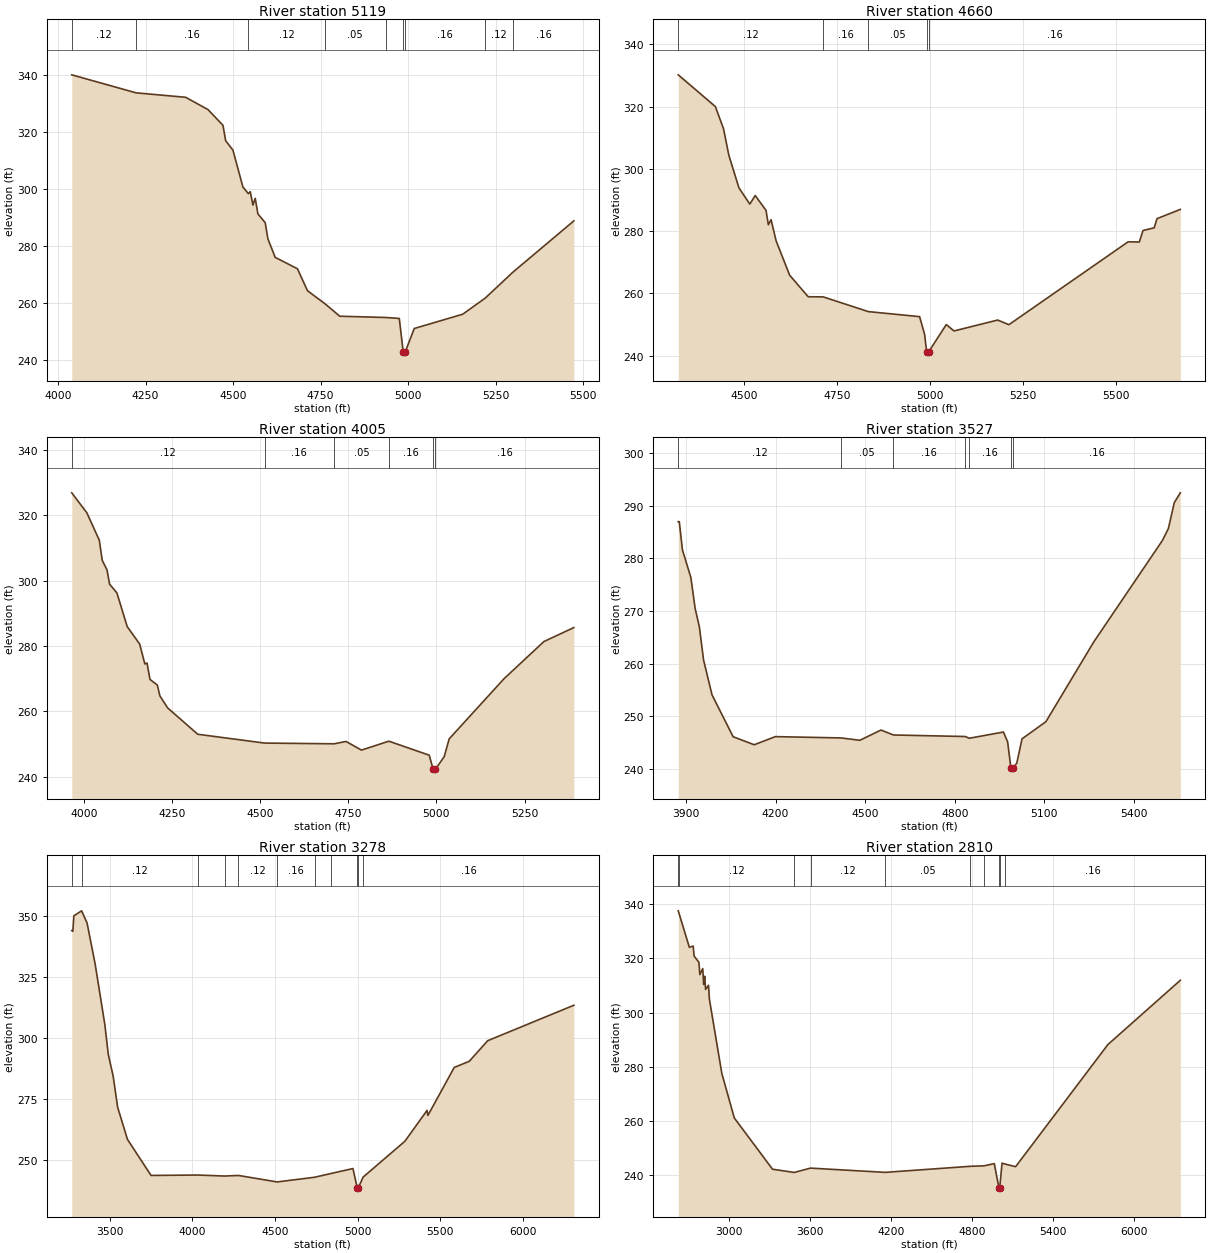
Type RM Length L Ch R = 1 ,5119    ,459,459,459
BEGIN DESCRIPTION:
UNT 165 IN UKCR 7.0
END DESCRIPTION:
XS GIS Cut Line= 3
       3688474.8      10543685.9      3687676.18     10544371.67
      3687499.63     10544710.15
#Sta/Elev= 30
  4039.1  340.01  4222.9  333.68  4364.6  332.12  4428.3   327.8  4471.1  322.29
  4478.7  316.89  4499.6  313.54  4528.1   300.6  4543.6  298.27    4549  298.98
  4556.7  294.26  4563.2  296.64  4570.9  291.16  4591.8  288.08  4599.4  282.43
  4620.3   275.9    4684  271.89  4712.5  264.19  4762.2  259.65  4804.7  255.23
  4935.7  254.79  4974.8  254.45    4986  242.77  4988.8  242.27    4992  242.77
  5017.6  250.92  5156.1  255.94  5220.1  261.57  5299.7  270.73  5473.5  288.71
#Mann= 9 ,-1 , 0
  4039.1     .12       0  4222.9     .16       0  4543.6     .12       0
  4762.2     .05       0  4935.7     .16       0    4986     .07       0
    4992     .16       0  5220.1     .12       0  5299.7     .16       0
Bank Sta=4986,4992
XS Rating Curve= 0 ,0
Exp/Cntr=0.3,0.1

Type RM Length L Ch R = 1 ,4660    ,655,655,655
BEGIN DESCRIPTION:
UNT 165 IN UKCR 6.0
END DESCRIPTION:
XS GIS Cut Line= 3
       3687899.6     10543460.21      3687449.61     10544060.19
      3687399.61     10544660.23
#Sta/Elev= 30
  4322.4   330.2  4422.4  320.01  4444.3  312.92  4458.8  304.33  4485.9  293.91
  4515.1   288.7  4529.7  291.44  4558.8  286.69  4565.1  282.07  4572.4   283.7
  4585.9  276.94  4622.4  265.88  4672.4  258.95  4712.7  258.91  4834.4  254.18
  4972.4  252.56  4985.9  246.87  4991.3  241.35    4994  240.85  4997.3  241.35
  5044.3  250.02  5065.1  247.97  5182.8  251.47  5212.9  249.98    5534  276.59
  5564.1  276.53  5574.1  280.22  5604.2  281.08  5611.7  284.02  5674.5     287
#Mann= 5 ,-1 , 0
  4322.4     .12       0  4712.7     .16       0  4834.4     .05       0
  4991.3     .07       0  4997.3     .16       0
Bank Sta=4991.3,4997.3
XS Rating Curve= 0 ,0
Exp/Cntr=0.3,0.1

Type RM Length L Ch R = 1 ,4005    ,478,478,478
BEGIN DESCRIPTION:
UNT 165 IN UKCR 5.0
END DESCRIPTION:
XS GIS Cut Line= 3
      3687849.61     10543410.19      3687049.61     10544010.19
      3686749.58     10544310.22
#Sta/Elev= 30
  3965.6  326.88  4008.3  320.78  4043.7  312.39  4052.1  306.21  4065.6   303.3
  4072.9  298.95  4093.7  296.26  4122.9  285.95  4158.3  280.62  4172.9  274.55
  4179.1  274.82  4187.5   269.8  4208.3   268.1  4215.6  264.77  4237.5  261.11
  4322.9  253.04  4512.5  250.34  4709.8  250.12  4743.7  250.83  4787.5  248.19
  4865.2  250.92  4979.7  246.63  4990.9  242.26  4993.6  241.76  4996.9  242.26
  5022.2   246.2  5036.3  251.63  5191.9  270.03    5305  281.39  5389.9  285.67
#Mann= 6 ,-1 , 0
  3965.6     .12       0  4512.5     .16       0  4709.8     .05       0
  4865.2     .16       0  4990.9     .07       0  4996.9     .16       0
Bank Sta=4990.9,4996.9
XS Rating Curve= 0 ,0
Exp/Cntr=0.3,0.1

Type RM Length L Ch R = 1 ,3527    ,249,249,249
BEGIN DESCRIPTION:
UNT 165 IN UKCR 4.0
END DESCRIPTION:
XS GIS Cut Line= 3
      3687449.58     10543060.22      3686649.61     10543860.19
      3686649.61     10544410.16
#Sta/Elev= 30
  3874.2     287  3877.7     287  3888.3  281.63  3916.6  276.36  3930.7  270.53
  3944.9  267.02    3959  260.71  3987.3  254.08    4058  246.11  4128.7  244.58
  4199.4  246.13  4419.3  245.88  4482.3  245.43    4553  247.38    4595  246.44
  4835.3  246.15  4848.8  245.82  4963.1     247  4977.2  245.16  4988.4  240.07
  4991.1  239.57  4994.4  240.07    5008  241.11  5025.5  245.71  5105.5  248.97
  5265.5  264.12  5495.5  283.41  5515.5  285.69  5535.5  290.64  5555.5  292.48
#Mann= 7 ,-1 , 0
  3874.2     .12       0  4419.3     .05       0    4595     .16       0
  4835.3     .05       0  4848.8     .16       0  4988.4     .07       0
  4994.4     .16       0
Bank Sta=4988.4,4994.4
XS Rating Curve= 0 ,0
Exp/Cntr=0.3,0.1

Type RM Length L Ch R = 1 ,3278    ,468,468,468
BEGIN DESCRIPTION:
Mapping XS e491283e
END DESCRIPTION:
XS GIS Cut Line= 4
      3687585.56     10542758.48      3686434.56     10543565.74
      3686413.72     10544175.12      3686569.95      10545185.4
#Sta/Elev= 30
  3269.6  343.94    3276  343.67  3282.1  349.99  3329.1  352.04  3362.3  347.03
  3411.2  330.22  3469.5  305.57  3490.4  293.34  3520.1  284.39  3547.1  271.67
  3606.4  258.52  3749.3  243.73  4033.2   243.9  4194.3  243.48  4277.8  243.73
    4512  241.07  4738.4  242.98  4836.4   244.5  4970.9  246.55  4997.1  238.63
  4999.9  238.13  5003.1  238.63  5032.5  243.05  5285.2  257.72  5419.3  270.35
  5424.4  268.29  5583.8  287.93  5674.9  290.46  5786.2  298.88  6307.5  313.39
#Mann= 11 ,-1 , 0
  3269.6     .16       0  3329.1     .12       0  4033.2     .05       0
  4194.3     .16       0  4277.8     .12       0    4512     .16       0
  4738.4     .12       0  4836.4     .05       0  4997.1     .03       0
  5003.1     .05       0  5032.5     .16       0
Bank Sta=4997.1,5003.1
XS Rating Curve= 0 ,0
Exp/Cntr=0.3,0.1

Type RM Length L Ch R = 1 ,2810    ,933,933,933
BEGIN DESCRIPTION:
UNT 165 IN UKCR 3.0
END DESCRIPTION:
XS GIS Cut Line= 4
      3687455.42     10542289.68      3685981.43     10543654.28
      3686054.35     10544373.03      3686356.44     10545310.55
#Sta/Elev= 30
  2625.6  337.55  2631.8  336.58  2707.9  324.07  2736.2  324.55    2743  320.86
  2778.8  318.51  2785.6     314  2807.1  316.23  2813.9  310.36  2821.3  313.39
  2828.1  308.51  2849.6  310.07  2856.4  304.91  2948.3   277.5  3040.7  261.06
  3323.6  242.14  3484.3  240.95  3604.6  242.55  4157.5  240.98  4788.7  243.22
  4887.7  243.38  4964.9  244.21  4999.1  235.29  5001.8  234.79  5005.1  235.29
  5022.2  244.39  5041.8  244.08  5122.7  243.08  5805.5  288.16  6341.7   311.9
#Mann= 10 ,-1 , 0
  2625.6     .16       0  2631.8     .12       0  3484.3     .05       0
  3604.6     .12       0  4157.5     .05       0  4788.7     .16       0
  4887.7     .12       0  4999.1     .07       0  5005.1     .12       0
  5041.8     .16       0
Bank Sta=4999.1,5005.1
XS Rating Curve= 0 ,0
Exp/Cntr=0.3,0.1

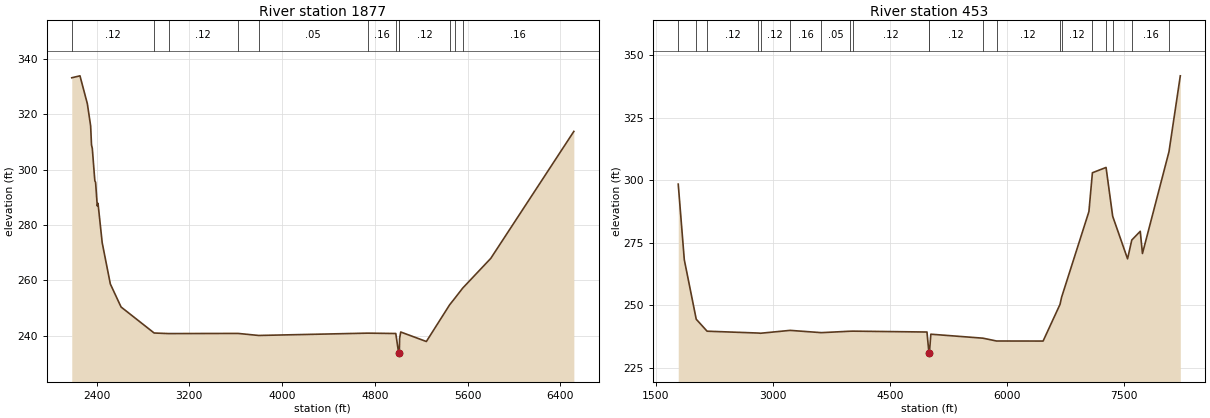
Type RM Length L Ch R = 1 ,1877    ,1424,1424,1424
BEGIN DESCRIPTION:
UNT 165 IN UKCR 2.0
END DESCRIPTION:
XS GIS Cut Line= 3
      3687299.57     10542260.22      3685341.11     10543972.36
      3686148.41     10545500.14
#Sta/Elev= 30
  2186.6  333.14  2257.3  333.84  2320.9  323.78  2349.3  315.78  2356.9  308.84
  2363.6  307.65  2385.4  295.95    2392  295.39  2406.3  286.86  2412.9  287.78
    2449  273.54  2519.2  258.65  2611.6  250.34    2897  240.94  3021.5  240.73
  3620.1  240.79  3798.1  240.05  4737.1  240.89  4980.6  240.76  5004.8  233.81
  5007.5  233.31  5010.8  233.81  5013.4  238.93    5023   241.3  5244.2  237.87
    5445  251.13  5490.2  253.52  5557.7  257.17  5799.6   267.9  6515.9  313.76
#Mann= 12 ,-1 , 0
  2186.6     .12       0    2897     .05       0  3021.5     .12       0
  3620.1     .16       0  3798.1     .05       0  4737.1     .16       0
  4980.6     .12       0  5004.8     .07       0  5010.8     .12       0
    5445     .16       0  5490.2     .12       0  5557.7     .16       0
Bank Sta=5004.8,5010.8
XS Rating Curve= 0 ,0
Exp/Cntr=0.3,0.1

Type RM Length L Ch R = 1 ,453     ,0,0,0
BEGIN DESCRIPTION:
UNT 165 IN UKCR 1.0
END DESCRIPTION:
XS GIS Cut Line= 4
      3686799.58     10542260.22      3684387.55      10544745.8
      3684411.43     10545141.45       3686304.2     10546891.61
#Sta/Elev= 30
  1785.5  298.47  1863.3  268.22  2016.3  244.45  2155.5  239.66  2812.8  238.92
  2841.5  238.84  3219.9  239.99  3620.4  239.08  3983.7  239.64  4023.6  239.68
  4974.9  239.33  5000.2  230.99    5003  230.49  5006.2  230.99  5024.4  238.46
    5692  236.87    5867  235.74    6464  235.72  6680.6  250.37  6701.1  253.23
  7051.4   287.5  7096.2  303.03  7271.2  305.15  7356.2  285.63  7546.9   268.6
  7601.1  276.12  7709.7  279.61    7738  270.73  8077.9  311.42  8223.3  341.79
#Mann= 20 ,-1 , 0
  1785.5     .12       0  2016.3     .05       0  2155.5     .12       0
  2812.8     .16       0  2841.5     .12       0  3219.9     .16       0
  3620.4     .05       0  3983.7     .16       0  4023.6     .12       0
  5000.2     .07       0  5006.2     .12       0    5692     .16       0
    5867     .12       0  6680.6     .16       0  6701.1     .12       0
  7096.2     .05       0  7271.2     .16       0  7356.2     .12       0
  7601.1     .16       0  8077.9     .05       0
Bank Sta=5000.2,5006.2
XS Rating Curve= 0 ,0
Exp/Cntr=0.3,0.1

Chan Stop Cuts=-1
Use User Specified Reach Order=0
Composite Channel Slope=5

--- UNT 165 IN UKCR.g02 (geometry) ---

Geom Title=ARC
Program Version=4.10

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
River Reach=UNT 165 IN UKCR ,Reach-1

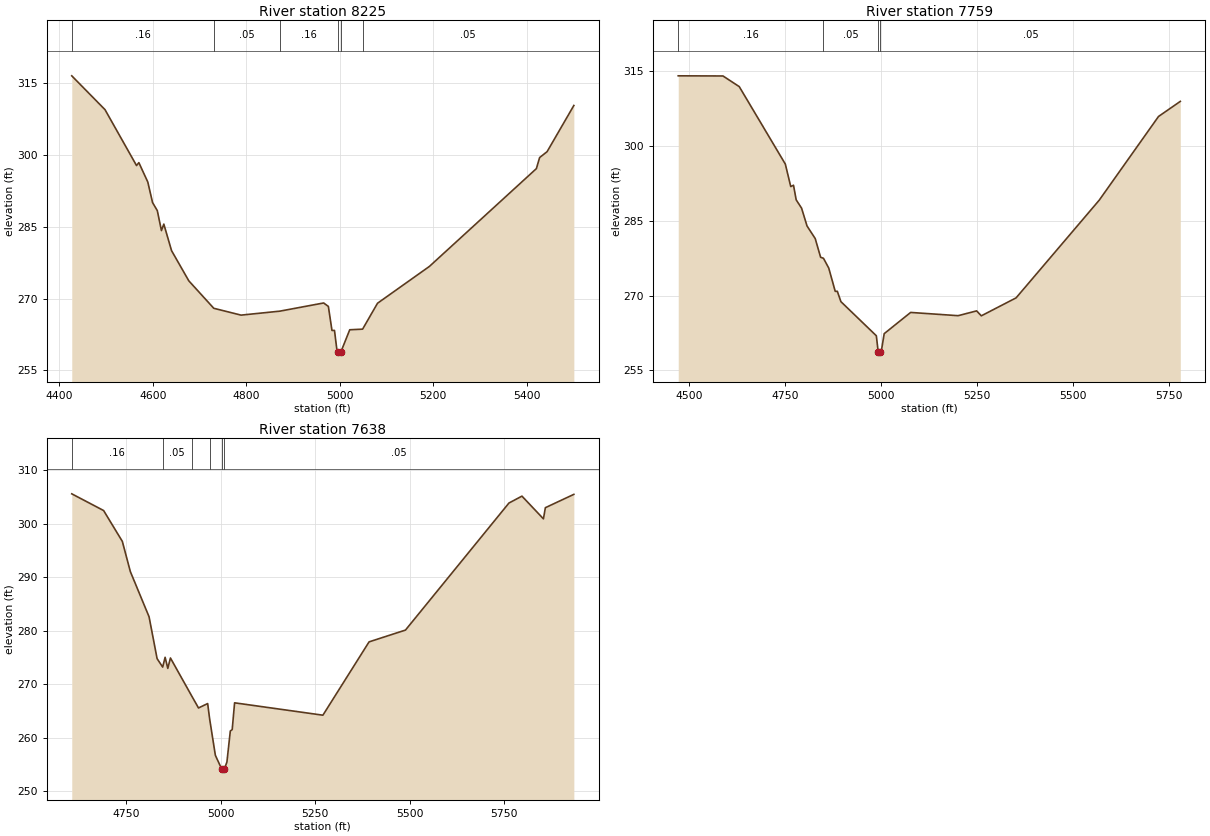
Type RM Length L Ch R = 1 ,8225    ,466,466,466
BEGIN DESCRIPTION:
UNT 165 IN UKCR 14.0
END DESCRIPTION:
XS GIS Cut Line= 3
       3689799.6     10544960.21      3689699.61     10545510.19
       3689449.6     10545960.21
#Sta/Elev= 30
  4426.7  316.58  4497.8  309.51  4565.2  297.83  4570.2  298.44  4589.3  294.39
  4599.5  290.09  4609.6  288.42  4618.5  284.24  4623.6  285.59  4640.1  280.05
    4677  273.74  4730.4     268  4788.8  266.57  4871.7   267.4  4965.4  269.11
  4975.5  268.39  4983.2  263.37  4988.6  263.37  4993.7  259.32  4996.4  258.92
  4999.2  258.42  5002.4  258.92  5021.2  263.51  5048.7  263.64  5080.6  269.05
  5191.6  276.75  5420.4  297.19  5427.3   299.5  5443.3  300.73  5500.5  310.38
#Mann= 6 ,-1 , 0
  4426.7     .16       0  4730.4     .05       0  4871.7     .16       0
  4996.4     .07       0  5002.4     .16       0  5048.7     .05       0
Bank Sta=4996.4,5002.4
XS Rating Curve= 0 ,0
Exp/Cntr=0.3,0.1

Type RM Length L Ch R = 1 ,7759    ,121,121,121
BEGIN DESCRIPTION:
UNT 165 IN UKCR 13.0
END DESCRIPTION:
XS GIS Cut Line= 4
      3689767.13     10544792.71      3689480.69     10545086.96
      3689436.42     10545279.67      3689347.88     10545974.98
#Sta/Elev= 30
  4471.3  314.01    4588  313.98  4630.4  311.85  4750.6  296.33  4764.7  291.83
  4771.9   292.1  4778.9  289.17    4793   287.5  4807.2  283.93  4828.5  281.42
  4842.6  277.67  4850.1  277.46  4863.8  275.51  4880.7  270.85  4886.2  270.85
  4895.5  268.78  4987.9  261.95  4992.7  258.77  4995.5  258.27  4998.7  258.77
  5000.8   258.8  5008.4  262.37  5077.4  266.62  5201.2  265.97  5249.4  266.93
  5261.7  265.94  5352.4  269.54  5569.1   289.1  5723.8  305.87  5780.6  308.89
#Mann= 4 ,-1 , 0
  4471.3     .16       0  4850.1     .05       0  4992.7     .03       0
  4998.7     .05       0
Bank Sta=4992.7,4998.7
XS Rating Curve= 0 ,0
Exp/Cntr=0.3,0.1

Type RM Length L Ch R = 1 ,7638    ,508,508,508
BEGIN DESCRIPTION:
Mapping XS f07aacb7
END DESCRIPTION:
XS GIS Cut Line= 5
      3689598.53     10544850.08      3689359.78     10545088.83
      3689312.03     10545353.59      3689238.25     10545453.41
      3689303.19     10546046.56
#Sta/Elev= 30
  4606.1  305.55  4690.3  302.43  4739.8  296.67    4761  291.03  4810.5  282.59
  4831.7  274.78  4846.5   273.2  4852.9  275.03    4860  272.96    4867   274.9
  4923.8  267.74  4941.2  265.57  4965.4  266.39  4970.7   263.5  4985.8  256.72
  5003.1  254.09  5005.8  253.59  5009.1  254.09  5016.3  255.47  5025.3  261.27
  5030.3  261.53  5036.6  266.53  5270.1  264.22  5392.2  277.91  5488.4  280.11
    5762  303.83  5796.4  305.12  5853.2  300.88  5858.3  302.96  5933.6  305.45
#Mann= 6 ,-1 , 0
  4606.1     .16       0  4846.5     .05       0  4923.8     .16       0
  4970.7     .05       0  5003.1     .03       0  5009.1     .05       0
Bank Sta=5003.1,5009.1
XS Rating Curve= 0 ,0
Exp/Cntr=0.3,0.1