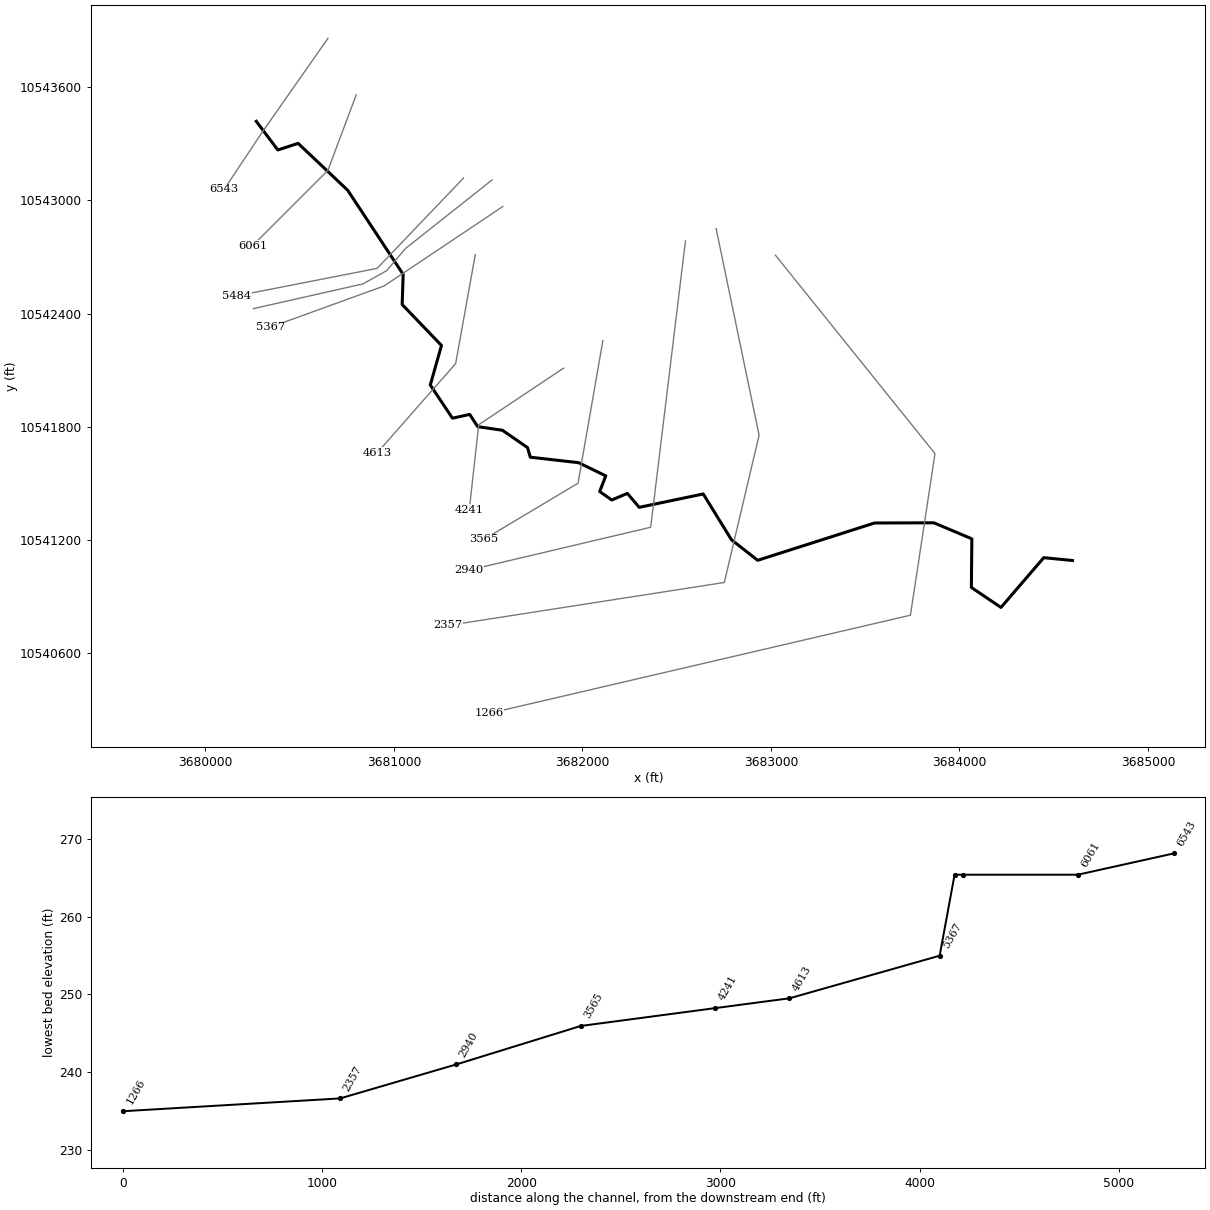
--- UNT 170 IN UKCR.prj (project) ---

Proj Title=UNT 170 IN UKCR Base Level Engineering
Current Plan=p01
Default Exp/Contr=0.3,0.1
English Units
Geom File=g01
Flow File=f01
Plan File=p01
BEGIN DESCRIPTION:
UNT 170 IN UKCR
END DESCRIPTION:

--- UNT 170 IN UKCR.p01 (plan) ---

Plan Title=Multiple Run
Short Identifier=Multiple
Geom File=g01
Flow File=f01
Subcritical Flow
K Sum by GR= 0
Std Step Tol= 0.01
Critical Tol= 0.01
Num of Std Step Trials= 20
Max Error Tol= 0.3
Flow Tol Ratio= 0.001
Split Flow NTrial= 30
Split Flow Tol= 0.02
Split Flow Ratio= 0.02
Log Output Level= 0
Friction Slope Method= 1
Unsteady Friction Slope Method= 2
Unsteady Bridges Friction Slope Method= 1
Parabolic Critical Depth
Global Vel Dist=  1 , 1 , 1
Global Log Level= 0
CheckData=True
Encroach Param= -1, 0, 0, 0
BEGIN DESCRIPTION:
Multiple Run
END DESCRIPTION:

--- UNT 170 IN UKCR.f01 (steady flow) ---

Flow Title=Multiple
Number of Profiles=7
Profile Names=10-year,25-year,50-year,1pct_min,100-year,1pct_plu,500-year
River Rch & RM= UNT 170 IN UKCR,Reach-1,6543
     571     780     955     859    1162    1572    1729
River Rch & RM= UNT 170 IN UKCR,Reach-1,6061
     710     977    1201    1084    1467    1983    2197
Boundary for River Rch & Prof#=UNT 170 IN UKCR,Reach-1,1
Up Type=0
Dn Type=3
Dn Slope=0.005
Boundary for River Rch & Prof#=UNT 170 IN UKCR,Reach-1,2
Up Type=0
Dn Type=3
Dn Slope=0.005
Boundary for River Rch & Prof#=UNT 170 IN UKCR,Reach-1,3
Up Type=0
Dn Type=3
Dn Slope=0.005
Boundary for River Rch & Prof#=UNT 170 IN UKCR,Reach-1,4
Up Type=0
Dn Type=3
Dn Slope=0.005
Boundary for River Rch & Prof#=UNT 170 IN UKCR,Reach-1,5
Up Type=0
Dn Type=3
Dn Slope=0.005
Boundary for River Rch & Prof#=UNT 170 IN UKCR,Reach-1,6
Up Type=0
Dn Type=3
Dn Slope=0.005
Boundary for River Rch & Prof#=UNT 170 IN UKCR,Reach-1,7
Up Type=0
Dn Type=3
Dn Slope=0.005

--- UNT 170 IN UKCR.g01 (geometry) ---

Geom Title=Existing Conditions

River Reach=UNT 170 IN UKCR,Reach-1
Reach XY= 30
      3680269.50     10543420.00      3680383.75     10543268.00
      3680491.50     10543303.00      3680754.75     10543054.00
      3681048.75     10542608.00      3681043.50     10542448.00
      3681252.00     10542231.00      3681192.75     10542021.00
      3681310.25     10541845.00      3681401.75     10541865.00
      3681444.50     10541800.00      3681575.25     10541781.00
      3681708.50     10541689.00      3681723.25     10541638.00
      3681979.25     10541609.00      3682123.75     10541539.00
      3682091.25     10541456.00      3682155.50     10541411.00
      3682238.25     10541446.00      3682301.00     10541372.00
      3682640.75     10541443.00      3682790.50     10541200.00
      3682929.50     10541091.00      3683549.75     10541289.00
      3683864.25     10541290.00      3684065.75     10541205.00
      3684063.25     10540947.00      3684220.25     10540841.00
      3684447.25     10541105.00      3684599.50     10541090.00

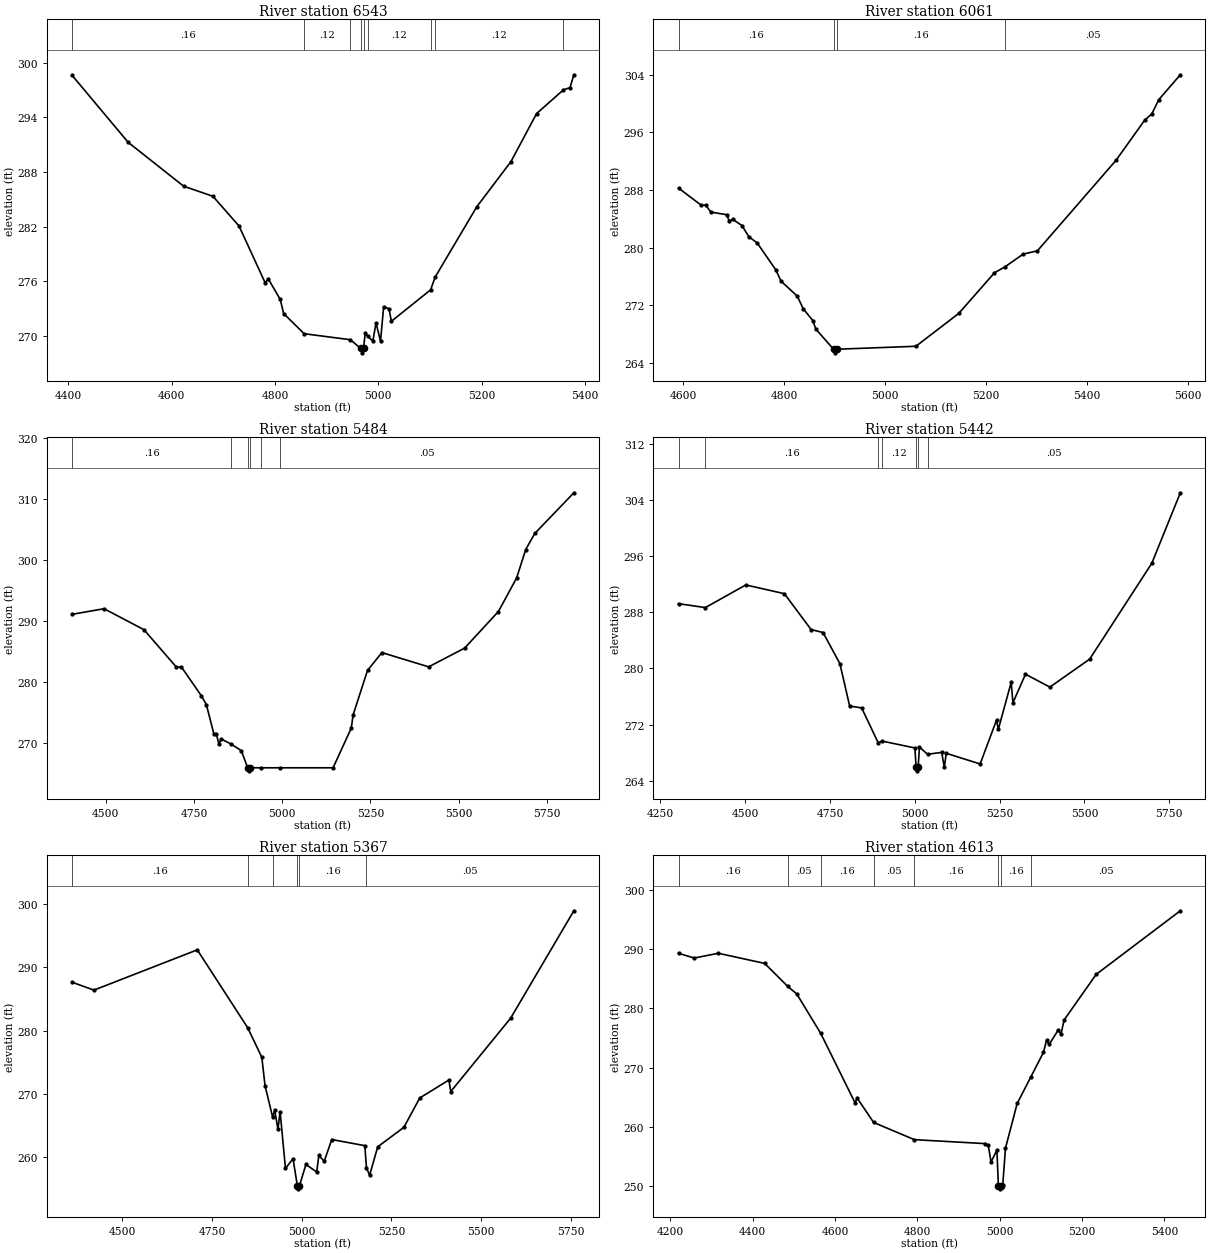
Type RM Length L Ch R = 1,6543,482,482,482
BEGIN DESCRIPTION:
UNT 170 IN UKCR 7.0
END DESCRIPTION:
XS GIS Cut Line= 3
      3680649.61     10543860.19      3680299.61     10543360.19
      3680099.60     10543060.17
#Sta/Elev= 30
  4407.5  298.62  4516.1  291.26  4623.3  286.45  4680.0  285.34  4730.5  282.08
  4781.1  275.84  4787.2  276.27  4810.3  274.01  4816.9  272.46  4856.5  270.25
  4946.0  269.59  4965.6  268.65  4968.3  268.15  4971.6  268.65  4974.7  270.37
  4979.6  269.96  4989.5  269.44  4995.6  271.44  5004.3  269.43  5010.4  273.22
  5020.8  272.98  5025.3  271.61  5101.3  275.07  5109.8  276.45  5190.6  284.19
  5256.7  289.15  5306.3  294.42  5358.3  297.03  5370.9  297.27  5378.4  298.68
#Mann=9,-1,0
  4407.5    0.16       0  4856.5    0.12       0  4946.0    0.16       0
  4965.6    0.07       0  4971.6    0.16       0  4979.6    0.12       0
  5101.3    0.16       0  5109.8    0.12       0  5358.3    0.16       0
Bank Sta=4965.6,4971.6
Exp/Cntr=0.3,0.1

Type RM Length L Ch R = 1,6061,577,577,577
BEGIN DESCRIPTION:
UNT 170 IN UKCR 6.0
END DESCRIPTION:
XS GIS Cut Line= 3
      3680799.62     10543560.23      3680649.61     10543160.19
      3680249.63     10542760.21
#Sta/Elev= 30
  4591.4  288.26  4636.8  285.86  4644.8  285.92  4655.5  284.93  4686.7  284.57
  4692.0  283.65  4698.2  283.94  4716.9  283.07  4730.3  281.54  4747.2  280.64
  4783.7  276.94  4794.4  275.34  4826.4  273.27  4838.0  271.54  4857.6  269.84
  4862.9  268.71  4898.2  265.91  4900.9  265.41  4904.2  265.91  5061.1  266.32
  5145.9  270.88  5216.6  276.52  5236.9  277.32  5273.2  279.10  5301.5  279.56
  5457.0  292.11  5513.6  297.67  5527.8  298.55  5541.9  300.55  5584.3  303.98
#Mann=4,-1,0
  4591.4    0.16       0  4898.2    0.07       0  4904.2    0.16       0
  5236.9    0.05       0
Bank Sta=4898.2,4904.2
Exp/Cntr=0.3,0.1

Type RM Length L Ch R = 1,5484,42,42,42
BEGIN DESCRIPTION:
UNT 170 IN UKCR 5.0
END DESCRIPTION:
XS GIS Cut Line= 3
      3681368.89     10543118.91      3680910.56     10542639.75
      3680165.77     10542493.92
#Sta/Elev= 30
  4404.4  291.06  4495.0  291.98  4608.2  288.54  4700.0  282.41  4714.2  282.44
  4770.8  277.71  4785.0  276.27  4806.0  271.50  4813.3  271.42  4820.2  269.86
  4827.4  270.62  4855.2  269.79  4884.0  268.72  4902.1  265.91  4904.9  265.41
  4908.1  265.91  4941.2  265.91  4992.7  265.91  5144.1  265.91  5195.6  272.41
  5200.9  274.59  5241.7  281.87  5282.4  284.79  5414.9  282.45  5516.8  285.52
  5612.6  291.52  5664.1  297.01  5690.0  301.68  5715.6  304.31  5826.4  310.98
#Mann=6,-1,0
  4404.4    0.16       0  4855.2    0.05       0  4902.1   0.033       0
  4908.1    0.05       0  4941.2    0.12       0  4992.7    0.05       0
Bank Sta=4902.1,4908.1
Exp/Cntr=0.3,0.1

Type RM Length L Ch R = 1,5442,75,75,75
BEGIN DESCRIPTION:
Mapping XS a85cd7d3
END DESCRIPTION:
XS GIS Cut Line= 5
      3681519.90     10543108.48      3681061.12     10542745.15
      3680960.20     10542626.87      3680835.42     10542557.43
      3680254.46     10542426.24
#Sta/Elev= 30
  4303.6  289.23  4382.7  288.67  4501.9  291.90  4615.7  290.65  4694.3  285.54
  4729.5  285.12  4779.2  280.69  4808.0  274.64  4843.3  274.38  4891.8  269.44
  4904.7  269.64  5000.3  268.67  5003.9  265.91  5006.6  265.41  5009.9  265.91
  5013.7  268.80  5037.5  267.77  5079.3  268.04  5087.0  265.91  5092.7  267.91
  5192.6  266.39  5240.9  272.64  5246.1  271.31  5284.1  278.01  5289.3  275.12
  5326.3  279.18  5398.1  277.34  5515.5  281.33  5698.6  294.98  5782.7  305.03
#Mann=7,-1,0
  4303.6    0.05       0  4382.7    0.16       0  4891.8    0.05       0
  4904.7    0.12       0  5003.9    0.07       0  5009.9    0.12       0
  5037.5    0.05       0
Bank Sta=5003.9,5009.9
Exp/Cntr=0.3,0.1

Type RM Length L Ch R = 1,5367,754,754,754
BEGIN DESCRIPTION:
UNT 170 IN UKCR 4.0
END DESCRIPTION:
XS GIS Cut Line= 3
      3681577.23     10542967.88      3680947.02     10542546.00
      3680343.72     10542327.57
#Sta/Elev= 30
  4359.3  287.67  4420.3  286.42  4708.6  292.79  4849.1  280.49  4888.7  275.80
  4897.7  271.30  4918.8  266.36  4924.7  267.41  4933.7  264.41  4939.7  267.20
  4954.7  258.22  4975.8  259.76  4987.8  255.49  4990.5  254.99  4993.8  255.49
  5011.8  258.85  5041.8  257.65  5047.8  260.27  5062.8  259.35  5083.8  262.79
  5176.1  261.82  5180.6  258.34  5189.4  257.13  5212.1  261.64  5285.1  264.72
  5329.3  269.36  5410.6  272.20  5415.9  270.38  5582.9  281.98  5759.3  298.97
#Mann=6,-1,0
  4359.3    0.16       0  4849.1    0.05       0  4918.8    0.16       0
  4987.8    0.07       0  4993.8    0.16       0  5180.6    0.05       0
Bank Sta=4987.8,4993.8
Exp/Cntr=0.3,0.1

Type RM Length L Ch R = 1,4613,372,372,372
BEGIN DESCRIPTION:
UNT 170 IN UKCR 3.0
END DESCRIPTION:
XS GIS Cut Line= 3
      3681431.39     10542712.67      3681327.22     10542134.54
      3680910.56     10541660.59
#Sta/Elev= 30
  4220.0  289.30  4258.2  288.51  4316.8  289.31  4429.1  287.60  4485.1  283.72
  4507.0  282.45  4565.1  275.80  4648.6  264.05  4653.7  264.85  4693.8  260.72
  4792.8  257.82  4964.6  257.15  4972.2  256.86  4978.8  254.03  4993.1  256.06
  4996.7  250.01  4999.5  249.51  5002.7  250.01  5007.3  250.16  5013.9  256.38
  5042.4  263.95  5075.9  268.47  5106.2  272.57  5113.6  274.60  5120.2  273.93
  5142.0  276.34  5148.7  275.65  5156.3  278.04  5234.1  285.74  5438.5  296.49
#Mann=8,-1,0
  4220.0    0.16       0  4485.1    0.05       0  4565.1    0.16       0
  4693.8    0.05       0  4792.8    0.16       0  4996.7    0.07       0
  5002.7    0.16       0  5075.9    0.05       0
Bank Sta=4996.7,5002.7
Exp/Cntr=0.3,0.1

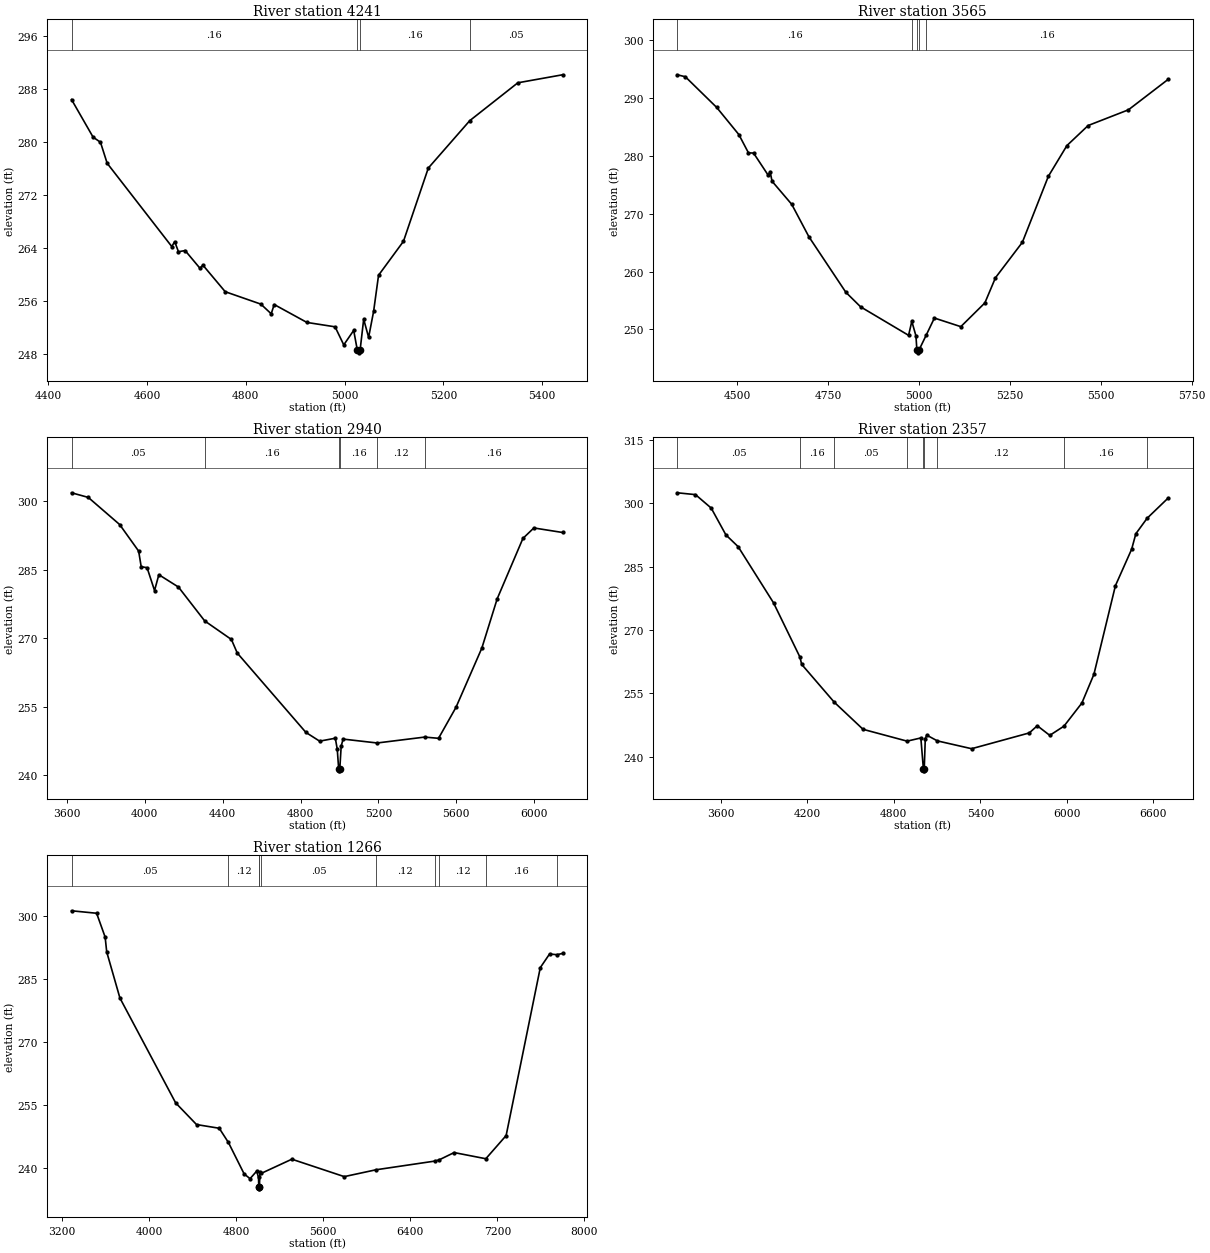
Type RM Length L Ch R = 1,4241,676,676,676
BEGIN DESCRIPTION:
UNT 170 IN UKCR 2.0
END DESCRIPTION:
XS GIS Cut Line= 3
      3681899.62     10542110.20      3681449.61     10541810.19
      3681399.61     10541360.21
#Sta/Elev= 30
  4447.5  286.41  4491.1  280.75  4506.1  279.97  4519.6  276.81  4650.3  264.27
  4656.3  265.00  4663.9  263.48  4677.4  263.66  4707.4  260.99  4713.4  261.46
  4758.5  257.46  4830.6  255.59  4851.6  254.13  4857.6  255.53  4923.8  252.83
  4980.8  252.17  4998.4  249.45  5018.5  251.63  5025.6  248.75  5028.3  248.25
  5031.6  248.75  5038.7  253.31  5048.7  250.58  5058.8  254.50  5068.8  259.94
  5119.2  265.05  5169.5  276.09  5253.4  283.23  5350.6  288.93  5441.1  290.14
#Mann=4,-1,0
  4447.5    0.16       0  5025.6    0.07       0  5031.6    0.16       0
  5253.4    0.05       0
Bank Sta=5025.6,5031.6
Exp/Cntr=0.3,0.1

Type RM Length L Ch R = 1,3565,625,625,625
BEGIN DESCRIPTION:
Mapping XS 529f4f5d
END DESCRIPTION:
XS GIS Cut Line= 3
      3682108.41     10542257.11      3681976.46     10541500.13
      3681476.43     10541201.51
#Sta/Elev= 30
  4334.8  294.06  4357.0  293.72  4443.3  288.41  4504.2  283.72  4530.6  280.56
  4544.8  280.51  4585.1  276.67  4590.2  277.31  4595.6  275.64  4649.8  271.64
  4697.1  266.02  4798.6  256.43  4839.2  253.91  4971.2  248.98  4980.1  251.40
  4991.5  248.88  4994.0  246.45  4996.8  245.95  5000.0  246.45  5019.6  249.00
  5042.2  251.97  5114.9  250.48  5181.1  254.59  5210.3  258.95  5284.2  265.07
  5355.8  276.50  5406.8  281.81  5465.2  285.28  5576.1  288.00  5685.6  293.28
#Mann=5,-1,0
  4334.8    0.16       0  4980.1    0.12       0  4994.0    0.07       0
  5000.0    0.12       0  5019.6    0.16       0
Bank Sta=4994,5000
Exp/Cntr=0.3,0.1

Type RM Length L Ch R = 1,2940,583,583,583
BEGIN DESCRIPTION:
Mapping XS 3fc113ca
END DESCRIPTION:
XS GIS Cut Line= 3
      3682546.41     10542785.48      3682361.95     10541266.38
      3681396.22     10541038.51
#Sta/Elev= 30
  3623.5  301.79  3709.4  300.78  3870.6  294.85  3968.3  289.04  3981.4  285.63
  4011.6  285.41  4050.0  280.42  4072.1  283.88  4172.8  281.18  4307.6  273.78
  4444.8  269.72  4475.0  266.75  4827.6  249.40  4898.1  247.49  4978.7  248.13
  4988.7  245.72  4995.8  241.50  4998.6  241.00  5001.8  241.50  5008.9  246.45
  5019.0  247.94  5193.7  247.09  5437.8  248.38  5509.0  248.11  5598.7  254.89
  5731.5  267.84  5810.4  278.62  5942.5  291.81  5998.7  294.10  6146.0  293.11
#Mann=6,-1,0
  3623.5    0.05       0  4307.6    0.16       0  4995.8    0.07       0
  5001.8    0.16       0  5193.7    0.12       0  5437.8    0.16       0
Bank Sta=4995.8,5001.8
Exp/Cntr=0.3,0.1

Type RM Length L Ch R = 1,2357,1091,1091,1091
BEGIN DESCRIPTION:
Mapping XS 89da1935
END DESCRIPTION:
XS GIS Cut Line= 4
      3682709.17     10542850.58      3682937.03     10541754.66
      3682752.57     10540973.41      3681287.68     10540745.54
#Sta/Elev= 30
  3298.6  302.47  3425.1  302.03  3533.9  298.85  3636.1  292.49  3720.6  289.72
  3966.0  276.42  4149.5  263.55  4161.3  261.84  4387.3  252.88  4587.0  246.46
  4892.4  243.66  4987.7  244.42  5005.2  237.13  5008.0  236.63  5011.2  237.13
  5018.5  244.28  5028.8  245.08  5102.4  243.72  5339.7  241.87  5739.8  245.61
  5795.1  247.31  5881.5  245.03  5980.1  247.21  6104.2  252.68  6187.6  259.47
  6336.9  280.48  6449.3  289.10  6478.6  292.78  6556.7  296.44  6703.2  301.25
#Mann=9,-1,0
  3298.6    0.05       0  4149.5    0.16       0  4387.3    0.05       0
  4892.4    0.16       0  5005.2    0.07       0  5011.2    0.16       0
  5102.4    0.12       0  5980.1    0.16       0  6556.7    0.05       0
Bank Sta=5005.2,5011.2
Exp/Cntr=0.3,0.1

Type RM Length L Ch R = 1,1266,0,0,0
BEGIN DESCRIPTION:
UNT 170 IN UKCR 1.0
END DESCRIPTION:
XS GIS Cut Line= 4
      3683023.86     10542709.50      3683870.19     10541657.00
      3683739.98     10540799.80      3681504.77     10540278.97
#Sta/Elev= 30
  3285.8  301.21  3516.4  300.62  3594.8  294.94  3609.1  291.42  3730.7  280.42
  4242.7  255.46  4434.7  250.29  4643.3  249.41  4727.8  246.02  4872.1  238.54
  4926.5  237.40  4987.2  239.19  5004.4  237.72  5006.5  235.48  5009.2  234.98
  5012.5  235.48  5017.5  239.00  5027.2  238.64  5310.8  242.04  5792.3  237.89
  6084.4  239.52  6624.8  241.59  6664.4  241.88  6802.2  243.62  7093.5  242.15
  7280.1  247.67  7594.1  287.67  7679.2  290.91  7747.3  290.75  7798.5  291.05
#Mann=10,-1,0
  3285.8    0.05       0  4727.8    0.12       0  5006.5    0.07       0
  5012.5    0.12       0  5027.2    0.05       0  6084.4    0.12       0
  6624.8    0.16       0  6664.4    0.12       0  7093.5    0.16       0
  7747.3    0.05       0
Bank Sta=5006.5,5012.5
Exp/Cntr=0.3,0.1

Chan Stop Cuts=-1