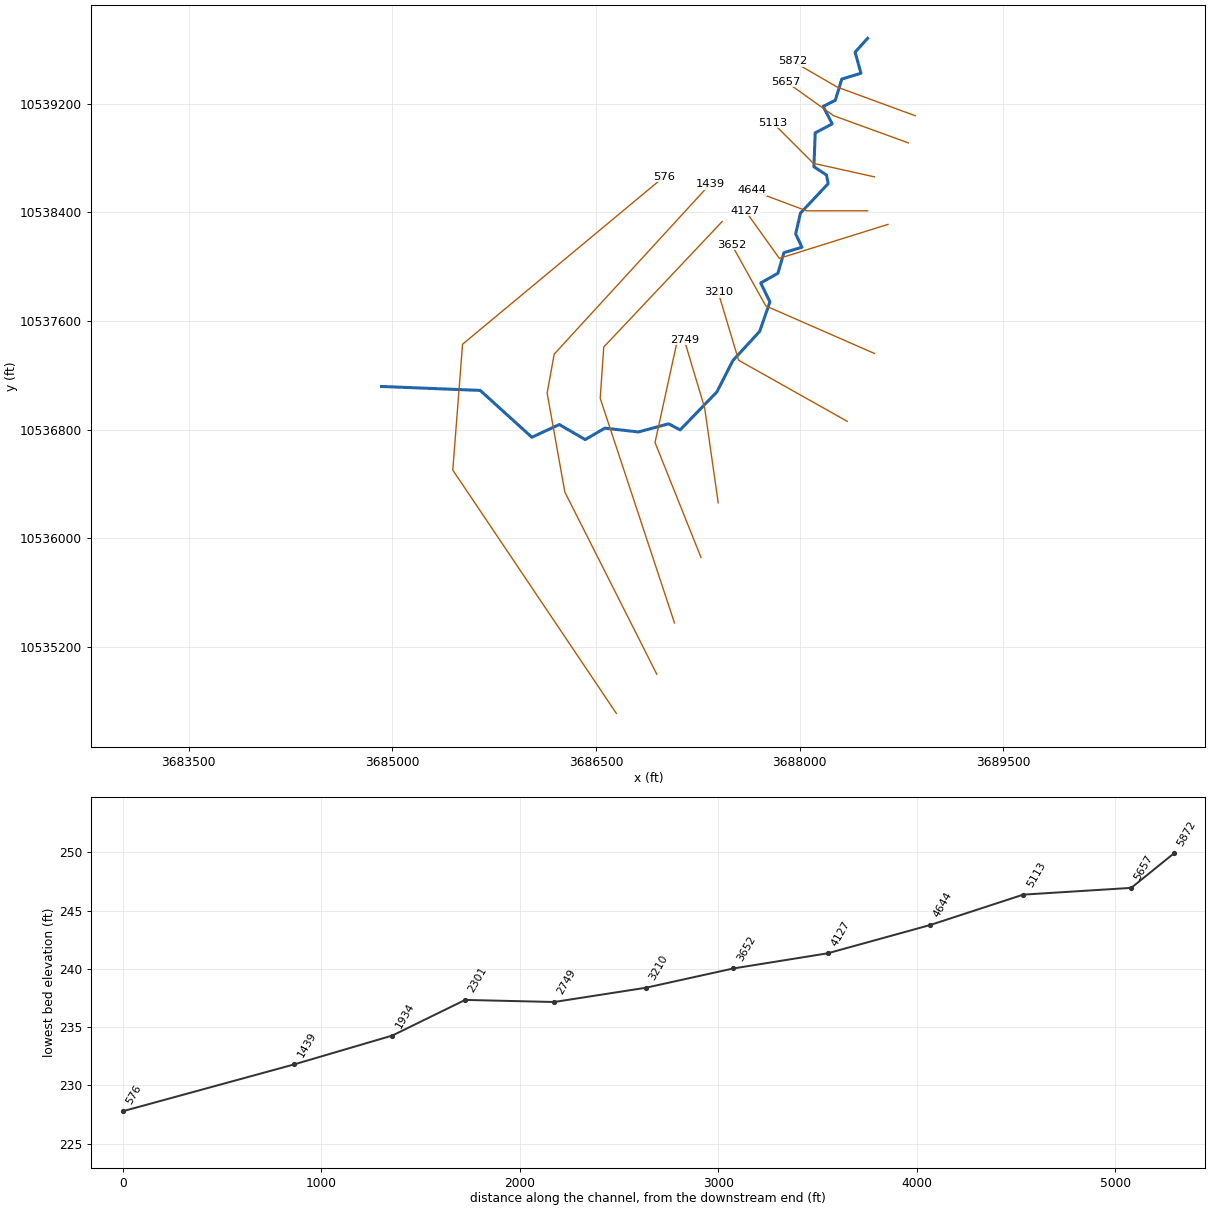
--- UNT 171 IN UKCR.prj (project) ---

Proj Title=UNT 171 IN UKCR Base Level Engineering
Current Plan=p01
Default Exp/Contr=0.3,0.1
English Units
Geom File=g01
Flow File=f01
Plan File=p01
Y Axis Title=Elevation
X Axis Title(PF)=Main Channel Distance
X Axis Title(XS)=Station
BEGIN DESCRIPTION:
UNT 171 IN UKCR
END DESCRIPTION:
DSS Export Rating Curves= 0
DSS Export Rating Curve Sorted= 0
DSS Export Volume Flow Curves= 0
DXF OffsetX= 0
DXF OffsetY= 0
DXF ScaleX= 1
DXF ScaleY= 10

--- UNT 171 IN UKCR.p01 (plan) ---

Plan Title=Multiple Run
Short Identifier=Multiple
Geom File=g01
Flow File=f01
Subcritical Flow
K Sum by GR= 0
Std Step Tol= 0.01
Critical Tol= 0.01
Num of Std Step Trials= 20
Max Error Tol= 0.3
Flow Tol Ratio= 0.001
Split Flow NTrial= 30
Split Flow Tol= 0.02
Split Flow Ratio= 0.02
Log Output Level= 0
Friction Slope Method= 1
Unsteady Friction Slope Method= 2
Unsteady Bridges Friction Slope Method= 1
Parabolic Critical Depth
Global Vel Dist=  1 , 1 , 1
Global Log Level= 0
CheckData=True
Encroach Param= -1, 0, 0, 0
BEGIN DESCRIPTION:
Multiple Run
END DESCRIPTION:

--- UNT 171 IN UKCR.f01 (steady flow) ---

Flow Title=Multiple
Number of Profiles=7
Profile Names=10-year,25-year,50-year,1pct_min,100-year,1pct_plu,500-year
River Rch & RM= UNT 171 IN UKCR,Reach-1,5872
     944    1318    1637    1491    2016    2727    3076
Boundary for River Rch & Prof#=UNT 171 IN UKCR,Reach-1,1
Up Type=0
Dn Type=3
Dn Slope=0.005
Boundary for River Rch & Prof#=UNT 171 IN UKCR,Reach-1,2
Up Type=0
Dn Type=3
Dn Slope=0.005
Boundary for River Rch & Prof#=UNT 171 IN UKCR,Reach-1,3
Up Type=0
Dn Type=3
Dn Slope=0.005
Boundary for River Rch & Prof#=UNT 171 IN UKCR,Reach-1,4
Up Type=0
Dn Type=3
Dn Slope=0.005
Boundary for River Rch & Prof#=UNT 171 IN UKCR,Reach-1,5
Up Type=0
Dn Type=3
Dn Slope=0.005
Boundary for River Rch & Prof#=UNT 171 IN UKCR,Reach-1,6
Up Type=0
Dn Type=3
Dn Slope=0.005
Boundary for River Rch & Prof#=UNT 171 IN UKCR,Reach-1,7
Up Type=0
Dn Type=3
Dn Slope=0.005

--- UNT 171 IN UKCR.g01 (geometry) ---

Geom Title=Existing Conditions
Program Version=4.10

River Reach=UNT 171 IN UKCR ,Reach-1
Reach XY= 30
       3688499.5       10539680.      3688407.25       10539578.
      3688450.75       10539423.       3688309.5       10539380.
       3688261.5       10539224.       3688172.5       10539179.
      3688238.75       10539050.      3688113.75       10538984.
      3688104.25       10538735.       3688196.5       10538674.
        3688209.       10538610.        3688005.       10538393.
        3687970.       10538240.      3688016.25       10538142.
       3687883.5       10538102.        3687839.       10537950.
       3687712.5       10537879.      3687780.25       10537740.
      3687705.25       10537523.        3687507.       10537307.
        3687390.       10537077.      3687119.25       10536797.
      3687034.75       10536842.      3686811.75       10536782.
      3686564.83      10536810.1      3686420.75       10536726.
      3686229.78     10536836.62      3686027.75       10536743.
      3685647.25       10537088.        3684921.       10537117.

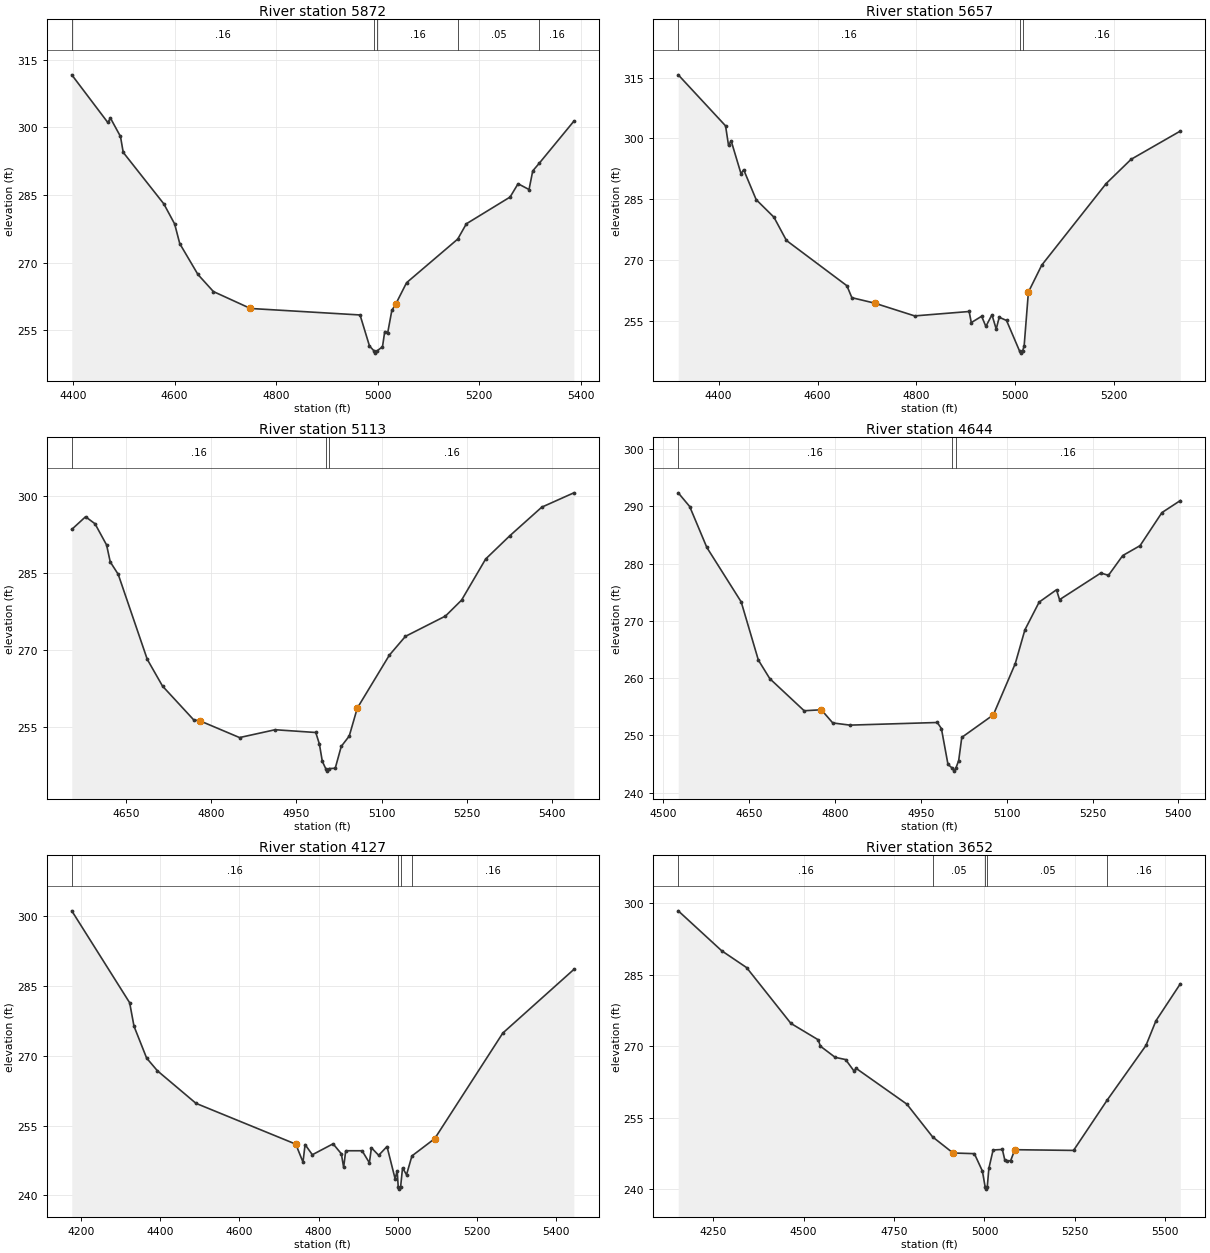
Type RM Length L Ch R = 1 ,5872    ,215,215,215
BEGIN DESCRIPTION:
UNT 171 IN UKCR 12.0
END DESCRIPTION:
XS GIS Cut Line= 3
      3688849.64     10539110.18      3688275.57     10539321.32
      3687949.61     10539510.19
#Sta/Elev= 30
  4397.7  311.61  4468.6  301.05  4473.9  302.01  4493.6  297.94    4499  294.42
  4578.9  283.01  4600.2  278.56  4610.3  274.19  4646.1  267.35  4676.5  263.57
  4749.4  259.82  4965.2  258.38  4983.8   251.5  4992.7  250.42  4995.4  249.92
  4998.7  250.42  5009.4  251.33  5013.8   254.7  5019.6   254.4  5027.8  259.39
  5035.3  260.75  5056.8  265.53  5157.5   275.2  5174.5  278.59  5260.6  284.52
  5276.3  287.47  5297.9  286.18  5305.2  290.32  5317.7  291.97  5386.1  301.33
#Mann= 5 ,-1 , 0
  4397.7     .16       0  4992.7     .07       0  4998.7     .16       0
  5157.5     .05       0  5317.7     .16       0
Bank Sta=4749.4,5035.3
XS Rating Curve= 0 ,0
Exp/Cntr=0.3,0.1

Type RM Length L Ch R = 1 ,5657    ,544,544,544
BEGIN DESCRIPTION:
UNT 171 IN UKCR 11.0
END DESCRIPTION:
XS GIS Cut Line= 3
      3688799.58      10538910.2      3688249.61     10539110.19
      3687899.62     10539360.18
#Sta/Elev= 30
  4318.3  315.68    4414  303.08    4420  298.26  4425.3  299.39  4445.3  291.25
  4450.6  292.25  4475.9  284.86  4511.8  280.53  4537.1  274.78  4659.4   263.6
  4669.4  260.65  4715.3  259.31  4796.4  256.15  4906.6  257.24  4910.9   254.5
  4931.8  256.06  4940.4  253.56  4952.7  256.43  4961.3   252.9  4967.4  255.82
  4982.2  255.02  5008.6  247.46  5011.4  246.96  5014.6  247.46  5017.8  248.73
  5026.4  262.03  5053.4  268.69  5183.7  288.84  5234.1  294.82  5333.6  301.79
#Mann= 3 ,-1 , 0
  4318.3     .16       0  5008.6     .07       0  5014.6     .16       0
Bank Sta=4715.3,5026.4
XS Rating Curve= 0 ,0
Exp/Cntr=0.3,0.1

Type RM Length L Ch R = 1 ,5113    ,469,469,469
BEGIN DESCRIPTION:
UNT 171 IN UKCR 10.0
END DESCRIPTION:
XS GIS Cut Line= 3
      3688549.59     10538660.19      3688099.61     10538760.19
      3687799.62     10539060.18
#Sta/Elev= 30
  4553.9  293.56  4578.2  296.03  4594.9  294.66  4615.3  290.52  4621.7  287.23
  4635.8  284.79    4687   268.2  4713.9  262.98    4769  256.37  4779.2  256.23
  4849.7  252.93  4912.4  254.46  4984.1  253.92  4990.5  251.66  4995.6   248.3
  5001.6  246.88  5004.4  246.38  5007.6  246.88  5018.4  246.94    5029   251.2
  5043.1  253.23  5057.3  258.68  5113.8  269.01  5142.1  272.68  5212.8  276.65
  5241.1  279.75  5283.6  287.78    5326   292.3  5382.5   297.9  5439.1   300.7
#Mann= 3 ,-1 , 0
  4553.9     .16       0  5001.6     .07       0  5007.6     .16       0
Bank Sta=4779.2,5057.3
XS Rating Curve= 0 ,0
Exp/Cntr=0.3,0.1

Type RM Length L Ch R = 1 ,4644    ,517,517,517
BEGIN DESCRIPTION:
UNT 171 IN UKCR 9.0
END DESCRIPTION:
XS GIS Cut Line= 3
      3688499.58     10538410.19      3688049.61     10538410.19
      3687649.58      10538560.2
#Sta/Elev= 30
  4526.1  292.35  4546.1  289.96  4576.1  282.81  4636.1  273.31  4666.1  263.15
  4686.1  259.91  4746.1  254.31  4776.1  254.48  4796.1  252.18  4826.1   251.8
  4978.7  252.26  4985.9   251.2  4997.4  244.94  5005.1  244.27  5007.9  243.77
  5011.1  244.27  5016.1  245.62  5021.5  249.66  5076.6  253.59  5114.9  262.53
  5131.8  268.44  5156.7  273.28    5187  275.43  5192.3   273.7  5264.4  278.35
  5277.8  277.95  5302.7   281.4    5333  283.13  5371.2   288.9  5403.3     291
#Mann= 3 ,-1 , 0
  4526.1     .16       0  5005.1     .07       0  5011.1     .16       0
Bank Sta=4776.1,5076.6
XS Rating Curve= 0 ,0
Exp/Cntr=0.3,0.1

Type RM Length L Ch R = 1 ,4127    ,475,475,475
BEGIN DESCRIPTION:
UNT 171 IN UKCR 8.0
END DESCRIPTION:
XS GIS Cut Line= 3
      3688649.64      10538310.2      3687849.61     10538060.19
      3687599.61     10538410.19
#Sta/Elev= 30
  4176.6  301.16  4322.8  281.41  4333.8  276.36  4365.7  269.51    4393  266.77
  4490.4  259.78  4742.4  251.01  4760.7  247.15    4766  250.92  4784.3  248.73
  4836.7  251.08  4857.6  248.93  4863.4     246  4868.6  249.59    4910  249.59
  4928.4     247  4933.6  250.23  4951.9  248.61  4972.9   250.5  4993.3   243.6
  4998.5  245.22  5001.3  241.84  5004.1  241.34  5007.3  241.84  5012.2  245.91
  5022.2  244.43  5035.9  248.48  5093.4  252.19  5265.5  274.89  5444.9  288.56
#Mann= 4 ,-1 , 0
  4176.6     .16       0  5001.3     .07       0  5007.3     .16       0
  5035.9     .16       0
Bank Sta=4742.4,5093.4
XS Rating Curve= 0 ,0
Exp/Cntr=0.3,0.1

Type RM Length L Ch R = 1 ,3652    ,442,442,442
BEGIN DESCRIPTION:
UNT 171 IN UKCR 7.0
END DESCRIPTION:
XS GIS Cut Line= 3
      3688549.56     10537360.21      3687749.61     10537710.19
      3687499.63     10538160.15
#Sta/Elev= 30
  4153.4  298.34  4273.4  289.98  4342.4  286.45  4464.8  274.76  4540.4  271.32
  4546.3  269.99  4587.2  267.65  4616.1  267.18  4639.5  264.76  4644.9  265.35
  4785.3  257.85  4856.6  250.98  4913.1  247.61    4972  247.47  4994.2  243.83
  5001.7  240.54  5004.5  240.04  5007.7  240.54  5012.1  244.39  5023.8  248.24
  5049.4  248.35  5056.3  246.09    5062  245.96  5072.3     246  5083.8   248.3
  5246.2  248.15  5339.6  258.74  5446.4  270.14  5473.9   275.3  5541.3  283.05
#Mann= 5 ,-1 , 0
  4153.4     .16       0  4856.6     .05       0  5001.7     .03       0
  5007.7     .05       0  5339.6     .16       0
Bank Sta=4913.1,5083.8
XS Rating Curve= 0 ,0
Exp/Cntr=0.3,0.1

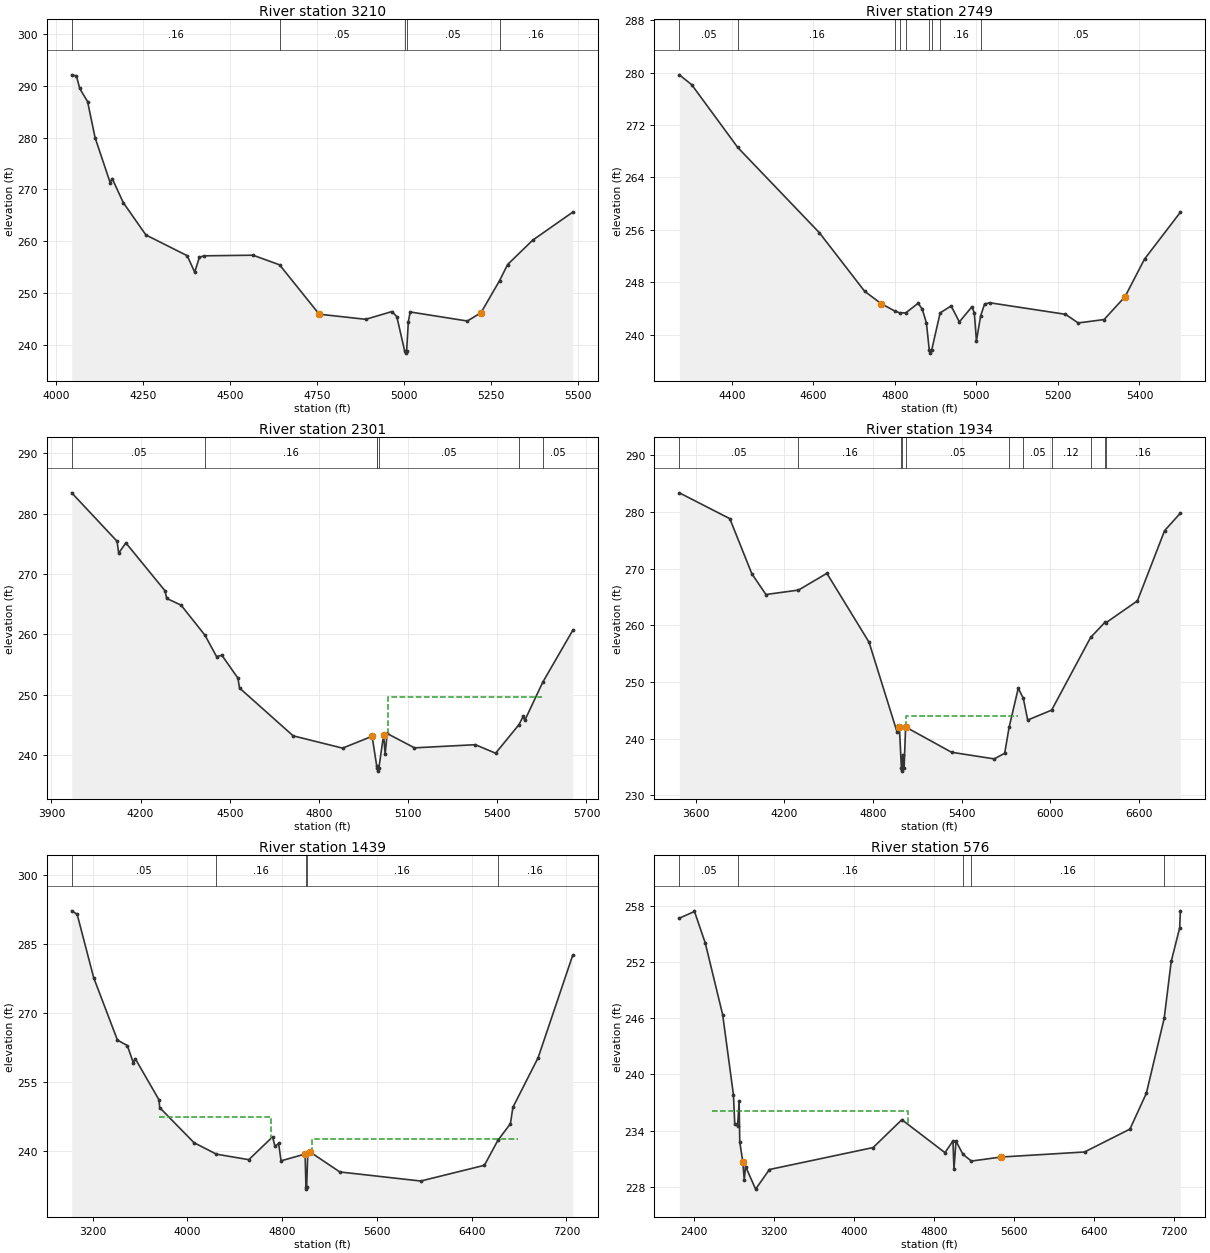
Type RM Length L Ch R = 1 ,3210    ,461,461,461
BEGIN DESCRIPTION:
UNT 171 IN UKCR 6.0
END DESCRIPTION:
XS GIS Cut Line= 3
       3688349.6     10536860.19      3687549.61     10537310.19
       3687399.6      10537810.2
#Sta/Elev= 30
  4045.4  292.12  4059.1   291.9  4068.3   289.5    4091  286.95  4112.6  279.98
    4156  271.28  4161.7   272.1  4193.6  267.44  4258.6   261.2  4377.2   257.2
  4398.8  254.03  4412.5  256.91  4426.2  257.17  4566.5  257.29  4642.8  255.43
  4756.7   245.9  4890.3  244.91  4965.9  246.41  4979.8  245.42    5002  238.88
  5004.8  238.38    5008  238.88  5012.9  244.44  5018.1  246.33  5182.5  244.58
  5221.7  246.19  5275.1  252.38  5298.2  255.49  5370.4   260.2  5485.3   265.6
#Mann= 5 ,-1 , 0
  4045.4     .16       0  4642.8     .05       0    5002     .03       0
    5008     .05       0  5275.1     .16       0
Bank Sta=4756.7,5221.7
XS Rating Curve= 0 ,0
Exp/Cntr=0.3,0.1

Type RM Length L Ch R = 1 ,2749    ,448,448,448
BEGIN DESCRIPTION:
UNT 171 IN UKCR 5.0
END DESCRIPTION:
XS GIS Cut Line= 3
       3687399.6     10536260.23      3687299.61     10536960.19
       3687149.6     10537460.21
#Sta/Elev= 30
  4271.3  279.67  4301.6  278.16  4414.6  268.57  4614.7  255.56  4725.8  246.61
  4766.2  244.73  4800.3  243.57  4811.7  243.32  4826.7  243.31  4857.1  244.78
  4867.2  243.88  4877.3   241.8  4884.4  237.66  4887.2  237.16  4890.4  237.66
  4911.1  243.31    4938  244.37  4958.2  241.93  4988.8  244.23  4994.9  243.35
  5000.1  239.04  5010.5  242.87  5020.1  244.66  5033.2  244.85  5218.5  243.09
  5249.8  241.77  5313.3  242.29  5364.7  245.79  5412.5  251.53  5500.4  258.68
#Mann= 9 ,-1 , 0
  4271.3     .05       0  4414.6     .16       0  4800.3     .05       0
  4811.7     .16       0  4826.7     .05       0  4884.4     .07       0
  4890.4     .05       0  4911.1     .16       0  5010.5     .05       0
Bank Sta=4766.2,5364.7
XS Rating Curve= 0 ,0
Exp/Cntr=0.3,0.1

Type RM Length L Ch R = 1 ,2301    ,367,367,367
BEGIN DESCRIPTION:
UNT 171 IN UKCR 4.0
END DESCRIPTION:
XS GIS Cut Line= 3
      3687272.98     10535857.77      3686934.43     10536704.13
      3687099.62     10537460.23
#Sta/Elev= 30
  3968.2  283.47  4120.8  275.44  4126.2  273.48  4150.4  275.17  4282.3  267.22
  4287.7  265.97  4336.2  264.85  4416.5  259.87  4455.5  256.33  4473.5  256.54
  4527.4  252.75  4532.7  251.12  4713.2  243.19  4879.5  241.15  4978.8  243.12
  4994.1  238.26  4995.6  237.84  4998.3  237.34  5001.6  237.84  5017.5  243.41
  5022.7  240.13  5029.3  243.58  5121.4   241.2  5326.1  241.72  5394.3  240.31
  5473.1  245.06  5487.2  246.45  5492.3  245.74  5552.9  252.08  5653.7  260.67
#Mann= 7 ,-1 , 0
  3968.2     .05       0  4416.5     .16       0  4994.1     .05       0
  4995.6     .03       0  5001.6     .05       0  5473.1     .16       0
  5552.9     .05       0
#XS Ineff= 1 ,-1
 5031.82 5548.86249.6167
Permanent Ineff=
       F
Bank Sta=4978.8,5017.5
XS Rating Curve= 0 ,0
Exp/Cntr=0.3,0.1

Type RM Length L Ch R = 1 ,1934    ,495,495,495
BEGIN DESCRIPTION:
UNT 171 IN UKCR 3.0
END DESCRIPTION:
XS GIS Cut Line= 4
      3687077.66       10535376.      3686530.78     10537029.65
      3686556.82     10537407.26      3687429.19      10538331.7
#Sta/Elev= 30
    3489  283.41  3830.5  278.85  3979.8  269.11    4075  265.46  4295.3  266.24
  4487.4   269.2  4772.9  257.04  4963.2  241.14  4978.5  241.99    4992  234.78
  4994.7  234.28    4998  234.78  5000.2   237.2  5010.1  234.78  5020.6  242.12
  5022.9  242.04  5331.5  237.61  5620.4  236.44  5691.2  237.44  5720.8  241.99
    5783  248.92  5817.3  247.13  5846.9   243.3  6008.9  245.05  6272.8  257.88
  6369.6  260.55  6374.6  260.44  6589.5  264.34  6773.4  276.72  6880.3  279.83
#Mann= 11 ,-1 , 0
    3489     .05       0  4295.3     .16       0    4992     .07       0
    4998     .16       0  5022.9     .05       0  5720.8     .16       0
  5817.3     .05       0  6008.9     .12       0  6272.8     .16       0
  6369.6     .05       0  6374.6     .16       0
#XS Ineff= 1 ,-1
 5022.73 5784.09244.0631
Permanent Ineff=
       F
Bank Sta=4978.5,5020.6
XS Rating Curve= 0 ,0
Exp/Cntr=0.3,0.1

Type RM Length L Ch R = 1 ,1439    ,863,863,863
BEGIN DESCRIPTION:
UNT 171 IN UKCR 2.0
END DESCRIPTION:
XS GIS Cut Line= 5
      3686947.45      10534998.4      3686270.37     10536339.55
      3686140.16     10537068.72      3686192.24     10537355.17
      3687338.05     10538605.15
#Sta/Elev= 30
  3023.3  292.26  3069.2  291.51  3208.6  277.75  3409.3  264.18  3492.9  262.99
  3543.1  259.28  3559.8  260.14  3760.4  251.19    3766  249.51  4055.9  241.89
  4245.4  239.39  4518.5   238.2  4719.3  243.16  4739.6  241.07  4770.1  241.73
  4790.7  237.95  4993.6  239.42  5000.8   232.3  5003.5   231.8  5006.8   232.3
  5016.2  239.54  5034.2   239.9  5287.2  235.53    5970  233.56  6507.7  236.98
  6621.1  242.39  6727.2  246.01  6748.1  249.57  6960.9  260.34  7253.2  282.62
#Mann= 5 ,-1 , 0
  3023.3     .05       0  4245.4     .16       0  5000.8     .07       0
  5006.8     .16       0  6621.1     .16       0
#XS Ineff= 2 ,-1
 3758.52  4701.7  247.39 5051.14 6789.77242.6852
Permanent Ineff=
       F       F
Bank Sta=4993.6,5034.2
XS Rating Curve= 0 ,0
Exp/Cntr=0.3,0.1

Type RM Length L Ch R = 1 ,576     ,0,0,0
BEGIN DESCRIPTION:
UNT 171 IN UKCR 1.0
END DESCRIPTION:
XS GIS Cut Line= 4
      3686649.63     10534710.16       3685445.5     10536501.48
      3685517.38     10537427.99      3686999.59     10538660.17
#Sta/Elev= 30
  2249.9  256.66  2401.4  257.37  2509.4     254  2683.4  246.37  2791.4  237.82
  2804.2  234.76  2832.5   234.5  2848.4  237.13  2854.4  232.83  2884.4  230.72
  2899.4   228.8  2912.7  230.19  3013.2  227.78  3151.4  229.87  4189.3  232.21
  4477.2  235.18  4908.5  231.67  4988.8  232.91  4998.8  229.88  5018.9   232.9
  5089.5  231.48  5173.4  230.77    5469   231.2  6306.2  231.74  6760.6  234.18
  6924.7     238  7103.3  245.99  7173.3  252.04    7258  255.62  7265.1  257.44
#Mann= 5 ,-1 , 0
  2249.9     .05       0  2832.5     .16       0  5089.5     .05       0
  5173.4     .16       0  7103.3     .16       0
#XS Ineff= 1 ,-1
 2572.73 4543.18  236.13
Permanent Ineff=
       F
Bank Sta=2884.4,5469
XS Rating Curve= 0 ,0
Exp/Cntr=0.3,0.1

Chan Stop Cuts=-1
Use User Specified Reach Order=0
Composite Channel Slope=5