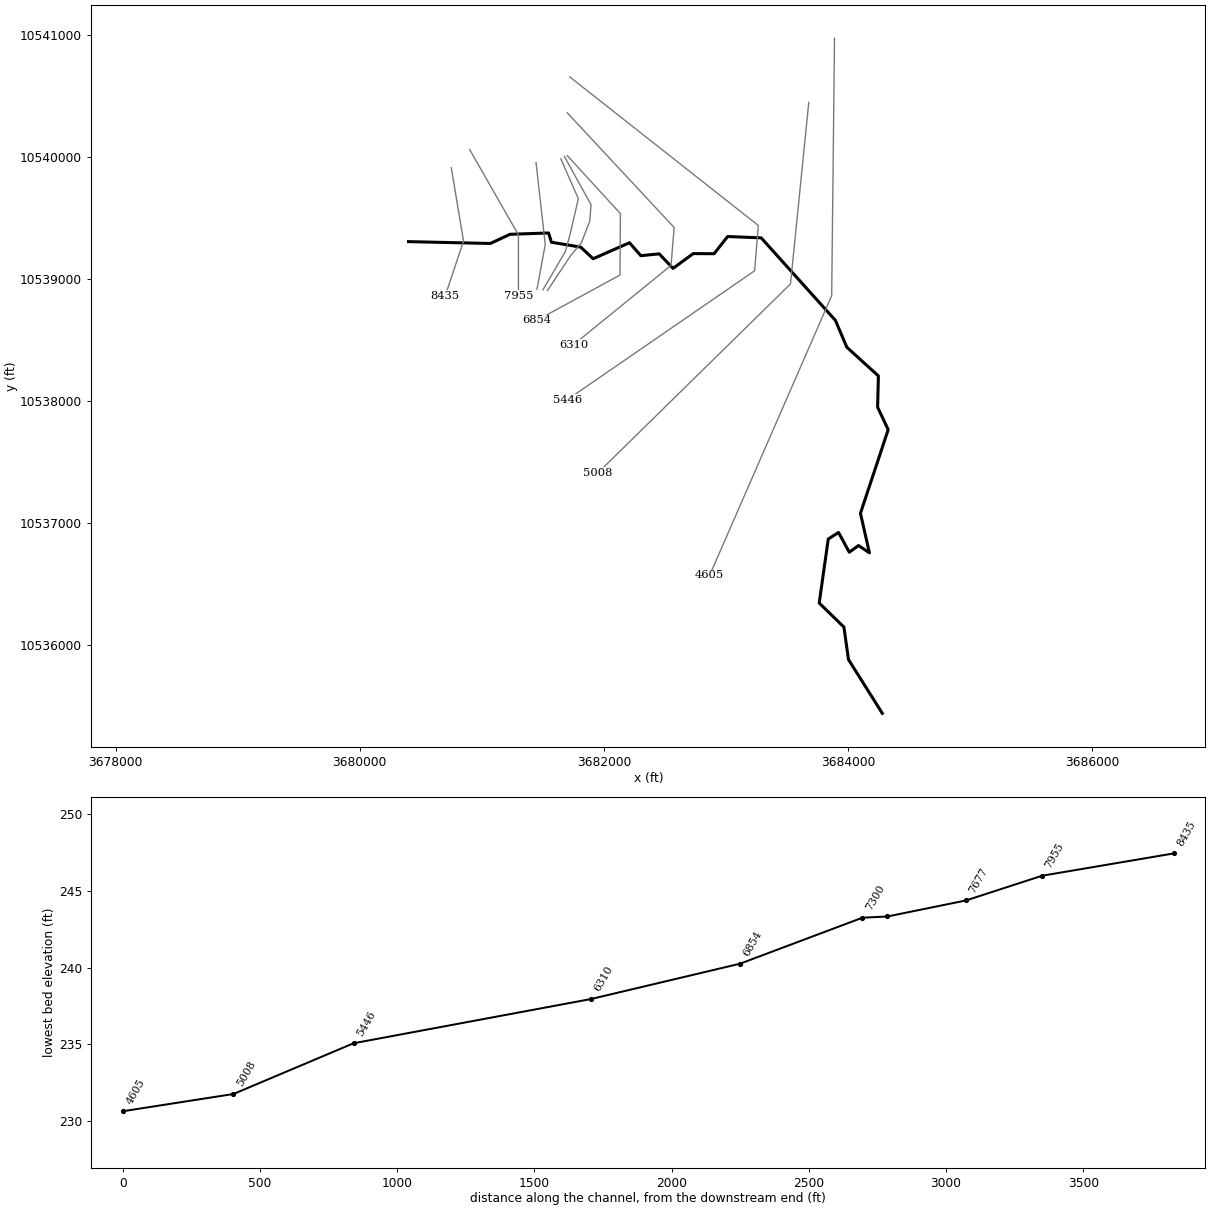
--- UNT 173 IN UKCR.prj (project) ---

Proj Title=UNT 173 IN UKCR Base Level Engineering
Current Plan=p01
Default Exp/Contr=0.3,0.1
English Units
Geom File=g01
Flow File=f01
Plan File=p01
BEGIN DESCRIPTION:
UNT 173 IN UKCR
END DESCRIPTION:

--- UNT 173 IN UKCR.p01 (plan) ---

Plan Title=Multiple Run
Short Identifier=Multiple
Geom File=g01
Flow File=f01
Subcritical Flow
K Sum by GR= 0
Std Step Tol= 0.01
Critical Tol= 0.01
Num of Std Step Trials= 20
Max Error Tol= 0.3
Flow Tol Ratio= 0.001
Split Flow NTrial= 30
Split Flow Tol= 0.02
Split Flow Ratio= 0.02
Log Output Level= 0
Friction Slope Method= 1
Unsteady Friction Slope Method= 2
Unsteady Bridges Friction Slope Method= 1
Parabolic Critical Depth
Global Vel Dist=  1 , 1 , 1
Global Log Level= 0
CheckData=True
Encroach Param= -1, 0, 0, 0
BEGIN DESCRIPTION:
Multiple Run
END DESCRIPTION:

--- UNT 173 IN UKCR.f01 (steady flow) ---

Flow Title=Multiple
Number of Profiles=7
Profile Names=10-year,25-year,50-year,1pct_min,100-year,1pct_plu,500-year
River Rch & RM= UNT 173 IN UKCR,Reach-1,8435
     583     798     977     881    1191    1611    1777
River Rch & RM= UNT 173 IN UKCR,Reach-1,7955
     791    1094    1348    1220    1649    2230    2481
Boundary for River Rch & Prof#=UNT 173 IN UKCR,Reach-1,1
Up Type=0
Dn Type=3
Dn Slope=0.005
Boundary for River Rch & Prof#=UNT 173 IN UKCR,Reach-1,2
Up Type=0
Dn Type=3
Dn Slope=0.005
Boundary for River Rch & Prof#=UNT 173 IN UKCR,Reach-1,3
Up Type=0
Dn Type=3
Dn Slope=0.005
Boundary for River Rch & Prof#=UNT 173 IN UKCR,Reach-1,4
Up Type=0
Dn Type=3
Dn Slope=0.005
Boundary for River Rch & Prof#=UNT 173 IN UKCR,Reach-1,5
Up Type=0
Dn Type=3
Dn Slope=0.005
Boundary for River Rch & Prof#=UNT 173 IN UKCR,Reach-1,6
Up Type=0
Dn Type=3
Dn Slope=0.005
Boundary for River Rch & Prof#=UNT 173 IN UKCR,Reach-1,7
Up Type=0
Dn Type=3
Dn Slope=0.005

--- UNT 173 IN UKCR.g01 (geometry) ---

Geom Title=Existing Conditions

River Reach=UNT 173 IN UKCR,Reach-1
Reach XY= 30
      3680399.19     10539305.07      3681069.50     10539290.00
      3681230.50     10539365.00      3681546.25     10539376.00
      3681570.00     10539300.00      3681809.75     10539260.00
      3681911.50     10539165.00      3682208.75     10539296.00
      3682302.25     10539190.00      3682452.50     10539205.00
      3682566.00     10539086.00      3682731.25     10539207.00
      3682902.00     10539206.00      3683013.25     10539347.00
      3683288.00     10539336.00      3683896.00     10538660.00
      3683989.50     10538440.00      3684248.00     10538205.00
      3684241.50     10537949.00      3684328.25     10537765.00
      3684101.00     10537080.00      3684174.50     10536756.00
      3684085.25     10536816.00      3684009.50     10536761.00
      3683921.50     10536923.00      3683837.25     10536869.00
      3683763.25     10536345.00      3683965.50     10536148.00
      3684003.00     10535882.00      3684280.25     10535441.00

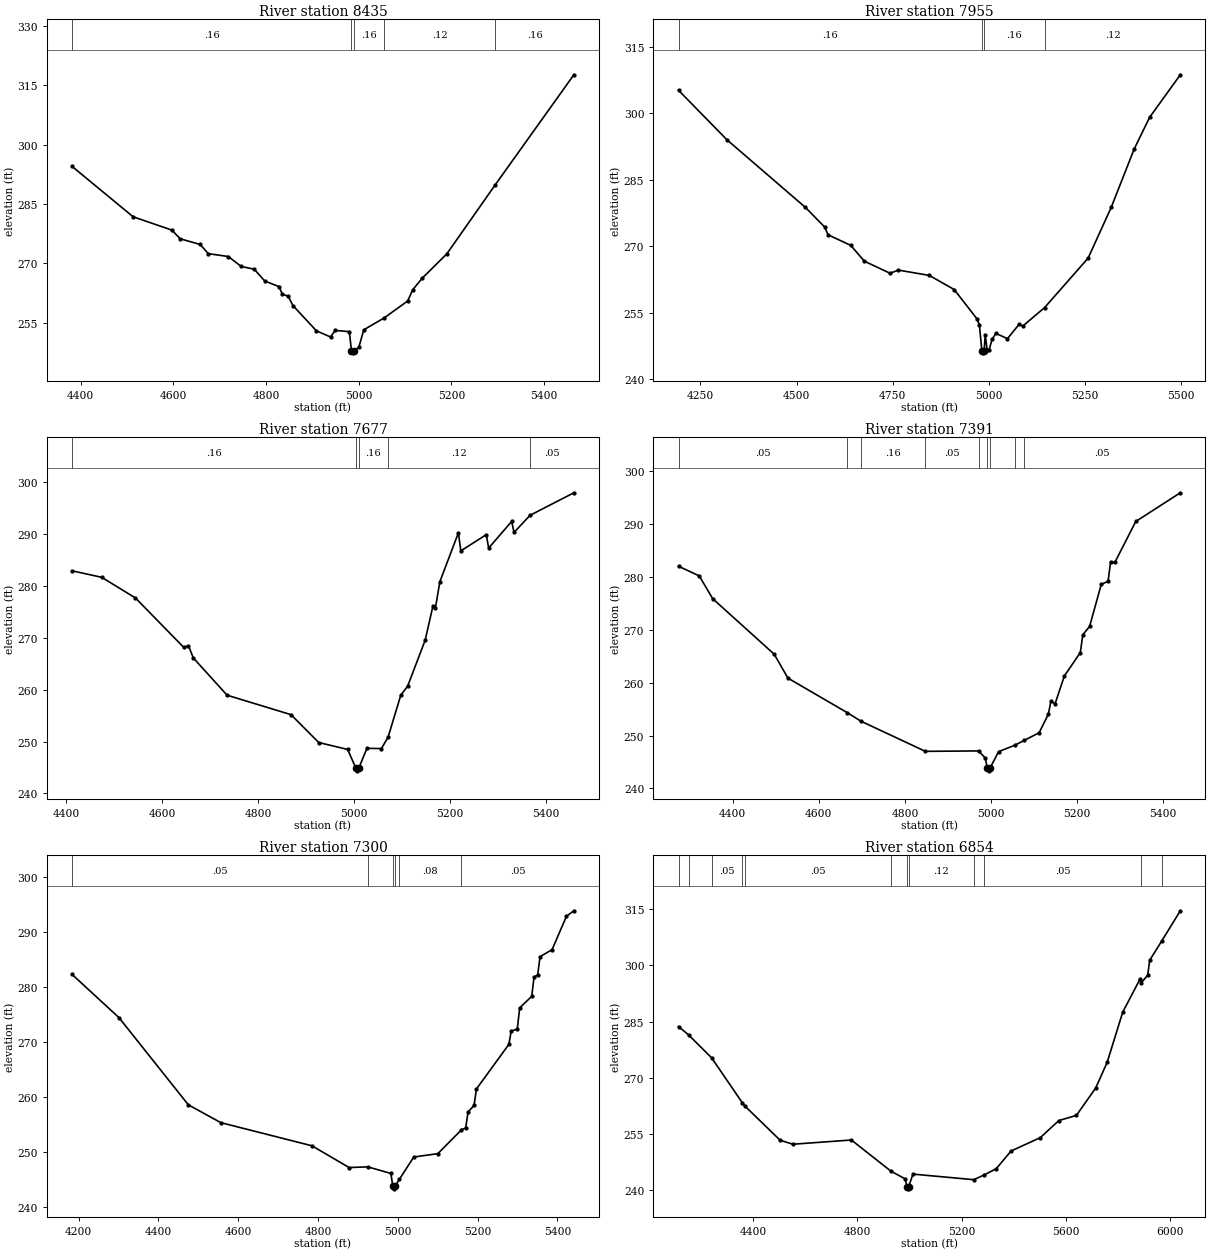
Type RM Length L Ch R = 1,8435,480,480,480
BEGIN DESCRIPTION:
UNT 173 IN UKCR 8.0
END DESCRIPTION:
XS GIS Cut Line= 3
      3680749.61     10539910.20      3680849.61     10539310.19
      3680699.62     10538860.22
#Sta/Elev= 30
  4381.7  294.49  4513.5  281.77  4597.1  278.41  4614.9  276.22  4658.0  274.79
  4675.7  272.46  4718.8  271.74  4746.7  269.23  4774.6  268.54  4797.4  265.56
  4827.8  264.16  4835.4  262.26  4848.1  261.69  4858.2  259.36  4908.9  252.98
  4939.3  251.42  4949.4  253.08  4979.9  252.77  4984.5  247.92  4987.2  247.42
  4990.5  247.92  5000.5  248.88  5011.1  253.24  5055.0  256.23  5105.9  260.53
  5116.5  263.33  5137.6  266.32  5190.3  272.42  5294.5  289.82  5464.3  317.63
#Mann=5,-1,0
  4381.7    0.16       0  4984.5    0.07       0  4990.5    0.16       0
  5055.0    0.12       0  5294.5    0.16       0
Bank Sta=4984.5,4990.5
Exp/Cntr=0.3,0.1

Type RM Length L Ch R = 1,7955,278,278,278
BEGIN DESCRIPTION:
UNT 173 IN UKCR 7.0
END DESCRIPTION:
XS GIS Cut Line= 3
      3680899.63     10540060.15      3681299.61     10539360.19
      3681299.61     10538860.18
#Sta/Elev= 30
  4192.9  305.22  4318.8  294.06  4523.3  278.78  4572.9  274.40  4582.3  272.60
  4641.3  270.22  4676.6  266.65  4743.5  263.93  4765.1  264.64  4845.8  263.44
  4910.5  260.25  4969.6  253.66  4976.1  252.25  4982.4  246.47  4985.2  245.97
  4988.4  246.47  4991.2  250.01  4996.2  246.69  5001.6  246.69  5009.1  249.05
  5019.1  250.36  5049.1  249.17  5079.1  252.38  5089.1  252.02  5145.9  256.19
  5259.1  267.35  5319.1  278.78  5379.1  291.99  5419.1  299.11  5499.1  308.72
#Mann=4,-1,0
  4192.9    0.16       0  4982.4    0.07       0  4988.4    0.16       0
  5145.9    0.12       0
Bank Sta=4982.4,4988.4
Exp/Cntr=0.3,0.1

Type RM Length L Ch R = 1,7677,286,286,286
BEGIN DESCRIPTION:
Mapping XS 51bf6042
END DESCRIPTION:
XS GIS Cut Line= 3
      3681443.69     10539951.55      3681519.21     10539282.25
      3681451.51     10538915.09
#Sta/Elev= 30
  4412.1  282.91  4473.9  281.66  4544.3  277.68  4644.9  268.17  4655.0  268.46
  4665.1  266.12  4735.5  258.94  4868.8  255.19  4926.7  249.82  4987.1  248.48
  5004.2  244.86  5007.0  244.36  5010.2  244.86  5027.3  248.70  5057.5  248.65
  5071.4  250.85  5097.9  258.94  5112.1  260.65  5148.8  269.55  5165.1  276.18
  5170.2  275.75  5179.3  280.77  5218.1  290.24  5223.2  286.75  5276.2  289.88
  5281.3  287.30  5329.2  292.42  5334.2  290.31  5367.6  293.61  5459.0  297.95
#Mann=5,-1,0
  4412.1    0.16       0  5004.2    0.07       0  5010.2    0.16       0
  5071.4    0.12       0  5367.6    0.05       0
Bank Sta=5004.2,5010.2
Exp/Cntr=0.3,0.1

Type RM Length L Ch R = 1,7391,91,91,91
BEGIN DESCRIPTION:
UNT 173 IN UKCR 6.0
END DESCRIPTION:
XS GIS Cut Line= 5
      3681646.82     10539982.77      3681790.05     10539657.25
      3681724.94     10539373.40      3681683.28     10539222.35
      3681499.62     10538910.21
#Sta/Elev= 30
  4274.0  282.04  4322.1  280.22  4353.3  275.91  4496.4  265.38  4528.1  260.87
  4665.6  254.35  4697.9  252.71  4847.4  247.01  4970.9  247.09  4986.4  245.76
  4991.5  243.82  4994.2  243.32  4997.5  243.82  5017.5  246.95  5054.7  248.15
  5077.4  249.10  5111.7  250.53  5133.2  254.05  5139.0  256.49  5148.8  256.02
  5170.3  261.28  5207.4  265.70  5213.2  269.09  5228.9  270.65  5256.1  278.63
  5271.8  279.18  5277.6  282.77  5287.5  282.76  5336.2  290.52  5439.7  295.95
#Mann=9,-1,0
  4274.0    0.05       0  4665.6    0.08       0  4697.9    0.16       0
  4847.4    0.05       0  4970.9    0.08       0  4991.5    0.07       0
  4997.5    0.08       0  5054.7    0.12       0  5077.4    0.05       0
Bank Sta=4991.5,4997.5
Exp/Cntr=0.3,0.1

Type RM Length L Ch R = 1,7300,446,446,446
BEGIN DESCRIPTION:
Mapping XS b6dc64aa
END DESCRIPTION:
XS GIS Cut Line= 6
      3681675.48     10540003.57      3681894.21     10539607.77
      3681883.80     10539472.35      3681816.09     10539297.88
      3681727.55     10539191.10      3681537.60     10538904.89
#Sta/Elev= 30
  4183.7  282.24  4301.0  274.40  4475.1  258.52  4556.5  255.28  4784.8  251.07
  4878.0  247.11  4924.7  247.24  4982.6  246.04  4987.4  243.74  4990.2  243.24
  4993.4  243.74  5003.7  244.95  5039.9  249.03  5100.3  249.64  5159.3  253.97
  5170.0  254.33  5176.0  257.22  5191.0  258.41  5197.0  261.41  5278.2  269.51
  5284.2  271.95  5299.3  272.27  5305.3  276.15  5335.4  278.25  5341.4  281.77
  5350.4  282.15  5356.4  285.48  5386.5  286.74  5422.6  292.83  5441.1  293.82
#Mann=6,-1,0
  4183.7    0.05       0  4924.7    0.16       0  4987.4    0.07       0
  4993.4    0.16       0  5003.7    0.08       0  5159.3    0.05       0
Bank Sta=4987.4,4993.4
Exp/Cntr=0.3,0.1

Type RM Length L Ch R = 1,6854,544,544,544
BEGIN DESCRIPTION:
UNT 173 IN UKCR 5.0
END DESCRIPTION:
XS GIS Cut Line= 4
      3681699.59     10540010.21      3682134.71     10539534.52
      3682131.63     10539031.54      3681449.63     10538660.20
#Sta/Elev= 30
  4114.8  283.66  4153.4  281.41  4241.6  275.30  4359.0  263.31  4368.9  262.42
  4504.3  253.25  4553.6  252.18  4777.5  253.31  4929.6  244.96  4983.8  242.92
  4990.8  240.75  4993.6  240.25  4996.8  240.75  5013.8  244.19  5246.8  242.70
  5284.8  243.90  5332.9  245.62  5390.0  250.37  5502.0  253.94  5573.2  258.51
  5640.5  259.89  5714.7  267.24  5758.4  274.07  5818.2  287.53  5883.7  296.24
  5890.0  295.43  5913.8  297.37  5921.7  301.39  5967.0  306.46  6039.0  314.61
#Mann=12,-1,0
  4114.8    0.05       0  4153.4    0.16       0  4241.6    0.05       0
  4359.0    0.16       0  4368.9    0.05       0  4929.6    0.12       0
  4990.8    0.07       0  4996.8    0.12       0  5246.8    0.16       0
  5284.8    0.05       0  5890.0    0.08       0  5967.0    0.16       0
Bank Sta=4990.8,4996.8
Exp/Cntr=0.3,0.1

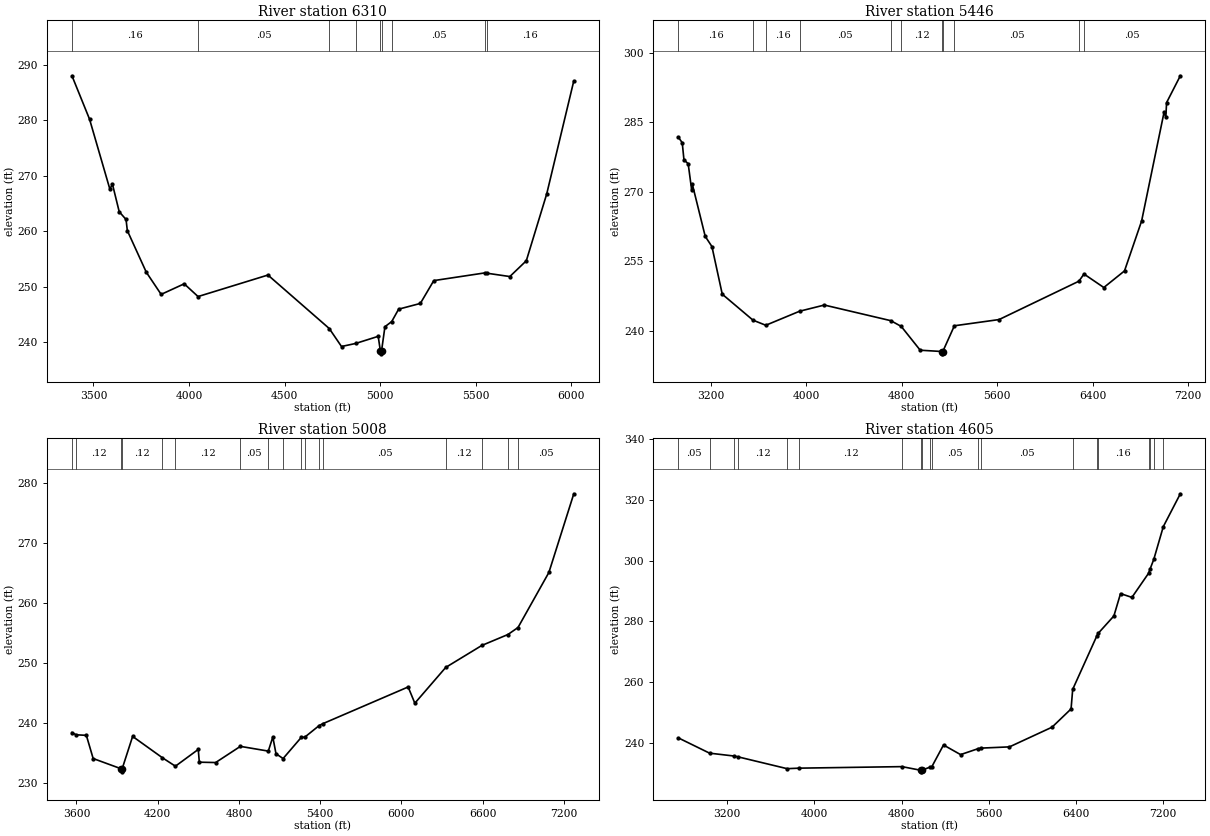
Type RM Length L Ch R = 1,6310,864,864,864
BEGIN DESCRIPTION:
UNT 173 IN UKCR 4.0
END DESCRIPTION:
XS GIS Cut Line= 4
      3681699.63     10540360.16      3682574.97     10539420.68
      3682549.61     10539110.19      3681749.59     10538460.17
#Sta/Elev= 30
  3387.5  287.99  3479.6  280.18  3585.6  267.63  3599.7  268.45  3634.9  263.52
  3670.6  262.13  3677.4  260.12  3776.6  252.64  3854.3  248.65  3975.0  250.55
  4047.5  248.26  4413.2  252.13  4734.0  242.51  4798.2  239.27  4872.4  239.82
  4990.3  241.10  5001.7  238.45  5004.4  237.95  5007.7  238.45  5025.5  242.83
  5061.0  243.76  5097.3  245.99  5210.8  247.02  5281.2  251.13  5551.2  252.53
  5557.1  252.47  5679.1  251.86  5765.4  254.70  5872.1  266.72  6013.9  287.07
#Mann=9,-1,0
  3387.5    0.16       0  4047.5    0.05       0  4734.0    0.12       0
  4872.4    0.16       0  5001.7    0.07       0  5007.7    0.16       0
  5061.0    0.05       0  5551.2    0.08       0  5557.1    0.16       0
Bank Sta=5001.7,5007.7
Exp/Cntr=0.3,0.1

Type RM Length L Ch R = 1,5446,438,438,438
BEGIN DESCRIPTION:
UNT 173 IN UKCR 3.0
END DESCRIPTION:
XS GIS Cut Line= 4
      3681719.58     10540654.41      3683264.50     10539437.31
      3683234.11     10539066.22      3681699.57     10538010.16
#Sta/Elev= 30
  2931.6  281.76  2963.1  280.59  2977.5  276.91  3012.8  276.07  3041.7  270.49
  3048.0  271.60  3155.5  260.41  3211.7  258.21  3298.2  247.94  3555.5  242.34
  3662.7  241.24  3946.0  244.27  4152.9  245.60  4709.5  242.23  4796.9  240.99
  4955.7  235.86  5138.7  235.58  5141.4  235.08  5144.7  235.58  5241.7  241.13
  5616.0  242.47  6284.3  250.74  6326.7  252.29  6492.9  249.38  6666.1  252.96
  6809.4  263.72  6997.5  287.19  7012.1  286.11  7018.5  289.25  7133.5  295.03
#Mann=11,-1,0
  2931.6    0.16       0  3555.5    0.12       0  3662.7    0.16       0
  3946.0    0.05       0  4709.5    0.16       0  4796.9    0.12       0
  5138.7    0.07       0  5144.7    0.12       0  5241.7    0.05       0
  6284.3    0.16       0  6326.7    0.05       0
Bank Sta=5138.7,5144.7
Exp/Cntr=0.3,0.1

Type RM Length L Ch R = 1,5008,403,403,403
BEGIN DESCRIPTION:
UNT 173 IN UKCR 2.0
END DESCRIPTION:
XS GIS Cut Line= 3
      3683677.92     10540446.06      3683527.92     10538958.57
      3681949.64     10537410.21
#Sta/Elev= 30
  3567.0  238.33  3598.0  237.96  3673.4  237.87  3723.7  234.00  3931.7  232.28
  3934.5  231.78  3937.7  232.28  4015.1  237.69  4235.0  234.13  4331.0  232.72
  4499.8  235.52  4507.6  233.39  4628.2  233.33  4810.7  236.03  5017.0  235.24
  5050.4  237.59  5073.8  234.80  5126.3  234.00  5259.8  237.51  5287.3  237.58
  5393.2  239.51  5421.2  239.83  6049.7  245.94  6099.1  243.23  6327.3  249.20
  6594.2  252.87  6786.6  254.69  6861.1  255.86  7089.2  265.05  7273.0  278.17
#Mann=17,-1,0
  3567.0    0.16       0  3598.0    0.12       0  3931.7    0.03       0
  3937.7    0.12       0  4235.0    0.16       0  4331.0    0.12       0
  4810.7    0.05       0  5017.0    0.16       0  5126.3    0.05       0
  5259.8    0.12       0  5287.3    0.16       0  5393.2    0.12       0
  5421.2    0.05       0  6327.3    0.12       0  6594.2    0.05       0
  6786.6     0.1       0  6861.1    0.05       0
Bank Sta=3931.7,3937.7
Exp/Cntr=0.3,0.1

Type RM Length L Ch R = 1,4605,0,0,0
BEGIN DESCRIPTION:
UNT 173 IN UKCR 1.0
END DESCRIPTION:
XS GIS Cut Line= 3
      3683888.52     10540970.28      3683865.42     10538862.73
      3682865.43     10536571.08
#Sta/Elev= 30
  2751.9  241.78  3037.3  236.79  3266.3  235.83  3299.7  235.57  3749.3  231.70
  3861.3  231.87  4804.0  232.37  4978.8  231.16  4981.5  230.66  4984.8  231.16
  5059.2  232.18  5077.7  232.31  5185.4  239.47  5342.4  236.31  5502.0  238.25
  5532.9  238.45  5791.0  238.85  6181.9  245.31  6356.7  251.30  6371.6  257.72
  6591.6  275.12  6605.4  276.09  6749.9  281.81  6810.9  289.15  6915.4  287.90
  7067.8  295.79  7082.2  297.21  7116.5  300.41  7203.7  311.13  7359.9  321.90
#Mann=20,-1,0
  2751.9    0.05       0  3037.3    0.12       0  3266.3    0.16       0
  3299.7    0.12       0  3749.3    0.16       0  3861.3    0.12       0
  4804.0    0.05       0  4978.8    0.03       0  4984.8    0.05       0
  5059.2    0.07       0  5077.7    0.05       0  5502.0    0.07       0
  5532.9    0.05       0  6371.6    0.16       0  6591.6    0.05       0
  6605.4    0.16       0  7067.8    0.12       0  7082.2    0.16       0
  7116.5    0.12       0  7203.7    0.16       0
Bank Sta=4978.8,4984.8
Exp/Cntr=0.3,0.1

Chan Stop Cuts=-1