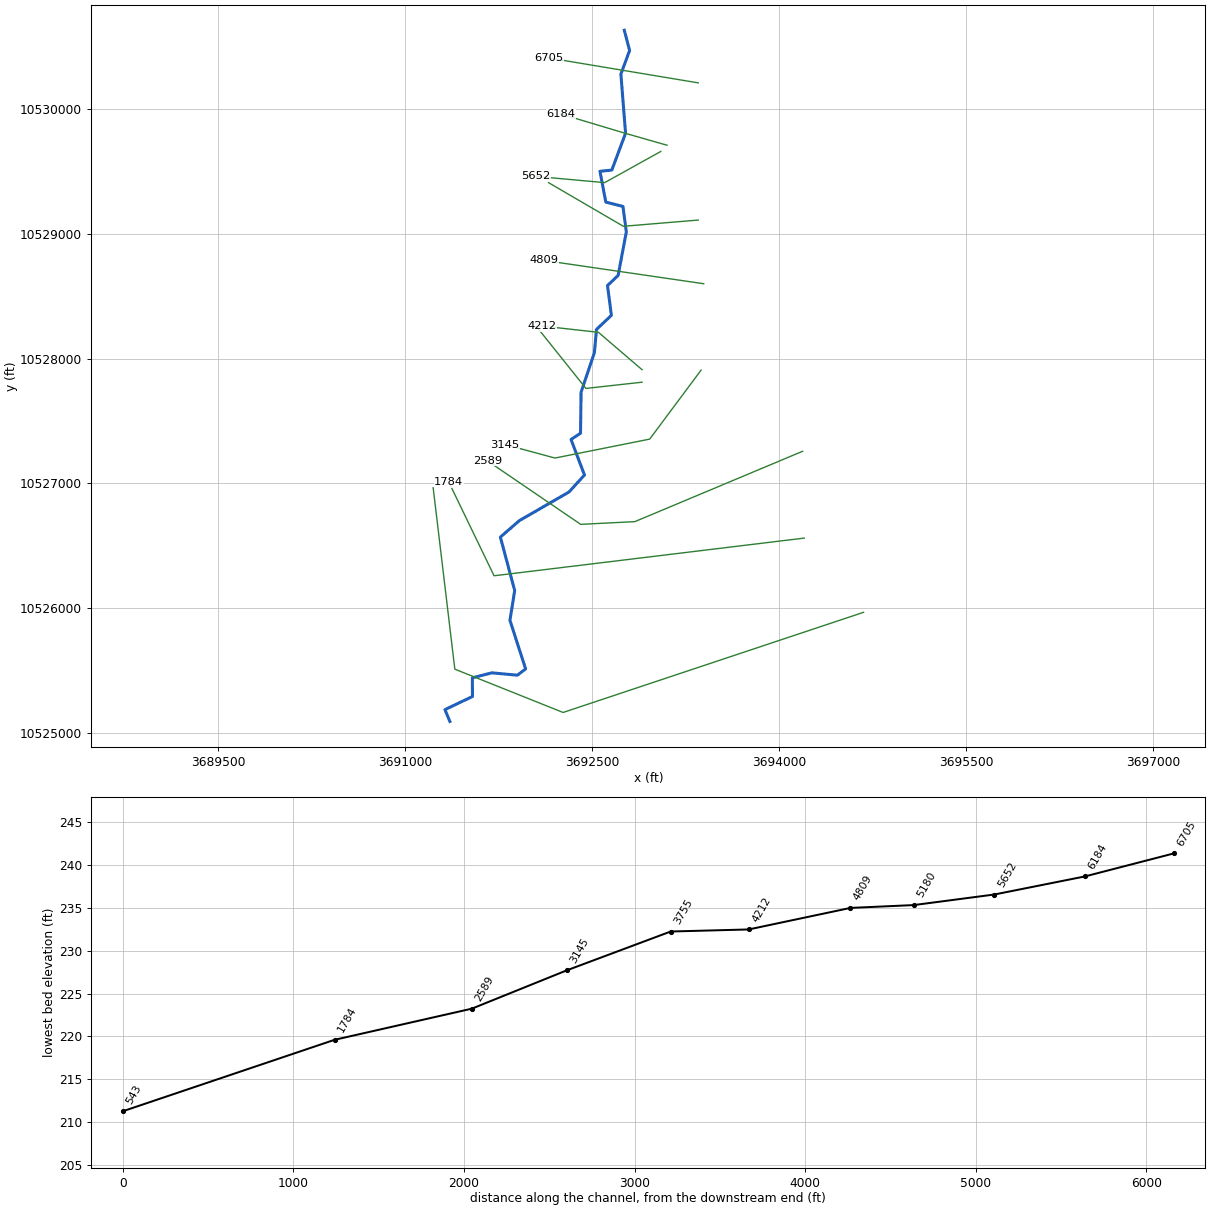
--- UNT 174 IN UKCR.prj (project) ---

Proj Title=UNT 174 IN UKCR Base Level Engineering
Current Plan=p01
Default Exp/Contr=0.3,0.1
English Units
Geom File=g01
Flow File=f01
Plan File=p01
Y Axis Title=Elevation
X Axis Title(PF)=Main Channel Distance
X Axis Title(XS)=Station
BEGIN DESCRIPTION:
UNT 174 IN UKCR
END DESCRIPTION:
DSS Export Rating Curves= 0
DSS Export Rating Curve Sorted= 0
DSS Export Volume Flow Curves= 0
DXF OffsetX= 0
DXF OffsetY= 0
DXF ScaleX= 1
DXF ScaleY= 10

--- UNT 174 IN UKCR.p01 (plan) ---

Plan Title=Multiple Run
Short Identifier=Multiple
Geom File=g01
Flow File=f01
Subcritical Flow
K Sum by GR= 0
Std Step Tol= 0.01
Critical Tol= 0.01
Num of Std Step Trials= 20
Max Error Tol= 0.3
Flow Tol Ratio= 0.001
Split Flow NTrial= 30
Split Flow Tol= 0.02
Split Flow Ratio= 0.02
Log Output Level= 0
Friction Slope Method= 1
Unsteady Friction Slope Method= 2
Unsteady Bridges Friction Slope Method= 1
Parabolic Critical Depth
Global Vel Dist=  1 , 1 , 1
Global Log Level= 0
CheckData=True
Encroach Param= -1, 0, 0, 0
BEGIN DESCRIPTION:
Multiple Run
END DESCRIPTION:

--- UNT 174 IN UKCR.f01 (steady flow) ---

Flow Title=Multiple
Number of Profiles=7
Profile Names=10-year,25-year,50-year,1pct_min,100-year,1pct_plu,500-year
River Rch & RM= UNT 174 IN UKCR,Reach-1,6705
     656     904    1111    1005    1359    1837    2040
Boundary for River Rch & Prof#=UNT 174 IN UKCR,Reach-1,1
Up Type=0
Dn Type=3
Dn Slope=0.005
Boundary for River Rch & Prof#=UNT 174 IN UKCR,Reach-1,2
Up Type=0
Dn Type=3
Dn Slope=0.005
Boundary for River Rch & Prof#=UNT 174 IN UKCR,Reach-1,3
Up Type=0
Dn Type=3
Dn Slope=0.005
Boundary for River Rch & Prof#=UNT 174 IN UKCR,Reach-1,4
Up Type=0
Dn Type=3
Dn Slope=0.005
Boundary for River Rch & Prof#=UNT 174 IN UKCR,Reach-1,5
Up Type=0
Dn Type=3
Dn Slope=0.005
Boundary for River Rch & Prof#=UNT 174 IN UKCR,Reach-1,6
Up Type=0
Dn Type=3
Dn Slope=0.005
Boundary for River Rch & Prof#=UNT 174 IN UKCR,Reach-1,7
Up Type=0
Dn Type=3
Dn Slope=0.005

--- UNT 174 IN UKCR.g01 (geometry) ---

Geom Title=Existing Conditions
Program Version=4.10

River Reach=UNT 174 IN UKCR ,Reach-1
Reach XY= 30
        3692757.       10530632.      3692799.75       10530470.
      3692729.75       10530280.      3692767.25       10529806.
        3692657.       10529511.        3692562.       10529501.
      3692608.75       10529254.      3692746.25       10529219.
       3692773.5       10529016.       3692707.5       10528666.
       3692622.5       10528585.       3692653.5       10528346.
        3692534.       10528233.      3692517.25       10528046.
       3692410.5       10527730.      3692406.25       10527401.
        3692330.       10527351.      3692437.75       10527066.
        3692314.       10526930.      3691915.25       10526700.
       3691763.5       10526568.      3691878.25       10526140.
      3691840.25       10525901.        3691966.       10525511.
       3691899.5       10525461.        3691695.       10525480.
      3691539.25       10525440.       3691539.5       10525290.
        3691319.       10525185.       3691358.5       10525090.

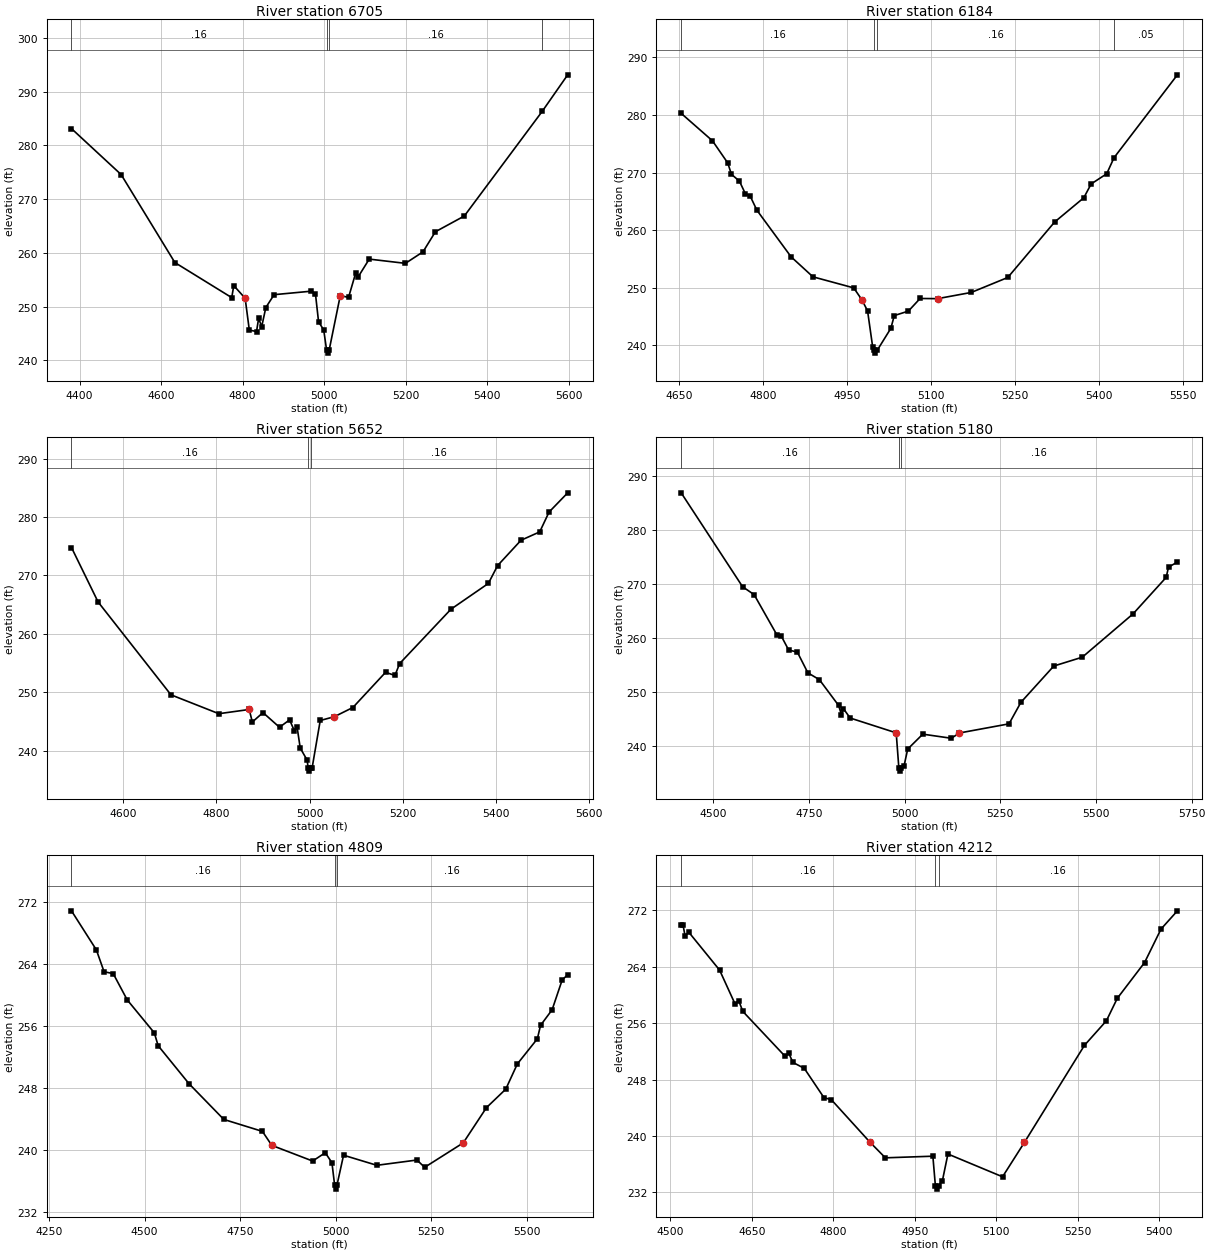
Type RM Length L Ch R = 1 ,6705    ,521,521,521
BEGIN DESCRIPTION:
UNT 174 IN UKCR 11.0
END DESCRIPTION:
XS GIS Cut Line= 3
      3693349.64     10530210.18      3692749.61     10530310.19
       3692149.6     10530410.19
#Sta/Elev= 30
  4380.3  283.12    4502  274.57  4633.8  258.19  4773.2  251.66  4778.2   253.9
  4806.1  251.54  4816.3  245.62    4834  245.35  4839.1   247.8  4846.7  246.27
  4856.8  249.82  4877.1  252.21  4968.3  252.86  4978.5  252.34  4986.1  247.15
  4998.7  245.66  5005.9  241.83  5008.6  241.33  5011.9  241.83  5039.3  252.04
  5059.6   251.7  5077.3   256.3  5082.4  255.43  5110.3  258.83    5199  258.04
  5242.1  260.18  5272.5  263.92  5343.4  266.85  5534.3  286.32  5596.9  293.13
#Mann= 4 ,-1 , 0
  4380.3     .16       0  5005.9     .07       0  5011.9     .16       0
  5534.3     .05       0
Bank Sta=4806.1,5039.3
XS Rating Curve= 0 ,0
Exp/Cntr=0.3,0.1

Type RM Length L Ch R = 1 ,6184    ,532,532,532
BEGIN DESCRIPTION:
UNT 174 IN UKCR 10.0
END DESCRIPTION:
XS GIS Cut Line= 3
      3693099.56      10529710.2      3692749.61     10529810.19
      3692249.58      10529960.2
#Sta/Elev= 30
    4654  280.29  4709.9  275.52  4737.2  271.67  4743.7  269.71    4758  268.52
  4768.4  266.37  4777.5  265.86  4789.2  263.47  4850.3  255.37  4889.3   251.9
  4962.1  249.98  4976.4  247.95  4986.8  245.99  4995.9  239.74  4998.1  239.15
  5000.8  238.65  5004.1  239.15  5028.4  242.96  5034.5  245.17  5059.7  245.95
  5080.6  248.14  5111.9  248.11    5172  249.19  5237.2  251.79  5320.7  261.41
  5372.9  265.63    5386  268.03  5413.8   269.8  5426.8  272.58    5540  286.98
#Mann= 4 ,-1 , 0
    4654     .16       0  4998.1     .07       0  5004.1     .16       0
  5426.8     .05       0
Bank Sta=4976.4,5111.9
XS Rating Curve= 0 ,0
Exp/Cntr=0.3,0.1

Type RM Length L Ch R = 1 ,5652    ,472,472,472
BEGIN DESCRIPTION:
UNT 174 IN UKCR 9.0
END DESCRIPTION:
XS GIS Cut Line= 3
       3693049.6     10529660.18      3692599.61     10529410.19
      3692049.65     10529460.19
#Sta/Elev= 30
  4488.2  274.78  4545.4  265.47  4702.1  249.59  4805.1  246.36  4870.3  247.08
  4877.1  244.94    4900  246.55  4935.5  244.04  4957.2  245.31  4967.5  243.43
  4973.2  244.13  4980.1  240.48    4995  238.41  4997.1  237.04  4999.9  236.54
  5003.1  237.04  5005.5  237.04  5023.1   245.2  5053.2  245.84  5093.3  247.42
  5163.6  253.44  5183.7   252.9  5193.8  254.93  5304.2  264.23  5384.5  268.63
  5404.6   271.7  5454.8  276.02    5495  277.45  5515.1  280.84  5555.2  284.13
#Mann= 3 ,-1 , 0
  4488.2     .16       0  4997.1     .07       0  5003.1     .16       0
Bank Sta=4870.3,5053.2
XS Rating Curve= 0 ,0
Exp/Cntr=0.3,0.1

Type RM Length L Ch R = 1 ,5180    ,371,371,371
BEGIN DESCRIPTION:
UNT 174 IN UKCR 8.0
END DESCRIPTION:
XS GIS Cut Line= 3
      3693349.56     10529110.18      3692749.61     10529060.19
      3692149.57     10529410.21
#Sta/Elev= 30
  4416.1  286.87  4576.6  269.47  4606.7  268.01  4666.9  260.47    4677  260.43
    4697  257.74  4719.6  257.37  4747.2  253.52  4777.3  252.25  4827.5  247.48
    4835  245.76    4840   246.9  4857.6  245.15    4978   242.4    4985  235.81
  4987.8  235.31    4991  235.81  4998.1  236.17  5008.1   239.4  5047.5  242.16
  5121.9   241.4  5143.4  242.38  5272.8  244.07  5303.8  248.05  5389.8  254.78
  5464.3  256.42    5597  264.45  5683.4   271.2  5689.6  273.11  5712.8  274.04
#Mann= 3 ,-1 , 0
  4416.1     .16       0    4985     .07       0    4991     .16       0
Bank Sta=4978,5143.4
XS Rating Curve= 0 ,0
Exp/Cntr=0.3,0.1

Type RM Length L Ch R = 1 ,4809    ,597,597,597
BEGIN DESCRIPTION:
UNT 174 IN UKCR 7.0
END DESCRIPTION:
XS GIS Cut Line= 2
        3693394.     10528599.61      3692109.22     10528787.12
#Sta/Elev= 30
  4308.7  270.84  4373.8  265.81    4394  262.99  4417.9  262.75  4454.6  259.36
  4525.4  255.12  4535.5  253.46  4616.3  248.56  4707.3  243.96  4808.3  242.42
  4832.8  240.62  4939.7   238.6  4972.8  239.67  4990.2  238.38  4997.3  235.48
  5000.1  234.98  5003.3  235.48  5020.6  239.35  5107.7  238.05  5212.6  238.73
  5232.8  237.79  5333.8  240.94  5394.5  245.48    5445  247.86  5475.3  251.11
  5527.7  254.35    5536  256.08  5566.3  258.09  5592.6  261.93  5607.1  262.61
#Mann= 3 ,-1 , 0
  4308.7     .16       0  4997.3     .07       0  5003.3     .16       0
Bank Sta=4832.8,5333.8
XS Rating Curve= 0 ,0
Exp/Cntr=0.3,0.1

Type RM Length L Ch R = 1 ,4212    ,457,457,457
BEGIN DESCRIPTION:
UNT 174 IN UKCR 6.0
END DESCRIPTION:
XS GIS Cut Line= 3
      3692899.64     10527910.17      3692549.61     10528210.19
      3692099.59     10528260.19
#Sta/Elev= 30
  4519.7  269.99    4523  269.99  4526.9  268.36  4533.5  268.93  4590.5  263.53
  4619.1   258.7  4625.6  259.21  4633.3  257.67  4711.3  251.29  4717.8  251.75
  4725.5  250.44  4746.4   249.6  4782.6  245.45  4796.3  245.15  4867.1  239.15
  4895.7  236.91  4983.2  237.14  4987.8  232.97  4990.5  232.47  4993.8  232.97
  5000.8  233.68  5010.9  237.45  5111.5  234.22  5151.8   239.1  5262.4  252.87
  5302.7  256.34  5322.8  259.53  5373.1  264.61  5403.3  269.35  5433.5  271.94
#Mann= 3 ,-1 , 0
  4519.7     .16       0  4987.8     .07       0  4993.8     .16       0
Bank Sta=4867.1,5151.8
XS Rating Curve= 0 ,0
Exp/Cntr=0.3,0.1

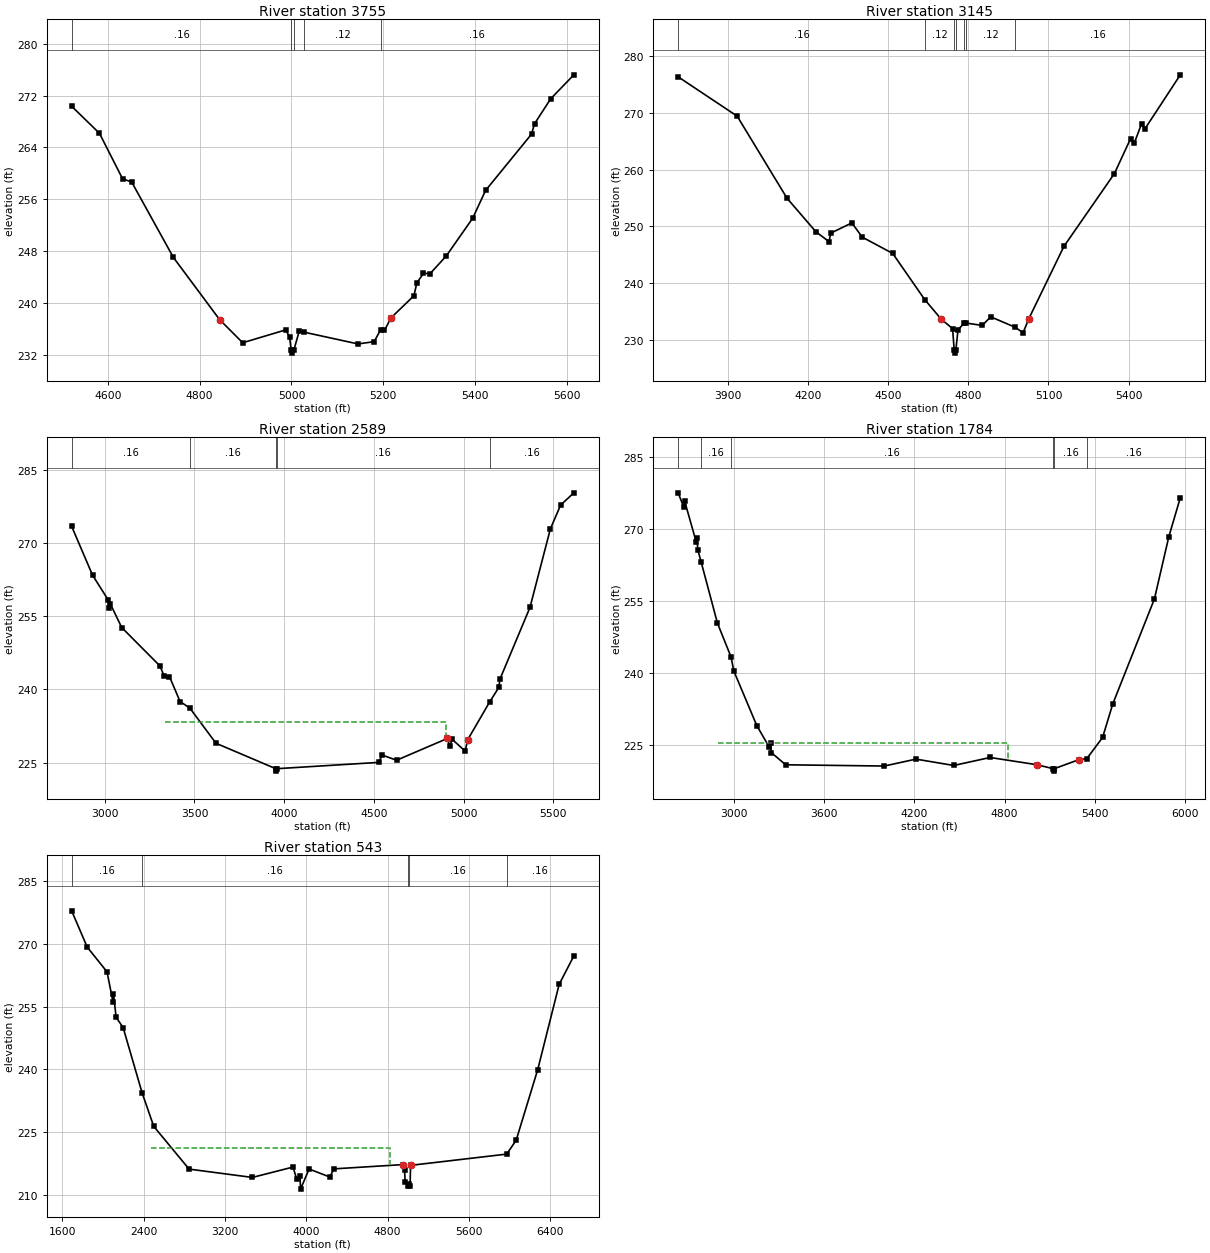
Type RM Length L Ch R = 1 ,3755    ,610,610,610
BEGIN DESCRIPTION:
UNT 174 IN UKCR 5.0
END DESCRIPTION:
XS GIS Cut Line= 3
      3692899.65     10527810.19      3692449.61     10527760.19
      3692049.62     10528260.17
#Sta/Elev= 30
  4521.5  270.35  4581.9  266.18  4632.2  259.17  4652.3  258.63  4742.9  247.01
  4843.5  237.41  4893.8  233.83  4987.9  235.83  4995.9  234.66  4999.3  232.73
  5002.1  232.23  5005.3  232.73  5016.7  235.58  5027.7  235.46  5144.8  233.65
    5180     234    5194  235.84  5202.4  235.73  5216.8  237.69  5266.5  241.09
  5272.9  243.08  5287.3  244.55  5301.7   244.5  5336.9  247.23  5394.5  253.07
  5422.5  257.35  5522.6  266.05    5529  267.64  5564.2   271.5  5614.6   275.2
#Mann= 5 ,-1 , 0
  4521.5     .16       0  4999.3     .07       0  5005.3     .16       0
  5027.7     .12       0    5194     .16       0
Bank Sta=4843.5,5216.8
XS Rating Curve= 0 ,0
Exp/Cntr=0.3,0.1

Type RM Length L Ch R = 1 ,3145    ,556,556,556
BEGIN DESCRIPTION:
UNT 174 IN UKCR 4.0
END DESCRIPTION:
XS GIS Cut Line= 4
      3693373.13     10527907.33      3692960.82     10527353.96
      3692201.27     10527202.05      3691799.76     10527310.57
#Sta/Elev= 30
    3713  276.33  3934.1  269.41    4121  254.95  4228.2   249.1  4278.2  247.31
  4284.5  248.82  4363.7  250.62  4402.3  248.12  4516.5  245.25  4636.4  237.13
  4698.9  233.64  4740.9  232.02  4746.9   228.2  4749.6   227.7  4752.9   228.2
  4761.3  231.83  4784.2  232.96  4792.6  232.99  4851.8  232.57  4883.6  234.09
  4975.4  232.25  5004.8  231.28  5026.4  233.77  5157.8  246.49  5346.7  259.29
  5407.3  265.44  5421.3  264.67  5448.7   268.1  5461.1  267.17  5593.6  276.68
#Mann= 7 ,-1 , 0
    3713     .16       0  4636.4     .12       0  4746.9     .07       0
  4752.9     .12       0  4784.2     .16       0  4792.6     .12       0
  4975.4     .16       0
Bank Sta=4698.9,5026.4
XS Rating Curve= 0 ,0
Exp/Cntr=0.3,0.1

Type RM Length L Ch R = 1 ,2589    ,805,805,805
BEGIN DESCRIPTION:
UNT 174 IN UKCR 3.0
END DESCRIPTION:
XS GIS Cut Line= 4
      3694186.95     10527256.31      3692841.46     10526692.07
      3692407.43     10526670.37      3691658.71     10527180.37
#Sta/Elev= 30
  2815.2  273.41  2931.6   263.4  3018.3  258.36  3024.4  256.59  3029.8  257.59
  3094.3  252.67  3307.5  244.79  3331.3  242.69  3360.5  242.62  3419.6   237.5
  3473.8  236.17  3619.9  228.95  3953.1  223.74  3955.8  223.24  3959.1  223.74
  4526.4  225.03  4546.4  226.53  4626.5  225.47  4909.3  229.93  4923.9  228.33
  4936.3  229.77  5008.6  227.34  5023.1  229.68  5145.7  237.43  5196.6  240.39
  5202.6  242.07  5370.1  256.78  5483.9  272.89    5541  277.76  5614.7  280.27
#Mann= 5 ,-1 , 0
  2815.2     .16       0  3473.8     .16       0  3953.1     .07       0
  3959.1     .16       0  5145.7     .16       0
#XS Ineff= 1 ,-1
 3333.24 4904.26   233.4
Permanent Ineff=
       F
Bank Sta=4909.3,5023.1
XS Rating Curve= 0 ,0
Exp/Cntr=0.3,0.1

Type RM Length L Ch R = 1 ,1784    ,1241,1241,1241
BEGIN DESCRIPTION:
UNT 174 IN UKCR 2.0
END DESCRIPTION:
XS GIS Cut Line= 3
      3694199.64     10526560.19      3691712.99     10526258.04
       3691349.6     10527010.22
#Sta/Elev= 30
    2628  277.57  2666.4  274.53  2671.4  275.85  2748.1  267.38  2753.2  268.13
    2759  265.68  2781.7  263.11  2889.9   250.4    2980  243.39  2998.4  240.47
  3151.9  229.05  3232.4  224.71  3242.5  225.39  3248.7  223.45  3343.3  220.93
  3999.5  220.67  4209.6  222.11  4461.4  220.79  4703.2  222.45  5015.5  220.94
  5123.3  220.11    5126  219.61  5129.3  220.11  5293.2  221.99  5346.6  222.22
  5451.4  226.62  5519.2  233.61    5796  255.46  5891.9  268.43  5968.3  276.55
#Mann= 6 ,-1 , 0
    2628      .1       0  2781.7     .16       0    2980     .16       0
  5123.3     .07       0  5129.3     .16       0  5346.6     .16       0
#XS Ineff= 1 ,-1
 2895.74 4824.72  225.42
Permanent Ineff=
       F
Bank Sta=5015.5,5293.2
XS Rating Curve= 0 ,0
Exp/Cntr=0.3,0.1

Type RM Length L Ch R = 1 ,543     ,0,0,0
BEGIN DESCRIPTION:
UNT 174 IN UKCR 1.0
END DESCRIPTION:
XS GIS Cut Line= 4
      3694675.22     10525965.07      3692266.37     10525162.12
      3691398.32     10525509.34      3691224.71     10526963.34
#Sta/Elev= 30
  1693.1   277.9  1846.1  269.22  2041.1  263.29  2099.1  256.15  2104.3  258.03
  2130.7  252.39  2199.2  249.97  2385.1   234.4  2500.1  226.32    2848  216.08
  3469.9  214.09  3869.9  216.57  3906.8  213.64  3938.4  214.42    3944  211.29
    4028   216.1  4232.2  214.19  4272.3  216.14  4950.4  217.16    4967  215.93
  4972.4  213.09  5004.2  212.14    5015  212.45  5020.9  212.12  5026.3  216.98
  5971.4  219.67  6064.3  222.99  6275.8  239.85  6487.3  260.31  6631.5   267.1
#Mann= 5 ,-1 , 0
  1693.1     .16       0  2385.1     .16       0  5004.2     .07       0
    5015     .16       0  5971.4     .16       0
#XS Ineff= 1 ,-1
 2469.32 4828.41  221.21
Permanent Ineff=
       F
Bank Sta=4950.4,5026.3
XS Rating Curve= 0 ,0
Exp/Cntr=0.3,0.1

Chan Stop Cuts=-1
Use User Specified Reach Order=0
Composite Channel Slope=5