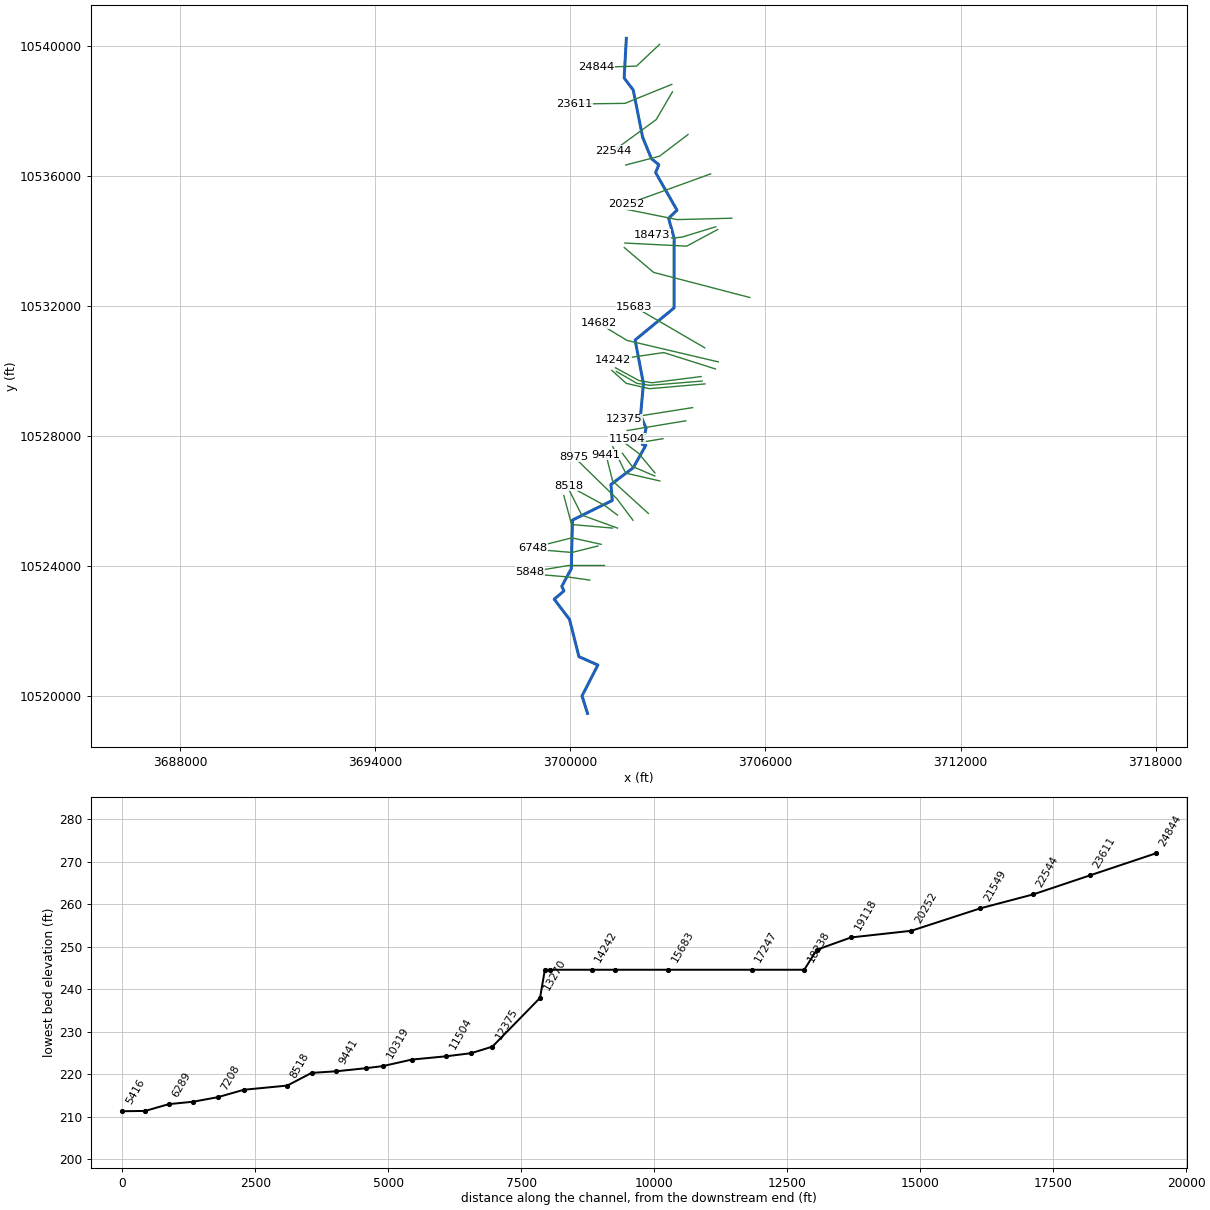
--- UNT 176 IN UKCR.prj (project) ---

Proj Title=UNT 176 IN UKCR Base Level Engineering
Current Plan=p01
Default Exp/Contr=0.3,0.1
English Units
Geom File=g01
Flow File=f01
Plan File=p01
Y Axis Title=Elevation
X Axis Title(PF)=Main Channel Distance
X Axis Title(XS)=Station
BEGIN DESCRIPTION:
UNT 176 IN UKCR
END DESCRIPTION:
DSS Export Rating Curves= 0
DSS Export Rating Curve Sorted= 0
DSS Export Volume Flow Curves= 0
DXF OffsetX= 0
DXF OffsetY= 0
DXF ScaleX= 1
DXF ScaleY= 10

--- UNT 176 IN UKCR.p01 (plan) ---

Plan Title=Multiple Run
Short Identifier=Multiple
Geom File=g01
Flow File=f01
Subcritical Flow
K Sum by GR= 0
Std Step Tol= 0.01
Critical Tol= 0.01
Num of Std Step Trials= 20
Max Error Tol= 0.3
Flow Tol Ratio= 0.001
Split Flow NTrial= 30
Split Flow Tol= 0.02
Split Flow Ratio= 0.02
Log Output Level= 0
Friction Slope Method= 1
Unsteady Friction Slope Method= 2
Unsteady Bridges Friction Slope Method= 1
Parabolic Critical Depth
Global Vel Dist=  1 , 1 , 1
Global Log Level= 0
CheckData=True
Encroach Param= -1, 0, 0, 0
BEGIN DESCRIPTION:
Multiple Run
END DESCRIPTION:

--- UNT 176 IN UKCR.f01 (steady flow) ---

Flow Title=Multiple
Program Version=4.10
Number of Profiles= 7
Profile Names=10-year,25-year,50-year,1pct_min,100-year,1pct_plu,500-year
River Rch & RM=UNT 176 IN UKCR,Reach-1         ,24844
    1175    1649    2053    1874    2534    3427    3879
River Rch & RM=UNT 176 IN UKCR,Reach-1         ,20252
    1289    1809    2252    2053    2776    3755    4241
River Rch & RM=UNT 176 IN UKCR,Reach-1         ,14242
    1550    2193    2745    2515    3402    4601    5251
River Rch & RM=UNT 176 IN UKCR,Reach-1         ,10856
    1728    2452    3075    2821    3815    5160    5904
River Rch & RM=UNT 176 IN UKCR,Reach-1         ,6748
    1919    2724    3414    3130    4233    5725    6541
Boundary for River Rch & Prof#=UNT 176 IN UKCR,Reach-1         , 1
Up Type= 0
Dn Type= 3
Dn Slope=0.001
Boundary for River Rch & Prof#=UNT 176 IN UKCR,Reach-1         , 2
Up Type= 0
Dn Type= 3
Dn Slope=0.001
Boundary for River Rch & Prof#=UNT 176 IN UKCR,Reach-1         , 3
Up Type= 0
Dn Type= 3
Dn Slope=0.001
Boundary for River Rch & Prof#=UNT 176 IN UKCR,Reach-1         , 4
Up Type= 0
Dn Type= 3
Dn Slope=0.001
Boundary for River Rch & Prof#=UNT 176 IN UKCR,Reach-1         , 5
Up Type= 0
Dn Type= 3
Dn Slope=0.001
Boundary for River Rch & Prof#=UNT 176 IN UKCR,Reach-1         , 6
Up Type= 0
Dn Type= 3
Dn Slope=0.001
Boundary for River Rch & Prof#=UNT 176 IN UKCR,Reach-1         , 7
Up Type= 0
Dn Type= 3
Dn Slope=0.001
DSS Import GetInterval= 0
DSS Import GetPeak= 0
DSS Import FillOption= 0

--- UNT 176 IN UKCR.g01 (geometry) ---

Geom Title=Existing Conditions
Program Version=4.10

River Reach=UNT 176 IN UKCR ,Reach-1
Reach XY= 30
       3701722.5       10540221.      3701654.75       10539001.
        3701934.       10538633.       3702223.5       10537180.
        3702493.       10536522.        3702722.       10536333.
        3702623.       10536092.      3703279.75       10534937.
        3703022.       10534687.      3703192.25       10534080.
       3703189.5       10531930.      3701992.25       10530943.
      3702248.51     10529598.84        3702160.       10528625.
      3702329.75       10528230.      3702212.75       10527731.
      3702322.75       10527708.        3701932.       10527014.
       3701249.5       10526500.       3701289.5       10526010.
        3700067.       10525407.        3700029.       10523911.
      3699736.75       10523368.        3699804.       10523228.
       3699503.5       10522973.      3699975.25       10522353.
      3700264.25       10521207.      3700846.75       10520949.
        3700360.       10520000.      3700527.75       10519462.

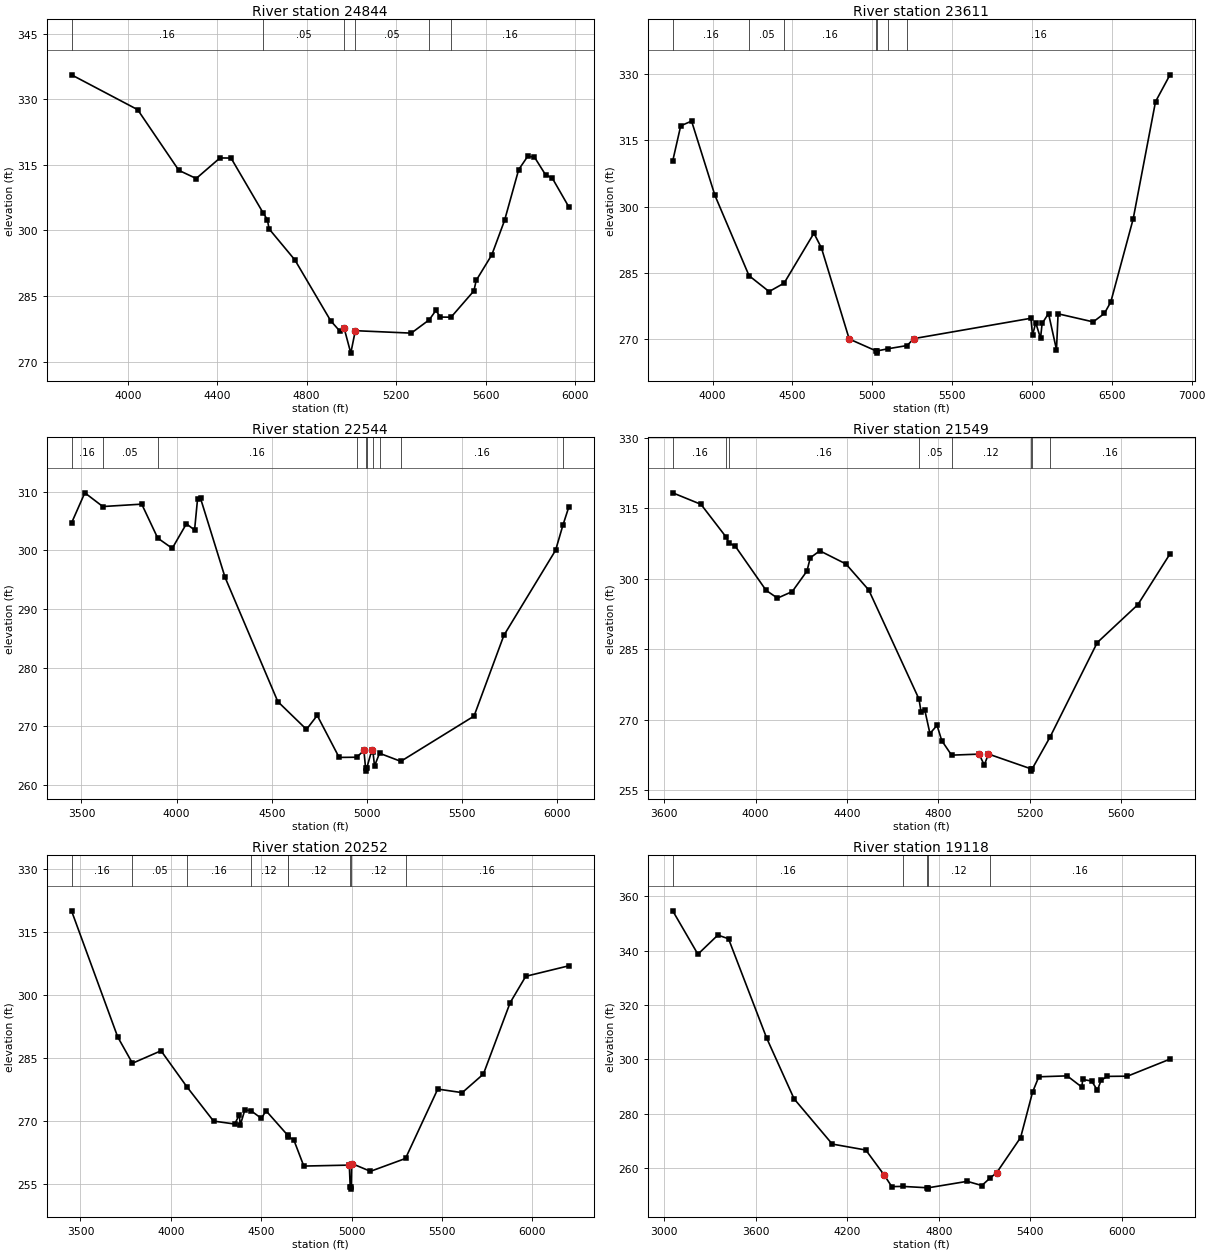
Type RM Length L Ch R = 1 ,24844   ,1233,1233,1233
BEGIN DESCRIPTION:
UNT 176 IN UKCR 20.0
END DESCRIPTION:
XS GIS Cut Line= 3
      3702743.94     10540033.99      3702035.64     10539367.36
      3700785.61     10539325.69
#Sta/Elev= 30
  3748.6  335.57  4044.2  327.61  4228.3  313.75    4306  311.88  4412.4  316.58
  4461.8  316.55  4604.5  304.09  4624.4  302.46  4631.7  300.38  4747.3  293.27
  4907.4  279.37  4947.4  277.06  4967.4   277.7  4997.2  271.98  5017.5  277.11
  5267.6  276.55  5347.7  279.58  5377.7  281.73  5397.7  280.22  5445.5  280.19
  5547.8  286.21  5557.8  288.58  5627.8  294.44  5684.8  302.31  5747.9  313.91
  5787.9  316.92  5817.9  316.81  5867.9  312.74    5898  311.98    5972   305.4
#Mann= 6 ,-1 , 0
  3748.6     .16       0  4604.5     .05       0  4967.4    .035       0
  5017.5     .05       0  5347.7     .05       0  5445.5     .16       0
Bank Sta=4967.4,5017.5
XS Rating Curve= 0 ,0
Exp/Cntr=0.3,0.1

Type RM Length L Ch R = 1 ,23611   ,1067,1067,1067
BEGIN DESCRIPTION:
Mapping XS 4b97582e
END DESCRIPTION:
XS GIS Cut Line= 3
        3703119.     10538804.86      3701681.48     10538221.52
      3700118.99     10538200.69
#Sta/Elev= 30
  3750.2  310.35  3800.3  318.32  3868.3   319.4  4014.6  302.55  4228.2  284.36
  4353.9  280.76    4448  282.68  4634.5  293.99  4681.6  290.64 4855.45  270.01
  5024.1  267.31  5026.9  266.81  5030.1  267.31  5098.2   267.8  5218.1  268.53
  5260.1   270.1  5993.5  274.71  6003.5  270.84  6023.5   273.7  6053.5  270.19
  6063.5  273.53  6103.5  275.79  6153.5  267.59  6163.5  275.72  6383.5  273.89
  6453.5  275.81  6493.5   278.4  6633.6   297.2  6773.6  323.79  6864.2  329.88
#Mann= 7 ,-1 , 0
  3750.2     .16       0  4228.2     .05       0    4448     .16       0
  5024.1     .07       0  5030.1     .16       0  5098.2     .05       0
  5218.1     .16       0
Bank Sta=4855.45,5260.1
XS Rating Curve= 0 ,0
Exp/Cntr=0.3,0.1

Type RM Length L Ch R = 1 ,22544   ,995,995,995
BEGIN DESCRIPTION:
Mapping XS 9730cc97
END DESCRIPTION:
XS GIS Cut Line= 3
      3703139.83     10538575.72      3702639.81     10537721.52
       3701328.7      10536764.2
#Sta/Elev= 30
  3447.7  304.66  3517.6  309.81    3612  307.47  3816.7  307.88  3900.6  302.09
    3977  300.34  4051.4  304.53  4094.3  303.46    4110  308.78  4125.7  308.86
  4254.6  295.38  4531.8  274.19  4682.4  269.45  4738.8  271.83  4853.9  264.67
  4947.1   264.7 4984.12  265.87    4993  262.83  4995.8  262.33    4999  262.83
  5025.3  265.88    5032  265.55    5040   263.2  5066.2  265.38    5178     264
  5562.9  271.72  5719.7  285.49  5991.5  300.01  6029.5  304.24  6060.9  307.39
#Mann= 10 ,-1 , 0
  3447.7     .16       0    3612     .05       0  3900.6     .16       0
  4947.1     .08       0    4993     .07       0    4999     .08       0
    5032     .05       0  5066.2     .12       0    5178     .16       0
  6029.5      .1       0
Bank Sta=4984.12,5025.3
XS Rating Curve= 0 ,0
Exp/Cntr=0.3,0.1

Type RM Length L Ch R = 1 ,21549   ,1297,1297,1297
BEGIN DESCRIPTION:
Mapping XS 157dddde
END DESCRIPTION:
XS GIS Cut Line= 3
      3703618.94     10537263.16      3702743.98     10536596.52
      3701703.45     10536325.99
#Sta/Elev= 30
  3637.6  318.28  3761.2  315.83  3871.3  308.86  3883.9  307.57  3910.9  306.95
  4046.1  297.52  4095.9  295.87  4160.4  297.26  4224.8  301.63  4239.3  304.45
    4281  305.94  4395.3  303.14  4495.1   297.6  4714.9  274.38  4723.8  271.69
  4740.2  272.04  4762.8  267.05  4793.8   268.8  4814.4  265.54  4857.4  262.45
    4978  262.67  5000.4  260.33  5018.5  262.69  5204.1  259.55  5206.8  259.05
  5210.1  259.55  5287.8  266.27  5494.6  286.41    5672  294.47  5812.7  305.28
#Mann= 8 ,-1 , 0
  3637.6     .16       0  3871.3      .1       0  3883.9     .16       0
  4714.9     .05       0  4857.4     .12       0  5204.1     .07       0
  5210.1     .12       0  5287.8     .16       0
Bank Sta=4978,5018.5
XS Rating Curve= 0 ,0
Exp/Cntr=0.3,0.1

Type RM Length L Ch R = 1 ,20252   ,1134,1134,1134
BEGIN DESCRIPTION:
Mapping XS 71a22c57
END DESCRIPTION:
XS GIS Cut Line= 2
      3704314.42     10536052.41      3701728.04     10535115.06
#Sta/Elev= 30
  3450.4  320.02  3705.9  289.99  3787.4  283.73  3945.6   286.7  4089.1  278.09
    4236  269.96  4353.2  269.26  4378.5  271.46  4383.8  268.98  4409.1   272.6
  4442.2  272.46    4501  270.59  4526.3  272.43  4646.2  266.59    4649  266.16
  4679.5  265.55  4735.4  259.25  4987.2  259.48  4992.1  254.26  4994.9  253.76
  4998.1  254.26  5000.4  259.86  5104.2     258    5298  261.06  5476.4  277.58
  5611.7  276.73  5728.9  281.15  5876.8  298.14  5963.3  304.43  6201.4  306.93
#Mann= 9 ,-1 , 0
  3450.4     .16       0  3787.4     .05       0  4089.1     .16       0
  4442.2     .12       0  4646.2     .16       0    4649     .12       0
  4992.1     .07       0  4998.1     .12       0    5298     .16       0
Bank Sta=4987.2,5000.4
XS Rating Curve= 0 ,0
Exp/Cntr=0.3,0.1

Type RM Length L Ch R = 1 ,19118   ,645,645,645
BEGIN DESCRIPTION:
Mapping XS ec5a5b9c
END DESCRIPTION:
XS GIS Cut Line= 3
      3704965.46     10534689.58      3703290.16     10534646.18
      3701736.34     10534958.68
#Sta/Elev= 30
  3054.5  354.61  3219.7  338.64  3350.5  345.68  3420.5  344.33  3670.6  307.78
  3850.6  285.41  4100.7  268.77  4320.8  266.58  4440.8  257.41  4490.8  253.12
  4563.2  253.19  4725.1  252.69  4727.9  252.19  4731.1  252.69  4985.9  255.06
  5081.6  253.51    5137  256.35  5178.2  258.18  5335.9  271.18  5414.3   287.9
  5455.1  293.53  5641.1  293.87  5737.7  289.72  5742.8  292.55  5801.9  291.97
  5839.4  288.57  5863.2   292.2    5904  293.68  6036.6  293.76  6315.3  300.03
#Mann= 5 ,-1 , 0
  3054.5     .16       0  4563.2     .12       0  4725.1     .07       0
  4731.1     .12       0    5137     .16       0
Bank Sta=4440.8,5178.2
XS Rating Curve= 0 ,0
Exp/Cntr=0.3,0.1

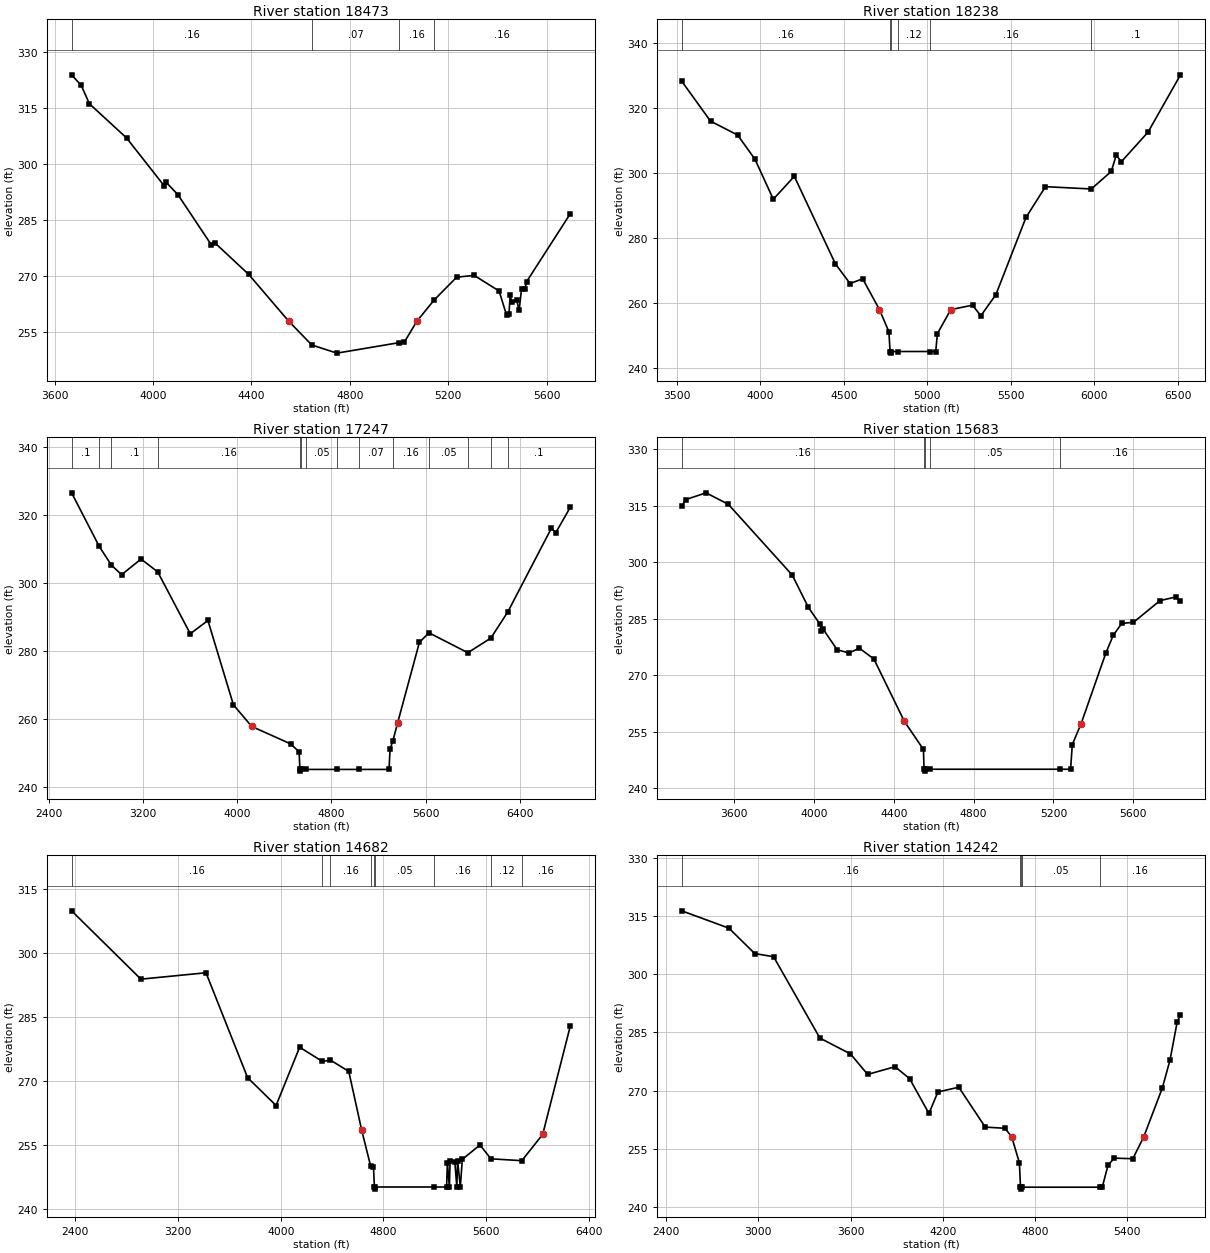
Type RM Length L Ch R = 1 ,18473   ,235,235,235
BEGIN DESCRIPTION:
Mapping XS a6d9589e
END DESCRIPTION:
XS GIS Cut Line= 4
        3704473.     10534426.57      3703439.12     10534108.85
      3703137.03      10534077.6      3702504.41     10534186.94
#Sta/Elev= 30
  3668.8  323.95  3708.2  321.09    3741   316.2    3892  307.03  4045.8  294.12
  4051.1  295.25  4101.3  291.77  4237.3  278.29  4252.6  278.79  4388.7  270.41
  4551.1  257.87  4645.3  251.47  4747.3  249.29  5001.2  252.11  5021.3  252.22
  5071.8  257.81  5142.8  263.56  5234.1  269.66  5305.2  270.15  5406.7  265.95
  5437.1  259.43  5446.6  259.83  5451.6  264.79  5457.4  262.92  5477.7  263.65
  5487.9  260.75    5498   266.6  5511.4  266.41  5518.3  268.46  5696.1   286.7
#Mann= 4 ,-1 , 0
  3668.8     .16       0  4645.3     .07       0  5001.2     .16       0
  5142.8     .16       0
Bank Sta=4551.1,5071.8
XS Rating Curve= 0 ,0
Exp/Cntr=0.3,0.1

Type RM Length L Ch R = 1 ,18238   ,991,991,991
BEGIN DESCRIPTION:
Mapping XS 02548f63
END DESCRIPTION:
XS GIS Cut Line= 3
      3704531.47     10534342.35      3703576.62      10533830.2
      3701675.54     10533925.69
#Sta/Elev= 30
  3529.1  328.12  3701.4  315.86  3863.8  311.59  3967.7  304.14  4077.4  291.87
  4203.3  298.89  4449.3  272.01    4537  265.97  4612.6  267.41  4713.4  257.94
  4769.8  251.14  4776.8  245.08  4779.6  244.58  4782.8  245.08  4825.1  245.08
    5015  245.08  5050.2  245.08  5060.2  250.56  5140.3  257.95  5270.5  259.31
  5320.5  256.06  5410.6  262.56  5590.9  286.28  5707.4  295.72  5982.2  295.02
  6101.5  300.41  6131.5  305.43  6161.6  303.37  6321.8  312.48  6516.1  330.09
#Mann= 6 ,-1 , 0
  3529.1     .16       0  4776.8     .07       0  4782.8     .16       0
  4825.1     .12       0    5015     .16       0  5982.2      .1       0
Bank Sta=4713.4,5140.3
XS Rating Curve= 0 ,0
Exp/Cntr=0.3,0.1

Type RM Length L Ch R = 1 ,17247   ,1564,1564,1564
BEGIN DESCRIPTION:
Mapping XS c920f065
END DESCRIPTION:
XS GIS Cut Line= 3
      3705521.01     10532250.35      3702560.99     10533022.91
      3701659.19     10533785.98
#Sta/Elev= 30
  2590.5  326.55  2825.7  310.75    2929  305.25  3015.7  302.43    3181  307.05
  3322.7  303.26  3599.6  285.03  3749.5  288.95  3966.5   264.1  4121.5  257.75
  4452.3  252.61  4524.6   250.3  4531.9  245.08  4534.7  244.58  4537.9  245.08
  4580.7  245.08  4849.3  245.08  5033.9  245.08  5289.4  245.08  5298.4  251.14
  5320.9  253.31  5361.7  258.69  5547.8  282.51    5629  285.32  5959.6  279.46
  6154.9  283.75  6300.1  291.52  6670.8  316.18    6706  314.73    6831  322.32
#Mann= 14 ,-1 , 0
  2590.5      .1       0  2825.7     .16       0    2929      .1       0
  3322.7     .16       0  4531.9     .07       0  4537.9     .16       0
  4580.7     .05       0  4849.3     .16       0  5033.9     .07       0
  5320.9     .16       0    5629     .05       0  5959.6     .16       0
  6154.9     .05       0  6300.1      .1       0
Bank Sta=4121.5,5361.7
XS Rating Curve= 0 ,0
Exp/Cntr=0.3,0.1

Type RM Length L Ch R = 1 ,15683   ,1001,1001,1001
BEGIN DESCRIPTION:
Mapping XS 45cbd682
END DESCRIPTION:
XS GIS Cut Line= 2
      3704132.18      10530705.2      3701970.75     10531963.86
#Sta/Elev= 30
  3336.2  314.86  3356.3  316.62    3458  318.41  3569.7  315.37  3890.7  296.57
    3971  288.03  4029.7  283.55  4035.5  281.87  4045.1  282.24  4115.7  276.77
  4174.5  275.94  4227.4  277.17  4299.6  274.34  4452.4  257.81  4548.4  250.32
  4551.2  245.08    4554  244.58  4557.2  245.08  4580.3  245.08  5232.2  245.08
  5286.3  245.08  5294.8  251.62  5339.3  257.21  5462.6  275.83  5499.8  280.57
  5542.8  283.78  5601.5  284.05  5734.6  289.81    5815   290.8  5837.4  289.76
#Mann= 5 ,-1 , 0
  3336.2     .16       0  4551.2    .033       0  4557.2     .16       0
  4580.3     .05       0  5232.2     .16       0
Bank Sta=4452.4,5339.3
XS Rating Curve= 0 ,0
Exp/Cntr=0.3,0.1

Type RM Length L Ch R = 1 ,14682   ,440,440,440
BEGIN DESCRIPTION:
Mapping XS ae6543d6
END DESCRIPTION:
XS GIS Cut Line= 3
      3704548.88     10530271.17      3701745.02      10530930.9
      3700885.65     10531451.72
#Sta/Elev= 30
  2370.2  309.95  2910.2   293.9  3417.3   295.4  3741.1  270.77  3963.2  264.22
  4146.7  277.91    4324  274.58  4386.8  274.88  4529.5  272.23  4629.5   258.5
  4698.9   250.1    4722  249.76  4729.3  245.08    4732  244.58  4735.3  245.08
  5197.1  245.08  5291.8  245.08  5297.7  250.82  5313.2  245.08    5319  251.23
  5355.9  250.84  5371.4  245.08  5377.2   251.3  5398.5  245.08    5414  251.58
  5551.7  254.95    5637   251.7  5877.6  251.26  6040.4  257.45  6255.5  282.93
#Mann= 9 ,-1 , 0
  2370.2     .16       0    4324     .12       0  4386.8     .16       0
  4698.9     .05       0  4729.3    .033       0  4735.3     .05       0
  5197.1     .16       0    5637     .12       0  5877.6     .16       0
Bank Sta=4629.5,6040.4
XS Rating Curve= 0 ,0
Exp/Cntr=0.3,0.1

Type RM Length L Ch R = 1 ,14242   ,782,782,782
BEGIN DESCRIPTION:
Mapping XS 81fefc94
END DESCRIPTION:
XS GIS Cut Line= 3
      3704462.06     10530054.15      3702873.49     10530557.63
      3701312.83     10530332.21
#Sta/Elev= 30
  2502.2  316.32    2809  311.85  2976.8  305.31  3099.4  304.49  3400.5  283.52
  3599.4  279.43  3711.1  274.15  3889.5  276.14  3983.9  273.05  4109.8  264.09
  4168.1  269.63  4303.9  270.85  4475.7  260.57  4603.7  260.26  4647.4  258.13
    4698  251.35  4705.1  245.08  4707.8  244.58  4711.1  245.08    4714  245.08
  5219.3  245.08  5236.8  245.08  5273.9  250.69  5314.3  252.57  5435.5  252.42
  5506.3  258.03  5627.5  270.65    5678  277.94  5724.1  287.71  5745.5  289.48
#Mann= 5 ,-1 , 0
  2502.2     .16       0  4705.1    .033       0  4711.1     .16       0
    4714     .05       0  5219.3     .16       0
Bank Sta=4647.4,5506.3
XS Rating Curve= 0 ,0
Exp/Cntr=0.3,0.1

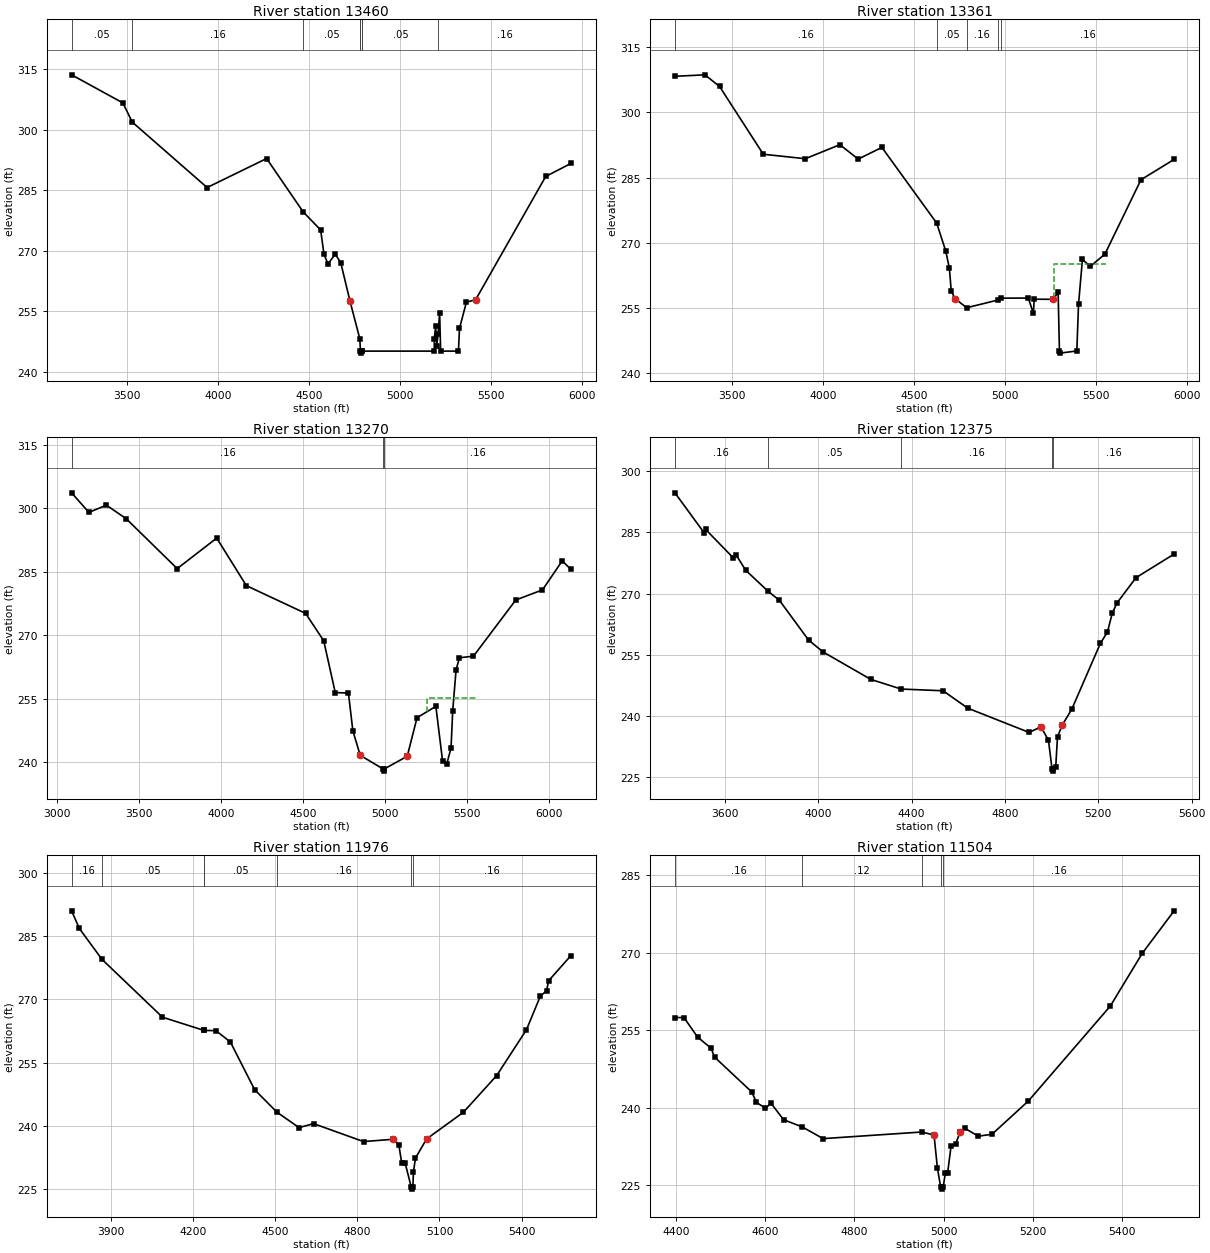
Type RM Length L Ch R = 1 ,13460   ,99,99,99
BEGIN DESCRIPTION:
Mapping XS 2aafa7c1
END DESCRIPTION:
XS GIS Cut Line= 4
      3704019.28     10529819.78      3702508.91     10529628.81
       3702109.6     10529698.26      3701389.09      10530088.9
#Sta/Elev= 30
  3193.1  313.57    3475  306.61  3526.9  301.85  3938.7  285.63  4266.2  292.82
  4467.5  279.58  4563.6  275.11  4581.8  269.14  4603.9  266.69  4644.2  269.12
  4674.5  266.96  4724.9   257.5  4778.9  248.17  4782.8  245.08  4785.6  244.58
  4788.8  245.08  4793.9  245.08    5189  245.08 5189.07   248.2  5196.5   251.2
  5202.2  246.33  5210.2  249.41  5218.4  254.55  5224.1  245.08    5322  245.08
  5327.7  250.71  5365.7  257.21  5416.5  257.81  5802.2  288.37  5940.4  291.59
#Mann= 8 ,-1 , 0
  3193.1     .05       0  3526.9     .16       0  4467.5     .05       0
  4778.9     .16       0  4782.8    .033       0  4788.8     .16       0
  4793.9     .05       0  5210.2     .16       0
Bank Sta=4724.9,5416.5
XS Rating Curve= 0 ,0
Exp/Cntr=0.3,0.1

Type RM Length L Ch R = 1 ,13361   ,91,91,91
BEGIN DESCRIPTION:
Mapping XS 5a52e1d4
END DESCRIPTION:
XS GIS Cut Line= 4
      3704054.06      10529680.9      3702448.14     10529550.69
      3702048.84     10529611.45      3701415.91     10529975.61
#Sta/Elev= 30
  3185.8   308.3  3350.8  308.64  3431.1  305.97  3671.8  290.36  3902.6  289.33
  4093.2  292.56  4193.5  289.24    4324  291.93  4625.4  274.51  4675.1  268.09
  4695.2  264.12  4705.2  258.97  4725.3  257.15  4790.4  255.03  4961.1  256.79
  4977.6  257.23  5129.3  257.26  5156.9  253.77    5162     257    5266  256.96
  5293.3  258.55  5300.4  245.08  5303.1  244.58  5396.1  245.08  5405.4  255.83
    5427  266.16  5470.1  264.53  5550.6  267.38  5748.9  284.49  5931.1  289.17
#Mann= 5 ,-1 , 0
  3185.8     .16       0  4625.4     .05       0  4790.4     .16       0
  4961.1     .07       0  4977.6     .16       0
#XS Ineff= 1 ,-1
 5272.16 5555.11  265.06
Permanent Ineff=
       F
Bank Sta=4725.3,5266
XS Rating Curve= 0 ,0
Exp/Cntr=0.3,0.1

Type RM Length L Ch R = 1 ,13270   ,895,895,895
BEGIN DESCRIPTION:
Mapping XS e42c379c
END DESCRIPTION:
XS GIS Cut Line= 4
      3704140.85     10529594.09      3702430.78     10529446.52
      3701718.98     10529611.45      3701276.24     10530010.78
#Sta/Elev= 30
  3089.7  303.67  3194.8  299.05  3301.7  300.75  3421.5  297.59  3733.3  285.77
  3974.2  292.98  4154.9  281.75  4516.2   275.2  4626.6  268.73  4696.9   256.5
  4777.2  256.39  4804.2  247.48    4849  241.69  4989.1  238.45  4991.8  237.95
  4995.1  238.45  5135.8  241.47  5195.6  250.58  5310.3  253.24  5351.4  240.26
  5376.6  239.63  5402.7  243.39    5413  252.21  5433.5  261.88    5454  264.72
  5539.6   265.1  5797.4  278.36  5960.3  280.75  6080.6  287.61    6133  285.61
#Mann= 3 ,-1 , 0
  3089.7     .16       0  4989.1     .07       0  4995.1     .16       0
#XS Ineff= 1 ,-1
  5257.1 5561.36  255.23
Permanent Ineff=
       F
Bank Sta=4849,5135.8
XS Rating Curve= 0 ,0
Exp/Cntr=0.3,0.1

Type RM Length L Ch R = 1 ,12375   ,399,399,399
BEGIN DESCRIPTION:
UNT 176 IN UKCR 19.0
END DESCRIPTION:
XS GIS Cut Line= 3
       3703758.9     10528864.92      3702149.61     10528610.19
      3701649.64     10528510.19
#Sta/Elev= 30
  3385.7   294.7  3511.7  284.84  3516.8  285.76  3636.4  278.72  3648.2  279.46
  3688.7  275.74  3783.6  270.64  3833.6  268.34  3958.3  258.62  4020.7  255.69
  4225.3  248.96  4355.3   246.6  4534.7  246.18  4640.4  241.92  4903.7  235.96
  4954.3  237.35  4986.4  234.04  5001.9  226.98  5004.7  226.48  5007.9  226.98
  5017.6  227.52  5025.2   234.9  5045.6  237.77  5086.4  241.66  5208.8  257.78
  5239.4  260.61  5259.8  265.18  5280.2  267.71  5361.8  273.91  5524.9  279.69
#Mann= 5 ,-1 , 0
  3385.7     .16       0  3783.6     .05       0  4355.3     .16       0
  5001.9     .07       0  5007.9     .16       0
Bank Sta=4954.3,5045.6
XS Rating Curve= 0 ,0
Exp/Cntr=0.3,0.1

Type RM Length L Ch R = 1 ,11976   ,472,472,472
BEGIN DESCRIPTION:
UNT 176 IN UKCR 18.0
END DESCRIPTION:
XS GIS Cut Line= 3
      3703549.65     10528460.19      3702349.61     10528260.19
      3701749.58     10528160.18
#Sta/Elev= 30
  3755.3  291.07  3783.2   286.9  3866.4  279.53  4087.4  265.79  4239.2  262.65
  4239.3  262.64  4282.5   262.6  4335.7   259.9  4424.4  248.55  4506.3   243.2
  4586.6  239.55  4639.9  240.49  4822.4  236.23  4931.3  236.78  4951.6  235.41
  4961.8  231.19  4974.4  231.16  4996.8  225.43  4999.5  224.93  5002.8  225.43
  5004.8     229  5012.4  232.32    5053  236.86  5187.3  243.18    5309  251.91
    5418   262.8  5468.7  270.78  5491.5  272.09  5499.1  274.45  5580.2  280.41
#Mann= 7 ,-1 , 0
  3755.3     .16       0  3866.4     .05       0  4239.2     .08       0
  4239.3     .05       0  4506.3     .16       0  4996.8     .07       0
  5002.8     .16       0
Bank Sta=4931.3,5053
XS Rating Curve= 0 ,0
Exp/Cntr=0.3,0.1

Type RM Length L Ch R = 1 ,11504   ,648,648,648
BEGIN DESCRIPTION:
UNT 176 IN UKCR 17.0
END DESCRIPTION:
XS GIS Cut Line= 3
      3702849.61     10527910.19      3702249.61     10527810.19
      3701749.59     10527910.19
#Sta/Elev= 30
  4398.2  257.46  4418.5  257.46  4448.9  253.68  4479.3  251.51  4486.9   249.8
  4570.5  243.02  4580.7  241.01    4601   239.9  4613.6  240.84  4641.5  237.66
  4683.6  236.25  4730.2  233.99  4950.7  235.27  4978.6  234.69  4986.2  228.27
  4993.3   224.7  4996.1   224.2  4999.3   224.7  5003.9   227.3    5009   227.3
  5016.7  232.51  5026.9  232.94  5037.1  235.26  5047.3  236.01  5077.9  234.46
  5108.5  234.84    5190  241.29  5373.6   259.7    5445  269.91  5516.4  278.15
#Mann= 5 ,-1 , 0
  4398.2     .16       0  4683.6     .12       0  4950.7     .16       0
  4993.3     .07       0  4999.3     .16       0
Bank Sta=4978.6,5037.1
XS Rating Curve= 0 ,0
Exp/Cntr=0.3,0.1

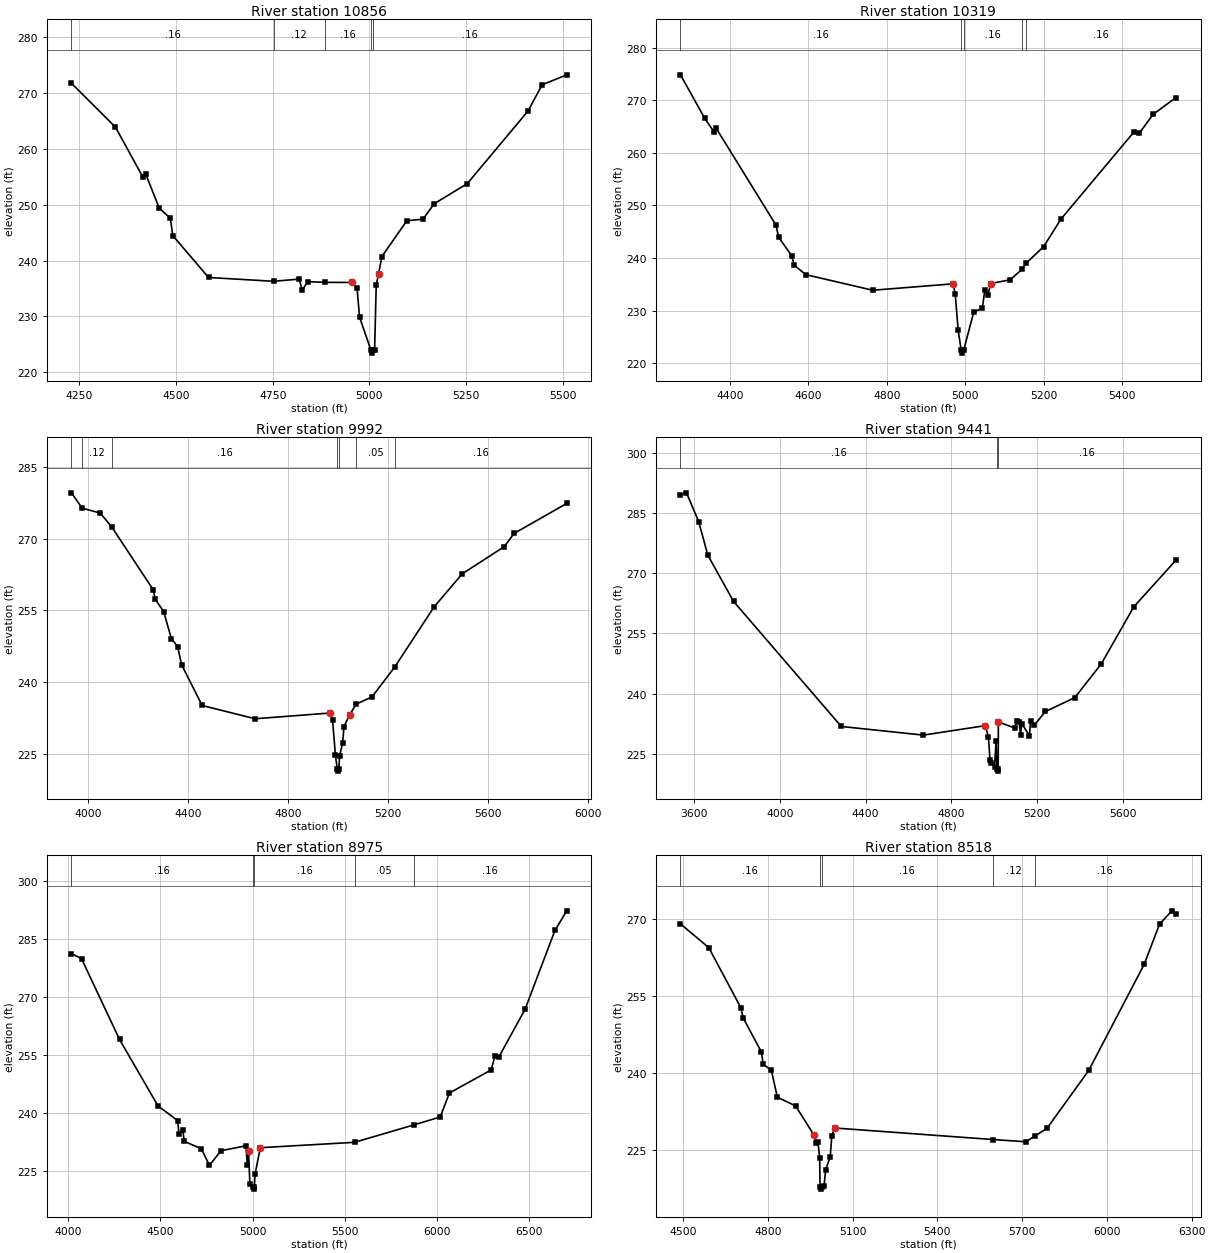
Type RM Length L Ch R = 1 ,10856   ,537,537,537
BEGIN DESCRIPTION:
UNT 176 IN UKCR 16.0
END DESCRIPTION:
XS GIS Cut Line= 3
      3702599.58     10526860.22      3702099.61     10527460.19
       3701699.6      10527760.2
#Sta/Elev= 30
  4229.3  271.72  4343.2  263.87  4413.5  255.01  4421.3   255.5  4456.4  249.37
    4485  247.57  4491.6  244.44    4584  236.96  4752.2  236.28  4818.3  236.67
  4826.1  234.69  4840.4  236.22  4884.9  236.09  4953.7  236.07    4968  235.04
  4974.5  229.86    5004  223.92  5006.8  223.42    5010  223.92  5013.4  223.92
  5017.6  235.64  5023.8  237.67  5032.2  240.71  5096.7  247.12  5138.4   247.4
  5167.6  250.17    5253  253.76  5410.3  266.77  5446.7  271.46  5510.3  273.24
#Mann= 5 ,-1 , 0
  4229.3     .16       0  4752.2     .12       0  4884.9     .16       0
    5004     .07       0    5010     .16       0
Bank Sta=4953.7,5023.8
XS Rating Curve= 0 ,0
Exp/Cntr=0.3,0.1

Type RM Length L Ch R = 1 ,10319   ,327,327,327
BEGIN DESCRIPTION:
UNT 176 IN UKCR 15.0
END DESCRIPTION:
XS GIS Cut Line= 3
      3702599.61     10526760.19      3701899.61     10527060.19
       3701599.6     10527460.21
#Sta/Elev= 30
  4274.4  274.83  4336.1  266.55  4359.6     264  4365.1  264.69  4517.4  246.27
  4524.6  243.92  4557.3  240.46  4564.5  238.59  4593.5  236.83    4764  233.86
  4968.9  235.08  4974.3  233.06  4981.6   226.3  4989.5   222.4  4992.2   221.9
  4995.5   222.4  5021.5  229.75  5043.3  230.43  5049.5  233.84  5057.9  233.03
  5064.1  235.13  5114.1  235.85  5144.1  237.82  5154.7     239  5199.5  242.16
  5243.3  247.37  5428.7   263.9  5443.3  263.76  5478.7  267.34    5536  270.48
#Mann= 5 ,-1 , 0
  4274.4     .16       0  4989.5     .07       0  4995.5     .16       0
  5144.1     .05       0  5154.7     .16       0
Bank Sta=4968.9,5064.1
XS Rating Curve= 0 ,0
Exp/Cntr=0.3,0.1

Type RM Length L Ch R = 1 ,9992    ,551,551,551
BEGIN DESCRIPTION:
UNT 176 IN UKCR 14.0
END DESCRIPTION:
XS GIS Cut Line= 3
      3702749.57      10526610.2      3701701.62     10526851.04
      3701302.75      10527666.1
#Sta/Elev= 30
    3933  279.57  3976.2  276.36  4047.8  275.35  4093.6   272.5  4261.3  259.24
  4267.1  257.43  4302.3  254.72  4333.1   249.1  4357.9  247.44  4374.2   243.6
  4456.3  235.11  4668.1  232.34  4969.3  233.54  4978.3  232.12  4989.8  224.66
  4997.1  221.89  4999.8  221.39  5003.1  221.89  5006.7  224.61  5018.5  227.26
  5024.1   230.7  5046.6  233.16  5072.8  235.39  5136.7  236.93    5228  243.21
  5384.3  255.69  5496.8  262.61  5665.5  268.32  5704.9  271.08  5915.7  277.35
#Mann= 7 ,-1 , 0
    3933     .16       0  3976.2     .12       0  4093.6     .16       0
  4997.1     .07       0  5003.1     .16       0  5072.8     .05       0
    5228     .16       0
Bank Sta=4969.3,5046.6
XS Rating Curve= 0 ,0
Exp/Cntr=0.3,0.1

Type RM Length L Ch R = 1 ,9441    ,466,466,466
BEGIN DESCRIPTION:
UNT 176 IN UKCR 13.0
END DESCRIPTION:
XS GIS Cut Line= 3
      3702399.61     10525610.19      3701299.61     10526610.19
      3701099.61     10527410.17
#Sta/Elev= 30
  3536.3  289.53  3564.3  289.97  3621.1  282.83  3663.7  274.45  3783.9  262.93
  4286.7  231.79  4669.2  229.64    4959     232  4973.2  229.14  4980.7  223.36
  4987.4  222.78  5001.6  221.79    5009  228.14  5012.8  221.17  5015.6  220.67
  5018.8  221.17  5019.5  232.93  5095.1  231.42  5105.4  233.14  5115.7  232.84
  5123.4  229.78  5128.6  232.51  5164.6  229.49  5169.8  233.23  5187.8  232.16
  5239.4  235.52  5375.9  238.96  5499.6  247.36  5651.7   261.6  5847.5  273.15
#Mann= 3 ,-1 , 0
  3536.3     .16       0  5012.8     .07       0  5018.8     .16       0
Bank Sta=4959,5019.5
XS Rating Curve= 0 ,0
Exp/Cntr=0.3,0.1

Type RM Length L Ch R = 1 ,8975    ,457,457,457
BEGIN DESCRIPTION:
UNT 176 IN UKCR 12.0
END DESCRIPTION:
XS GIS Cut Line= 3
      3701927.33     10525401.36      3701432.52     10526061.11
      3700099.63     10527360.16
#Sta/Elev= 30
  4017.2  281.19  4071.9  279.86  4278.2  258.97  4486.4  241.82  4592.7  238.03
    4601  234.45  4621.9   235.6  4628.2  232.66  4721.9  230.71  4765.6  226.43
  4828.2  230.22  4963.5  231.49  4970.7  226.61  4977.6  230.02  4984.8  221.74
  5002.9  220.79  5005.7  220.29  5008.9  220.79  5013.1  224.17  5041.4     231
  5552.4  232.39  5873.4  236.88  6017.3  238.94  6066.7  245.13    6293   251.1
  6314.1  254.72  6335.4  254.47  6476.9  266.75  6639.5   287.2  6703.1  292.23
#Mann= 5 ,-1 , 0
  4017.2     .16       0  5002.9     .07       0  5008.9     .16       0
  5552.4     .05       0  5873.4     .16       0
Bank Sta=4977.6,5041.4
XS Rating Curve= 0 ,0
Exp/Cntr=0.3,0.1

Type RM Length L Ch R = 1 ,8518    ,814,814,814
BEGIN DESCRIPTION:
UNT 176 IN UKCR 11.0
END DESCRIPTION:
XS GIS Cut Line= 3
      3701449.58     10525560.21      3701049.61     10525860.19
      3699949.57     10526460.21
#Sta/Elev= 30
  4490.9  269.01  4590.9  264.39  4704.4  252.68  4712.7  250.68  4777.3  244.03
  4783.6  241.67  4812.7  240.45  4833.6  235.22  4898.2  233.53  4962.7  227.89
    4969  226.39  4977.3   226.5  4983.6  223.41  4984.7   217.8  4987.5   217.3
  4990.7   217.8  4998.9  217.88  5004.6  221.08  5020.8  223.59  5026.5  227.73
  5036.4  229.22  5596.4  226.97  5712.8  226.54  5745.2  227.63  5788.2  229.17
  5935.8  240.44  6132.3  261.15  6186.4  268.97  6230.1  271.56  6243.9  270.87
#Mann= 5 ,-1 , 0
  4490.9     .16       0  4984.7     .07       0  4990.7     .16       0
  5596.4     .12       0  5745.2     .16       0
Bank Sta=4962.7,5036.4
XS Rating Curve= 0 ,0
Exp/Cntr=0.3,0.1

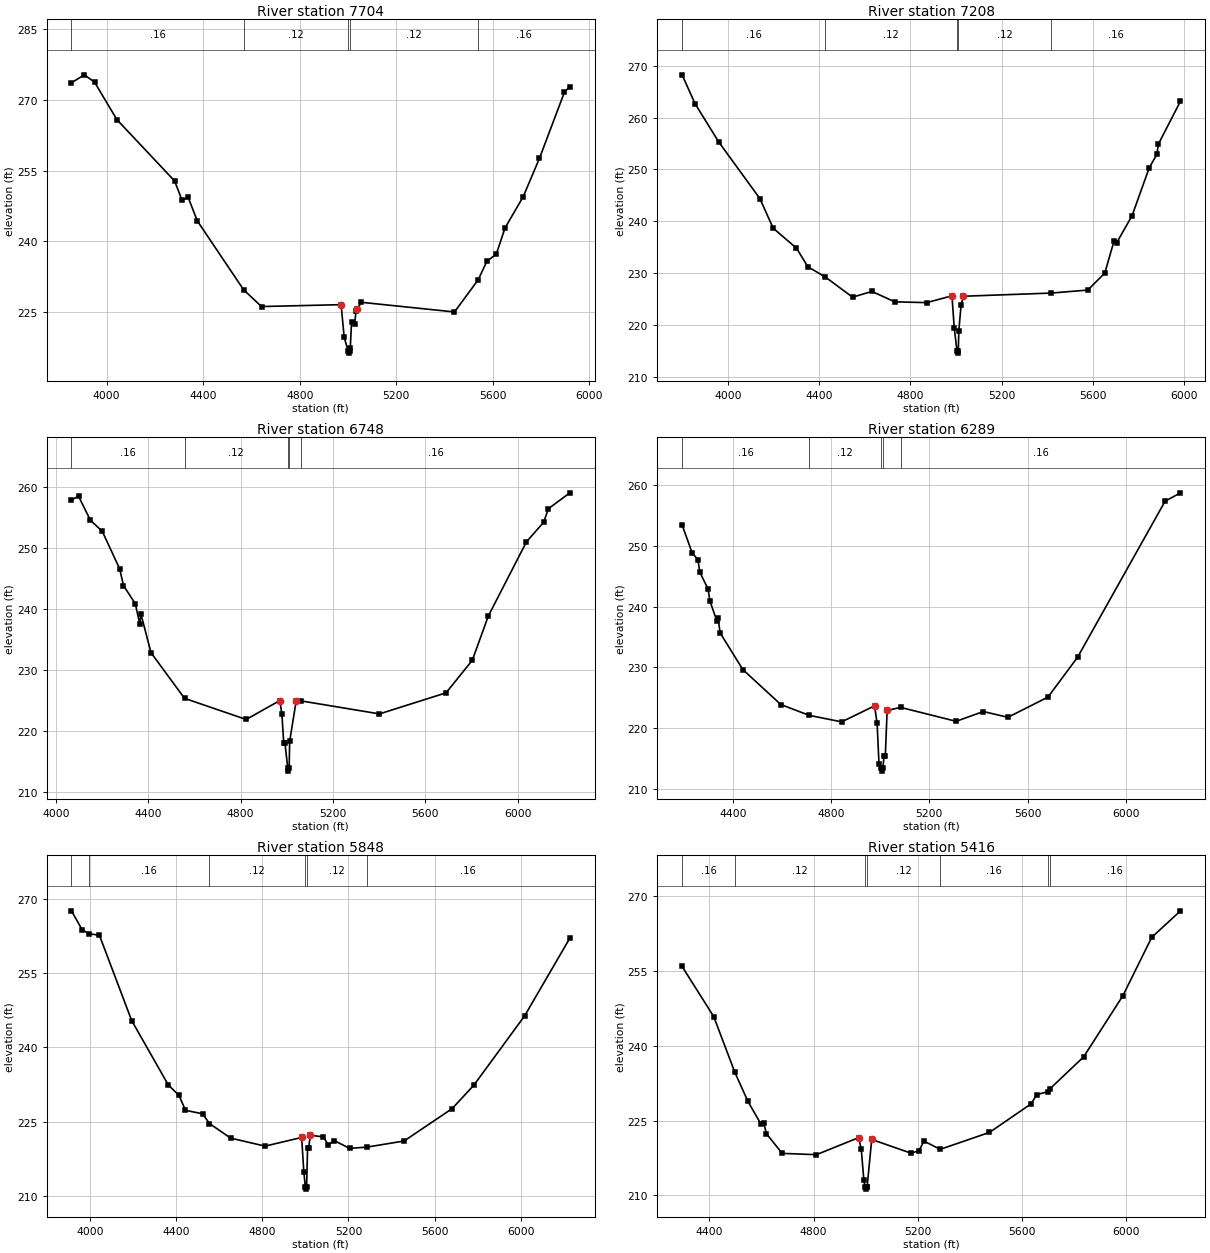
Type RM Length L Ch R = 1 ,7704    ,496,496,496
BEGIN DESCRIPTION:
UNT 176 IN UKCR 10.0
END DESCRIPTION:
XS GIS Cut Line= 3
      3701449.59      10525160.2      3700349.61     10525560.19
       3699949.6     10526360.21
#Sta/Elev= 30
  3854.2  273.66  3907.4  275.35  3949.9   273.8  4042.4  265.85  4281.8  252.82
  4312.4  248.73  4337.7  249.36  4375.6  244.37  4567.6  229.75  4641.6   226.2
  4971.4   226.6  4984.1  219.67  5000.4  216.82  5003.1  216.32  5006.4  216.82
  5009.4  217.44  5014.7  222.98  5027.4  222.45    5033  225.21  5038.6  225.71
  5055.4   227.1  5441.1  225.05  5539.1  231.86  5575.3  235.79  5614.4  237.33
  5650.7  242.89  5726.2  249.54  5793.3  257.66  5896.7  271.67  5919.1  272.86
#Mann= 5 ,-1 , 0
  3854.2     .16       0  4567.6     .12       0  5000.4     .07       0
  5006.4     .12       0  5539.1     .16       0
Bank Sta=4971.4,5038.6
XS Rating Curve= 0 ,0
Exp/Cntr=0.3,0.1

Type RM Length L Ch R = 1 ,7208    ,460,460,460
BEGIN DESCRIPTION:
UNT 176 IN UKCR 9.0
END DESCRIPTION:
XS GIS Cut Line= 3
       3701299.6     10525160.19      3700038.25     10525270.13
      3699799.61     10526160.17
#Sta/Elev= 30
  3797.7  268.23  3854.1   262.7  3958.3  255.29    4139  244.37  4197.5  238.65
  4299.6  234.81  4349.8  231.21  4425.7  229.26  4545.9  225.35  4630.8  226.46
  4731.2  224.45  4871.7   224.3  4982.2  225.61  4992.2   219.4  5004.1  215.06
  5006.8  214.56  5010.1  215.06  5012.3  218.92  5022.3  223.85  5032.4  225.53
  5416.4  226.14  5578.1  226.72    5653  229.99    5693  236.11  5705.8  235.89
    5773  241.09  5847.9  250.29  5881.8   252.9  5887.9  254.84  5985.3  263.15
#Mann= 5 ,-1 , 0
  3797.7     .16       0  4425.7     .12       0  5004.1     .07       0
  5010.1     .12       0  5416.4     .16       0
Bank Sta=4982.2,5032.4
XS Rating Curve= 0 ,0
Exp/Cntr=0.3,0.1

Type RM Length L Ch R = 1 ,6748    ,459,459,459
BEGIN DESCRIPTION:
UNT 176 IN UKCR 8.0
END DESCRIPTION:
XS GIS Cut Line= 3
      3700949.63     10524660.18      3700049.61     10524860.19
      3698849.62     10524560.19
#Sta/Elev= 30
  4067.7  257.96  4098.5  258.56  4149.7  254.62  4200.9  252.83  4276.4  246.68
  4293.1  243.92  4344.3  240.93  4363.5  237.63  4368.6  239.26  4412.2  232.92
  4557.4  225.43  4824.5  221.97  4970.5  225.07  4979.4  222.79  4987.1  218.16
  4992.3  218.16  5004.7     214  5007.5   213.5  5010.7     214  5012.9  218.38
  5041.2  225.01  5062.5  225.01    5402  222.88  5690.6  226.34    5804  231.67
  5873.6  238.94  6038.5  251.08  6113.2   254.3  6133.8  256.52  6226.6  259.12
#Mann= 5 ,-1 , 0
  4067.7     .16       0  4557.4     .12       0  5004.7     .07       0
  5010.7     .12       0  5062.5     .16       0
Bank Sta=4970.5,5041.2
XS Rating Curve= 0 ,0
Exp/Cntr=0.3,0.1

Type RM Length L Ch R = 1 ,6289    ,441,441,441
BEGIN DESCRIPTION:
UNT 176 IN UKCR 7.0
END DESCRIPTION:
XS GIS Cut Line= 3
      3700849.57     10524610.18      3700049.61     10524410.19
      3698849.65     10524510.18
#Sta/Elev= 30
  4193.8  253.45    4235  248.81  4258.2  247.76  4265.9  245.67  4299.4  242.91
  4307.1  240.91  4335.5  237.63  4340.6  238.08  4348.4  235.69  4441.1  229.64
  4595.8  223.89  4711.1  222.11  4843.2  221.04  4977.2  223.67  4987.5  220.81
  4995.2  214.18  5005.1  213.43  5007.8  212.93  5011.1  213.43  5015.8  215.41
  5020.9  215.41  5028.4  222.92  5083.2  223.42  5309.4  221.13  5419.8  222.74
  5520.1  221.79  5683.2  225.12  5803.6  231.68  6159.8  257.36  6222.5  258.74
#Mann= 5 ,-1 , 0
  4193.8     .16       0  4711.1     .12       0  5005.1     .07       0
  5011.1     .12       0  5083.2     .16       0
Bank Sta=4977.2,5028.4
XS Rating Curve= 0 ,0
Exp/Cntr=0.3,0.1

Type RM Length L Ch R = 1 ,5848    ,432,432,432
BEGIN DESCRIPTION:
UNT 176 IN UKCR 6.0
END DESCRIPTION:
XS GIS Cut Line= 3
      3701049.63     10524010.19      3699949.61     10524010.19
      3698749.58     10523810.18
#Sta/Elev= 30
  3912.3  267.65  3962.3  263.79  3994.6  263.02  4042.3   262.7  4192.3  245.43
  4362.3  232.43  4412.3  230.28  4442.3  227.28  4522.3  226.57  4553.6  224.61
  4652.3  221.65  4812.3  220.03  4982.3  221.79  4992.3  214.81  4999.3  211.83
  5002.1  211.33  5005.3  211.83  5009.8  219.65  5014.9  219.65  5022.5  222.21
  5083.3  221.92  5106.1  220.25    5134  221.15  5204.9  219.58  5285.4  219.83
  5458.4  221.07  5681.4  227.61  5782.8  232.37  6018.5  246.38  6228.9  262.12
#Mann= 6 ,-1 , 0
  3912.3     .12       0  3994.6     .16       0  4553.6     .12       0
  4999.3     .07       0  5005.3     .12       0  5285.4     .16       0
Bank Sta=4982.3,5022.5
XS Rating Curve= 0 ,0
Exp/Cntr=0.3,0.1

Type RM Length L Ch R = 1 ,5416    ,476,476,476
BEGIN DESCRIPTION:
UNT 176 IN UKCR 5.0
END DESCRIPTION:
XS GIS Cut Line= 3
      3700599.57     10523560.19      3699899.61     10523660.19
      3698699.63     10523760.19
#Sta/Elev= 30
  4295.9  255.85  4417.1  245.82  4498.4  234.62  4548.4  228.82  4598.9  224.22
    4609  224.54  4619.1  222.37  4679.7  218.42    4811  218.16  4972.7  221.57
  4982.8   219.3  4992.9  213.05  4997.4  211.76  5000.2  211.26  5003.4  211.76
  5005.5  211.76    5023  221.21  5173.6  218.46  5203.7  218.94  5223.7  220.87
  5285.6  219.23  5474.6  222.62  5635.1  228.37  5655.2  230.17  5698.1  230.78
  5706.1  231.33  5835.8  237.76  5986.4  250.02  6096.7  261.68  6207.1     267
#Mann= 7 ,-1 , 0
  4295.9     .16       0  4498.4     .12       0  4997.4     .07       0
  5003.4     .12       0  5285.6     .16       0  5698.1     .12       0
  5706.1     .16       0
Bank Sta=4972.7,5023
XS Rating Curve= 0 ,0
Exp/Cntr=0.3,0.1