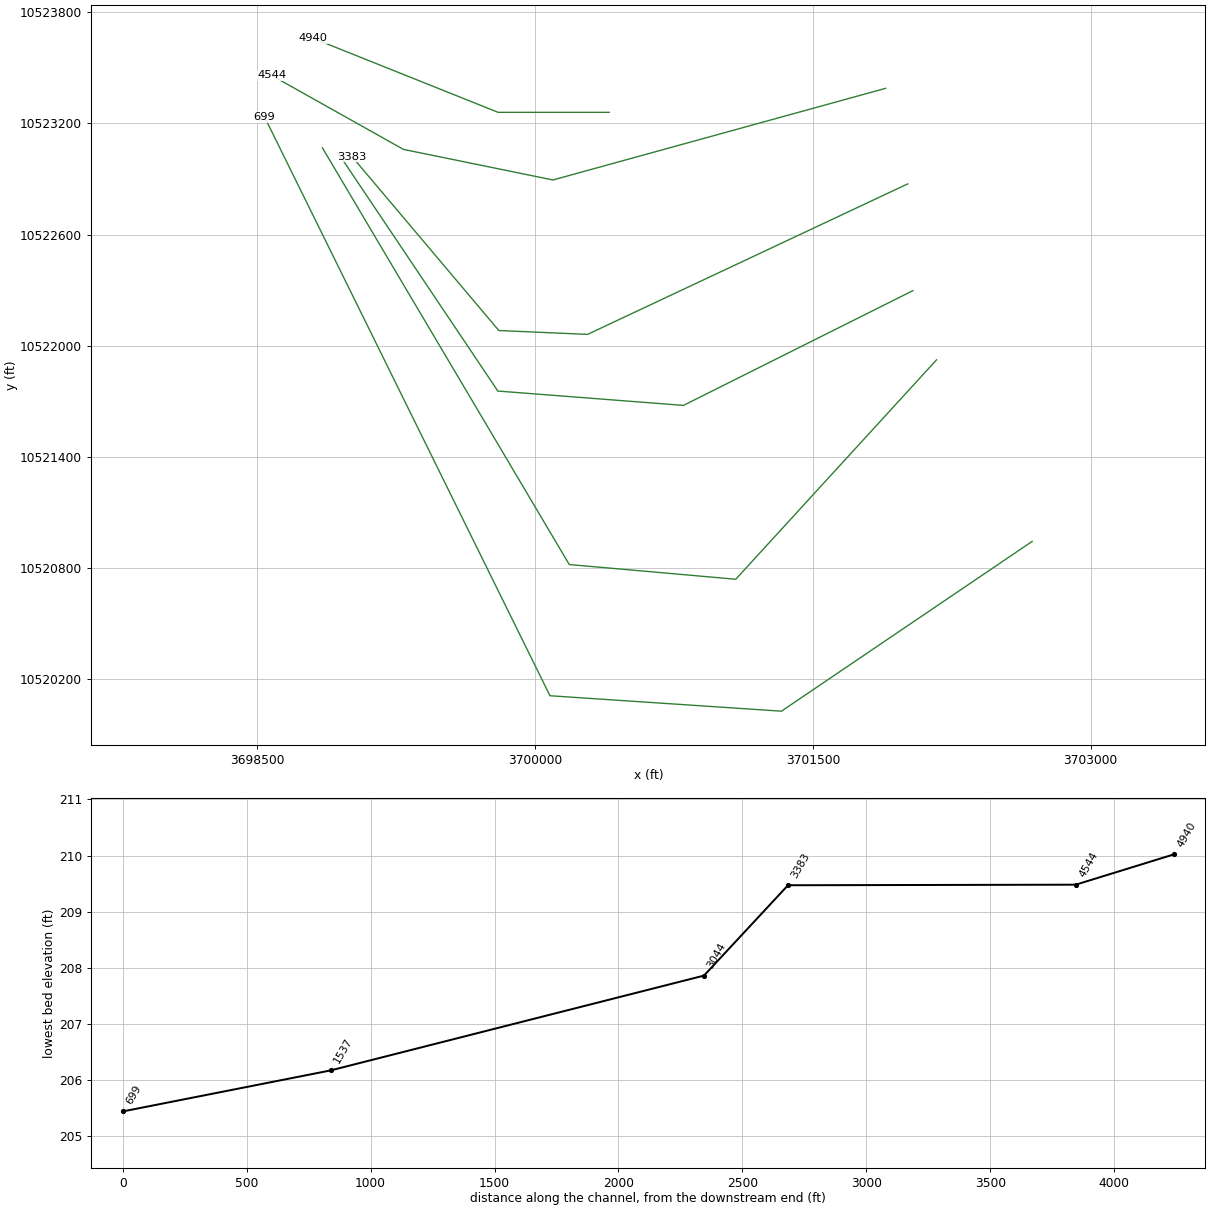
HEC-RAS study UNT 176 IN UKCR.prj: UNT 176 IN UKCR Base Level Engineering

--- UNT 176 IN UKCR.g01 (geometry) --- (continued)

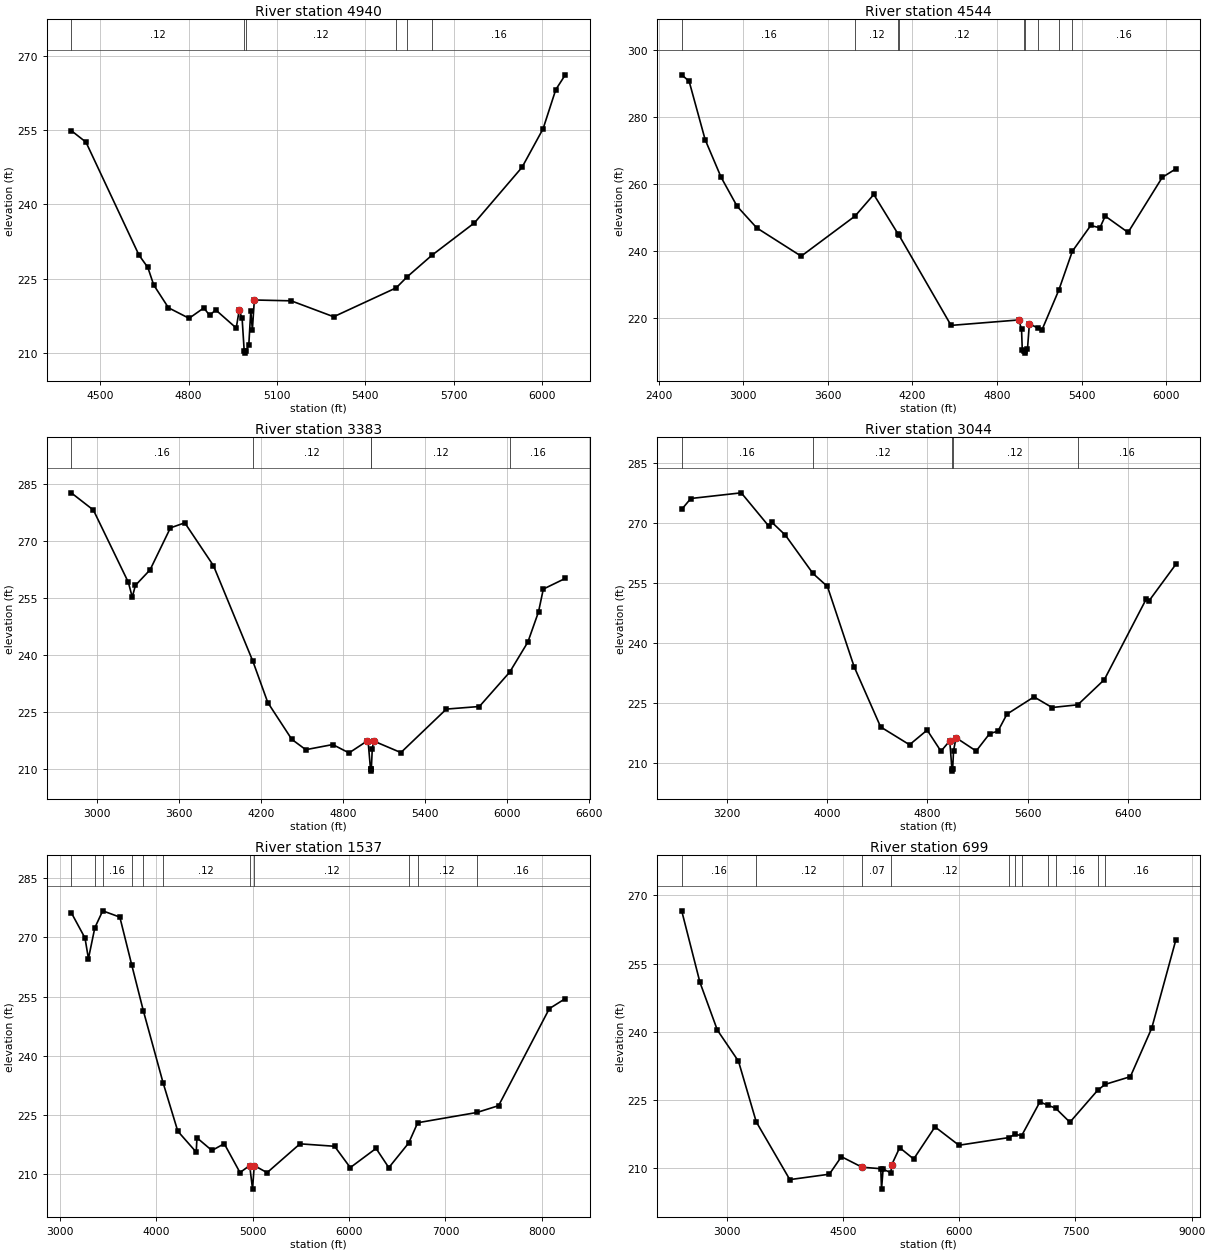
Type RM Length L Ch R = 1 ,4940    ,396,396,396
BEGIN DESCRIPTION:
UNT 176 IN UKCR 4.0
END DESCRIPTION:
XS GIS Cut Line= 3
      3700399.56     10523260.19      3699799.61     10523260.19
      3698799.59     10523660.19
#Sta/Elev= 30
  4401.7  254.87  4451.7  252.54  4631.7  229.77  4661.7  227.28  4681.7  223.75
  4731.7  219.16  4801.7  217.04  4851.7  219.13  4871.7  217.61  4891.7  218.75
  4961.7  215.08  4971.7  218.62  4981.7  217.02  4988.7  210.52  4991.4  210.02
  4994.7  210.52  5004.3  211.59  5011.1  218.53  5016.5   214.7  5023.2  220.73
  5148.4  220.56  5292.5  217.35  5504.7  223.18  5541.6  225.38  5625.4  229.72
  5770.4  236.28  5931.9  247.48  6003.3  255.24  6046.4  263.13  6078.7  266.11
#Mann= 6 ,-1 , 0
  4401.7     .12       0  4988.7     .07       0  4994.7     .12       0
  5504.7     .16       0  5541.6     .12       0  5625.4     .16       0
Bank Sta=4971.7,5023.2
XS Rating Curve= 0 ,0
Exp/Cntr=0.3,0.1

Type RM Length L Ch R = 1 ,4544    ,1161,1161,1161
BEGIN DESCRIPTION:
UNT 176 IN UKCR 3.0
END DESCRIPTION:
XS GIS Cut Line= 4
      3701892.91     10523389.81      3700096.03     10522895.02
      3699288.74     10523059.95      3698576.92     10523459.27
#Sta/Elev= 30
  2563.6  292.67  2616.2  290.75  2729.7  273.31  2843.3  262.02  2956.8  253.36
    3096  246.91    3411  238.46  3793.3  250.46  3925.8   256.9  4097.7  245.12
  4102.2   244.9  4473.9  217.77  4954.4   219.4  4973.7  216.62  4978.9  210.53
  4992.3  209.98    4995  209.48  4998.3  209.98  5015.7  210.61  5029.3  218.25
  5090.3  216.96  5117.8  216.34  5237.8  228.29    5334  239.93  5464.4  247.64
  5529.5  246.93  5567.1  250.45  5729.2  245.56  5972.2  262.04  6067.5  264.54
#Mann= 9 ,-1 , 0
  2563.6     .16       0  3793.3     .12       0  4097.7     .16       0
  4102.2     .12       0  4992.3     .07       0  4998.3     .12       0
  5090.3     .16       0  5237.8     .12       0    5334     .16       0
Bank Sta=4954.4,5029.3
XS Rating Curve= 0 ,0
Exp/Cntr=0.3,0.1

Type RM Length L Ch R = 1 ,3383    ,339,339,339
BEGIN DESCRIPTION:
Mapping XS bc830ac4
END DESCRIPTION:
XS GIS Cut Line= 4
      3702011.96     10522873.82      3700282.84     10522061.34
      3699803.67     10522082.17      3699011.98      10523019.7
#Sta/Elev= 30
  2808.8  282.68  2970.9  278.15  3227.3  259.11  3255.6  255.22  3278.4  258.33
  3385.9  262.42  3534.8  273.46  3640.1  274.79    3850  263.52  4138.6  238.37
  4247.8  227.51  4423.6  217.83  4525.8  215.11  4723.4  216.46  4842.6  214.26
  4972.8  217.34  4982.8  217.11  4999.8  209.97  5002.5  209.47  5005.8  209.97
  5012.8  215.38  5022.8  217.39  5222.2  214.35  5555.1  225.79  5796.9  226.47
  6018.5  235.49  6151.8  243.41  6229.8  251.36    6265  257.36    6426  260.17
#Mann= 5 ,-1 , 0
  2808.8     .16       0  4138.6     .12       0  4999.8     .07       0
  5005.8     .12       0  6018.5     .16       0
Bank Sta=4972.8,5022.8
XS Rating Curve= 0 ,0
Exp/Cntr=0.3,0.1

Type RM Length L Ch R = 1 ,3044    ,1507,1507,1507
BEGIN DESCRIPTION:
Mapping XS dc74181c
END DESCRIPTION:
XS GIS Cut Line= 4
      3702039.99     10522297.54      3700800.75     10521677.91
      3699798.42     10521755.37      3698933.68     10523043.38
#Sta/Elev= 30
  2840.8  273.38  2913.5  276.09    3316  277.51    3534  269.24    3562  270.09
  3668.2  266.91  3888.1  257.33  4003.6  254.07  4216.4  234.01  4428.1  218.92
  4658.7  214.46  4799.2  218.13  4909.5  212.84  4979.7  215.44  4996.8  208.36
  4999.5  207.86  5002.8  208.36  5009.8  212.95  5029.8  216.22  5190.3  212.89
    5298  217.25    5364  217.86    5436  222.12    5652  226.44  5796.1  223.78
  6001.3  224.46  6213.2  230.76  6546.2  250.86  6567.2  250.37    6783  259.59
#Mann= 5 ,-1 , 0
  2840.8     .16       0  3888.1     .12       0  4996.8     .07       0
  5002.8     .12       0  6001.3     .16       0
Bank Sta=4979.7,5029.8
XS Rating Curve= 0 ,0
Exp/Cntr=0.3,0.1

Type RM Length L Ch R = 1 ,1537    ,838,838,838
BEGIN DESCRIPTION:
UNT 176 IN UKCR 2.0
END DESCRIPTION:
XS GIS Cut Line= 5
      3702167.54     10521923.92      3701083.22     10520739.37
      3700184.08     10520818.74       3699694.6     10521644.74
      3698850.76     10523068.73
#Sta/Elev= 30
  3119.5  276.31    3262  269.87  3297.8  264.63    3364  272.46  3445.8  276.76
  3623.4  275.17  3746.3  263.09  3867.2  251.41  4071.2  233.21  4224.6  220.86
  4415.8  215.55  4423.2  219.19  4578.6  215.97  4706.2   217.7  4869.6  210.38
    4970  212.15  4999.8  206.17  5017.1  212.15  5150.7  210.35    5492  217.66
  5850.6  217.04  6013.3  211.63  6280.7   216.5    6413  211.62  6619.5  217.88
  6712.7  223.01  7326.2  225.61  7551.4  227.34  8077.7  251.95  8243.4  254.49
#Mann= 11 ,-1 , 0
  3119.5     .16       0    3364     .12       0  3445.8     .16       0
  3746.3     .12       0  3867.2     .16       0  4071.2     .12       0
    4970     .07       0  5017.1     .12       0  6619.5     .16       0
  6712.7     .12       0  7326.2     .16       0
Bank Sta=4970,5017.1
XS Rating Curve= 0 ,0
Exp/Cntr=0.3,0.1

Type RM Length L Ch R = 1 ,699     ,0,0,0
BEGIN DESCRIPTION:
UNT 176 IN UKCR 1.0
END DESCRIPTION:
XS GIS Cut Line= 4
      3702684.09     10520943.75      3701329.92     10520027.08
      3700079.92     10520110.41       3698538.3      10523235.3
#Sta/Elev= 30
  2421.8  266.59  2656.9  250.88  2881.6  240.38  3154.2  233.54  3383.1  220.23
  3816.3  207.53  4326.1  208.72  4481.5  212.57  4748.9  210.25  4989.4  209.93
  4999.2  205.44  5019.5  209.82  5119.7  209.04 5129.75  210.77  5233.1  214.55
  5413.9  212.06  5688.9  219.12  5997.6  215.08  6643.1  216.77  6717.7  217.48
  6806.9   217.2  7041.6   224.6  7150.7  223.83  7243.7  223.24  7428.8  220.14
  7786.3  227.15  7882.3  228.45  8208.8  230.15  8484.1   240.8  8794.3  260.13
#Mann= 11 ,-1 , 0
  2421.8     .16       0  3383.1     .12       0  4748.9     .07       0
  5119.7     .12       0  6643.1     .16       0  6717.7     .12       0
  6806.9     .16       0  7150.7     .12       0  7243.7     .16       0
  7786.3     .05       0  7882.3     .16       0
Bank Sta=4748.9,5129.75
XS Rating Curve= 0 ,0
Exp/Cntr=0.3,0.1

Chan Stop Cuts=-1
Use User Specified Reach Order=0
Composite Channel Slope=5