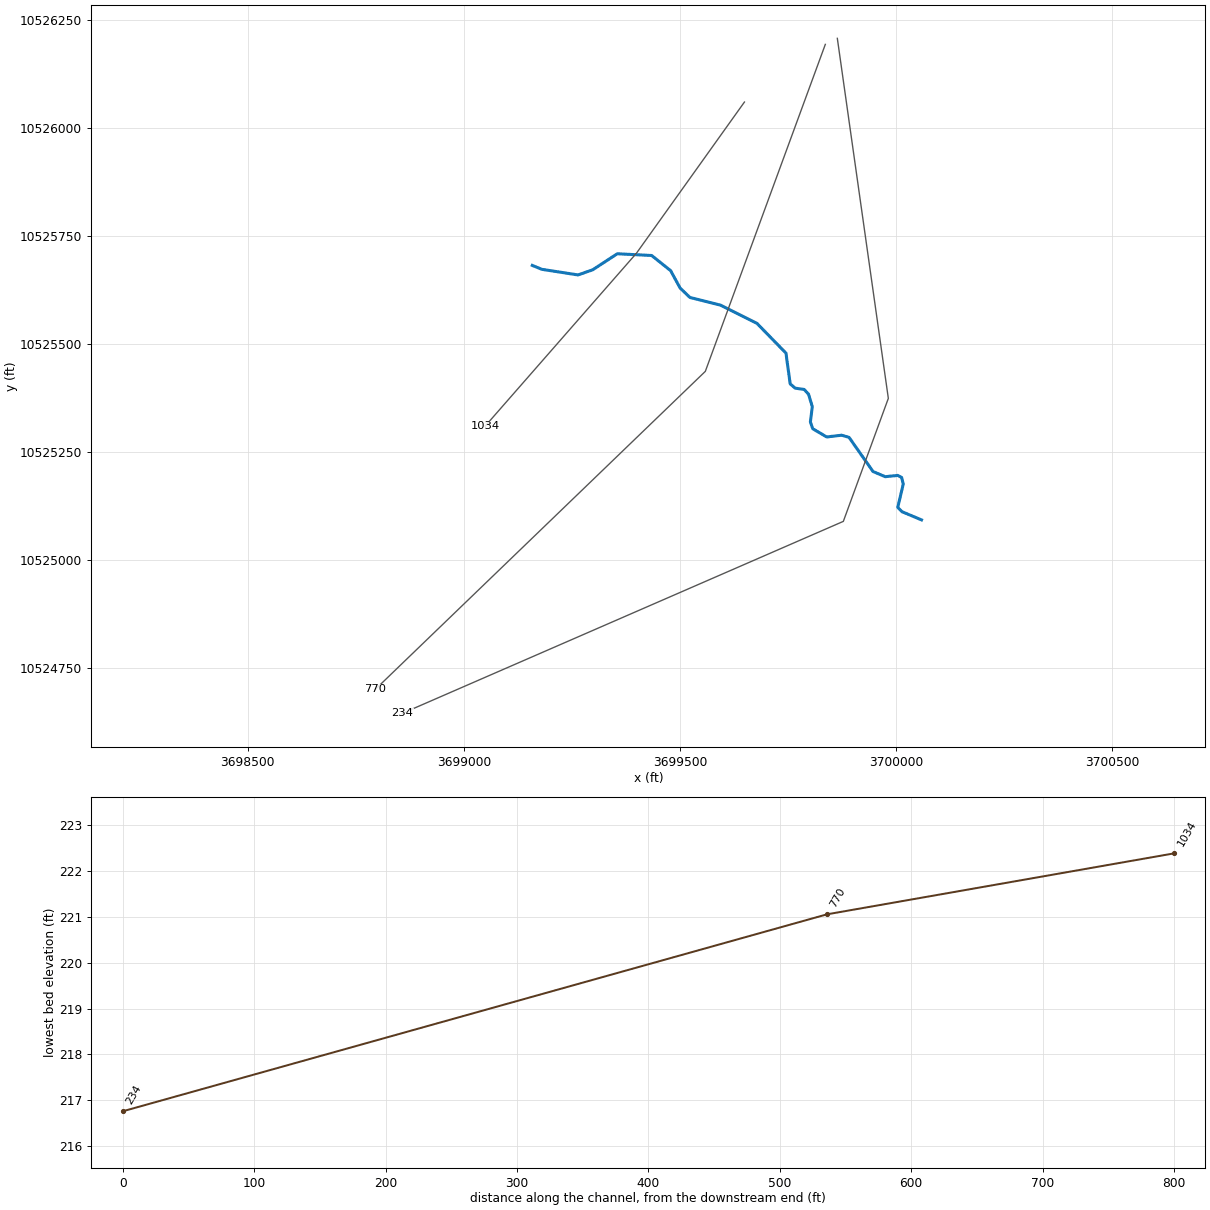
--- UNT 188 IN UKCR.prj (project) ---

Proj Title=UNT 188 IN UKCR Base Level Engineering
Current Plan=p01
Default Exp/Contr=0.3,0.1
English Units
Geom File=g01
Flow File=f01
Plan File=p01
BEGIN DESCRIPTION:
UNT 188 IN UKCR
END DESCRIPTION:

--- UNT 188 IN UKCR.p01 (plan) ---

Plan Title=Multiple Run
Short Identifier=Multiple
Geom File=g01
Flow File=f01
Subcritical Flow
K Sum by GR= 0
Std Step Tol= 0.01
Critical Tol= 0.01
Num of Std Step Trials= 20
Max Error Tol= 0.3
Flow Tol Ratio= 0.001
Split Flow NTrial= 30
Split Flow Tol= 0.02
Split Flow Ratio= 0.02
Log Output Level= 0
Friction Slope Method= 1
Unsteady Friction Slope Method= 2
Unsteady Bridges Friction Slope Method= 1
Parabolic Critical Depth
Global Vel Dist=  1 , 1 , 1
Global Log Level= 0
CheckData=True
Encroach Param= -1, 0, 0, 0
BEGIN DESCRIPTION:
Multiple Run
END DESCRIPTION:

--- UNT 188 IN UKCR.f01 (steady flow) ---

Flow Title=Multiple
Number of Profiles=7
Profile Names=10-year,25-year,50-year,1pct_min,100-year,1pct_plu,500-year
River Rch & RM= UNT 188 IN UKCR,Reach-1,1034
     524     708     860     768    1039    1405    1521
Boundary for River Rch & Prof#=UNT 188 IN UKCR,Reach-1,1
Up Type=0
Dn Type=3
Dn Slope=0.005
Boundary for River Rch & Prof#=UNT 188 IN UKCR,Reach-1,2
Up Type=0
Dn Type=3
Dn Slope=0.005
Boundary for River Rch & Prof#=UNT 188 IN UKCR,Reach-1,3
Up Type=0
Dn Type=3
Dn Slope=0.005
Boundary for River Rch & Prof#=UNT 188 IN UKCR,Reach-1,4
Up Type=0
Dn Type=3
Dn Slope=0.005
Boundary for River Rch & Prof#=UNT 188 IN UKCR,Reach-1,5
Up Type=0
Dn Type=3
Dn Slope=0.005
Boundary for River Rch & Prof#=UNT 188 IN UKCR,Reach-1,6
Up Type=0
Dn Type=3
Dn Slope=0.005
Boundary for River Rch & Prof#=UNT 188 IN UKCR,Reach-1,7
Up Type=0
Dn Type=3
Dn Slope=0.005

--- UNT 188 IN UKCR.g01 (geometry) ---

Geom Title=Existing Conditions

River Reach=UNT 188 IN UKCR,Reach-1
Reach XY= 30
      3699158.57     10525682.08      3699180.75     10525673.00
      3699264.50     10525660.00      3699298.50     10525672.00
      3699355.25     10525709.00      3699435.00     10525705.00
      3699478.75     10525670.00      3699500.50     10525630.00
      3699523.25     10525608.00      3699594.50     10525590.00
      3699678.50     10525548.00      3699745.75     10525479.00
      3699755.50     10525408.00      3699766.75     10525398.00
      3699787.75     10525395.00      3699798.00     10525384.00
      3699806.75     10525355.00      3699802.25     10525320.00
      3699807.75     10525304.00      3699840.00     10525285.00
      3699874.75     10525289.00      3699891.75     10525284.00
      3699947.25     10525205.00      3699975.50     10525193.00
      3700004.50     10525196.00      3700013.50     10525191.00
      3700017.25     10525176.00      3700004.50     10525122.00
      3700014.25     10525112.00      3700059.50     10525093.00

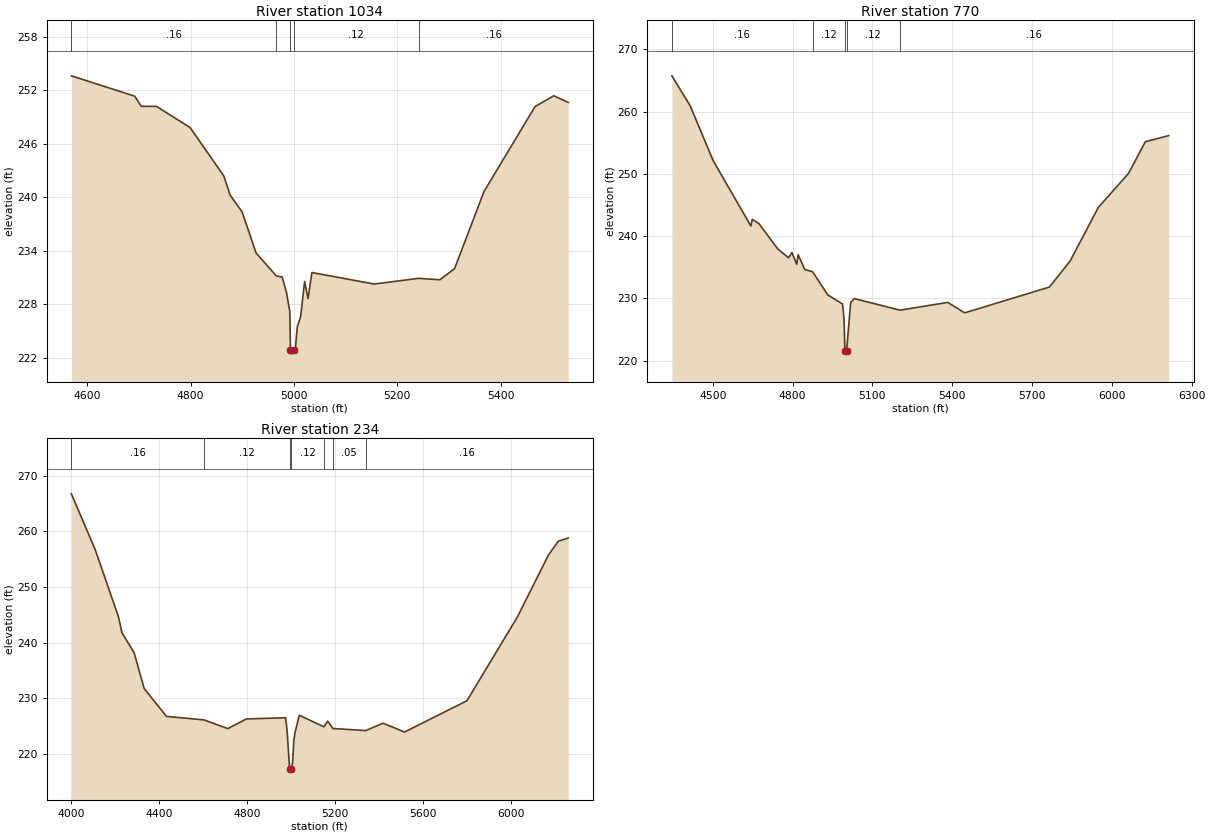
Type RM Length L Ch R = 1,1034,264,264,264
BEGIN DESCRIPTION:
UNT 188 IN UKCR 2.0
END DESCRIPTION:
XS GIS Cut Line= 3
      3699649.63     10526060.21      3699399.61     10525710.19
      3699049.58     10525310.15
#Sta/Elev= 30
  4569.3  253.64  4692.2  251.35  4704.5  250.22  4734.0  250.21  4799.1  247.83
  4864.3  242.41  4876.6  240.25  4899.9  238.35  4926.9  233.74  4966.3  231.16
  4977.3  231.06  4985.9  229.27  4992.1  227.18  4993.4  222.89  4996.1  222.39
  4999.4  222.89  5002.8  222.89  5006.6  225.44  5013.2  226.64  5020.8  230.55
  5027.4  228.62  5035.0  231.55  5155.6  230.26  5241.5  230.90  5282.8  230.74
  5311.2  232.00  5368.2  240.66  5466.9  250.19  5503.0  251.40  5531.0  250.66
#Mann=5,-1,0
  4569.3    0.16       0  4966.3    0.12       0  4993.4    0.07       0
  4999.4    0.12       0  5241.5    0.16       0
Bank Sta=4993.4,4999.4
Exp/Cntr=0.3,0.1

Type RM Length L Ch R = 1,770,536,536,536
BEGIN DESCRIPTION:
Mapping XS c29bf8f1
END DESCRIPTION:
XS GIS Cut Line= 3
      3699836.85     10526193.72      3699559.08     10525436.80
      3698795.21     10524700.70
#Sta/Elev= 30
  4346.6  265.76  4415.4  260.94  4501.5  252.15  4643.3  241.64  4648.7  242.70
  4673.8  242.02  4744.5  237.95  4785.1  236.54  4797.7  237.38  4815.6  235.49
  4821.0  237.03  4846.1  234.64  4875.2  234.30  4932.3  230.58  4987.9  229.11
  4993.3  226.82  4997.1  221.56  4999.9  221.06  5003.1  221.56  5018.4  229.35
  5032.1  229.98  5203.9  228.12  5383.5  229.37  5447.1  227.69  5765.3  231.83
  5843.3  236.02  5949.2  244.63  6062.4  250.07  6126.0  255.18  6213.7  256.16
#Mann=5,-1,0
  4346.6    0.16       0  4875.2    0.12       0  4997.1    0.07       0
  5003.1    0.12       0  5203.9    0.16       0
Bank Sta=4997.1,5003.1
Exp/Cntr=0.3,0.1

Type RM Length L Ch R = 1,234,0,0,0
BEGIN DESCRIPTION:
UNT 188 IN UKCR 1.0
END DESCRIPTION:
XS GIS Cut Line= 4
      3699864.63     10526207.67      3699982.69     10525374.30
      3699878.53     10525089.58      3698857.75     10524645.16
#Sta/Elev= 30
  4002.1  266.74  4110.7  256.68  4216.3  244.64  4231.9  241.80  4287.3  238.20
  4332.9  231.79  4434.3  226.77  4605.0  226.14  4713.2  224.57  4797.4  226.31
  4975.9  226.52  4982.5  224.29  4994.2  217.26  4997.0  216.76  5000.2  217.26
  5007.7  218.48  5013.0  222.38  5018.5  223.85  5038.2  226.97  5149.9  224.91
  5167.6  225.92  5190.5  224.60  5340.1  224.22  5418.5  225.55  5516.6  223.96
  5800.2  229.58  6029.2  244.61  6171.0  255.77  6215.1  258.22  6260.3  258.81
#Mann=7,-1,0
  4002.1    0.16       0  4605.0    0.12       0  4994.2    0.07       0
  5000.2    0.12       0  5149.9    0.16       0  5190.5    0.05       0
  5340.1    0.16       0
Bank Sta=4994.2,5000.2
Exp/Cntr=0.3,0.1

Chan Stop Cuts=-1