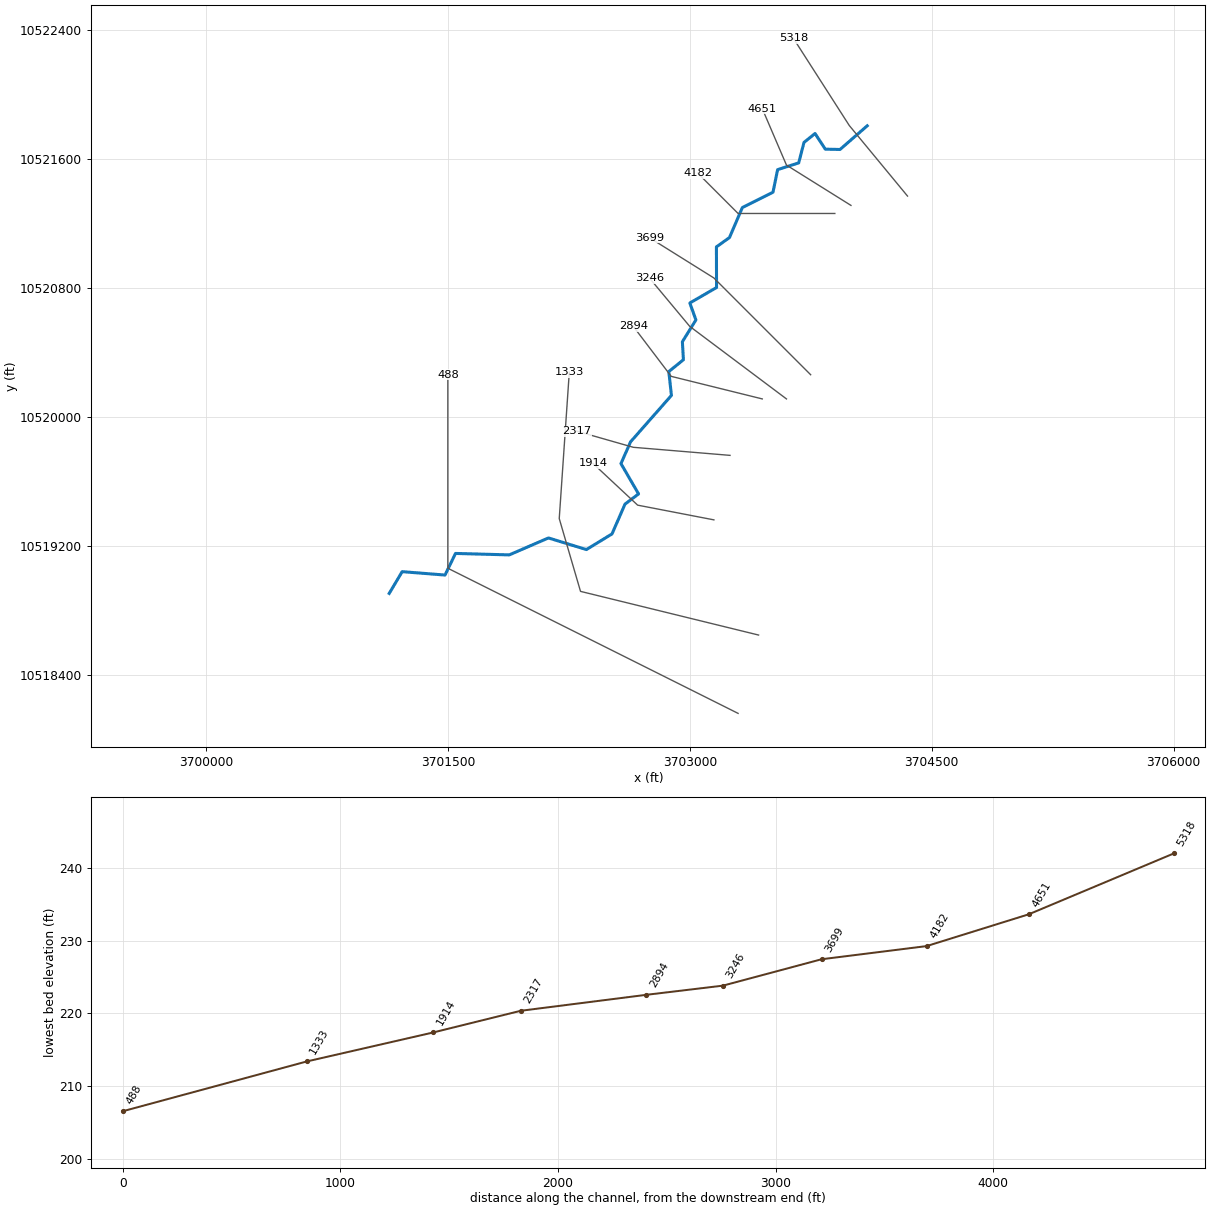
--- UNT 190 IN UKCR.prj (project) ---

Proj Title=UNT 190 IN UKCR Base Level Engineering
Current Plan=p01
Default Exp/Contr=0.3,0.1
English Units
Geom File=g01
Flow File=f01
Plan File=p01
Y Axis Title=Elevation
X Axis Title(PF)=Main Channel Distance
X Axis Title(XS)=Station
BEGIN DESCRIPTION:
UNT 190 IN UKCR
END DESCRIPTION:
DSS Export Rating Curves= 0
DSS Export Rating Curve Sorted= 0
DSS Export Volume Flow Curves= 0
DXF OffsetX= 0
DXF OffsetY= 0
DXF ScaleX= 1
DXF ScaleY= 10

--- UNT 190 IN UKCR.p01 (plan) ---

Plan Title=Multiple Run
Short Identifier=Multiple
Geom File=g01
Flow File=f01
Subcritical Flow
K Sum by GR= 0
Std Step Tol= 0.01
Critical Tol= 0.01
Num of Std Step Trials= 20
Max Error Tol= 0.3
Flow Tol Ratio= 0.001
Split Flow NTrial= 30
Split Flow Tol= 0.02
Split Flow Ratio= 0.02
Log Output Level= 0
Friction Slope Method= 1
Unsteady Friction Slope Method= 2
Unsteady Bridges Friction Slope Method= 1
Parabolic Critical Depth
Global Vel Dist=  1 , 1 , 1
Global Log Level= 0
CheckData=True
Encroach Param= -1, 0, 0, 0
BEGIN DESCRIPTION:
Multiple Run
END DESCRIPTION:

--- UNT 190 IN UKCR.f01 (steady flow) ---

Flow Title=Multiple
Number of Profiles=7
Profile Names=10-year,25-year,50-year,1pct_min,100-year,1pct_plu,500-year
River Rch & RM= UNT 190 IN UKCR,Reach-1,5318
     562     768     941     848    1147    1551    1710
Boundary for River Rch & Prof#=UNT 190 IN UKCR,Reach-1,1
Up Type=0
Dn Type=3
Dn Slope=0.005
Boundary for River Rch & Prof#=UNT 190 IN UKCR,Reach-1,2
Up Type=0
Dn Type=3
Dn Slope=0.005
Boundary for River Rch & Prof#=UNT 190 IN UKCR,Reach-1,3
Up Type=0
Dn Type=3
Dn Slope=0.005
Boundary for River Rch & Prof#=UNT 190 IN UKCR,Reach-1,4
Up Type=0
Dn Type=3
Dn Slope=0.005
Boundary for River Rch & Prof#=UNT 190 IN UKCR,Reach-1,5
Up Type=0
Dn Type=3
Dn Slope=0.005
Boundary for River Rch & Prof#=UNT 190 IN UKCR,Reach-1,6
Up Type=0
Dn Type=3
Dn Slope=0.005
Boundary for River Rch & Prof#=UNT 190 IN UKCR,Reach-1,7
Up Type=0
Dn Type=3
Dn Slope=0.005

--- UNT 190 IN UKCR.g01 (geometry) ---

Geom Title=Existing Conditions
Program Version=4.10

River Reach=UNT 190 IN UKCR ,Reach-1
Reach XY= 30
      3704100.21     10521803.77      3703931.75       10521657.
       3703840.5       10521659.      3703776.75       10521756.
      3703708.25       10521701.       3703675.5       10521574.
      3703544.75       10521532.        3703516.       10521392.
      3703326.25       10521297.      3703246.25       10521111.
      3703165.25       10521053.        3703166.       10520801.
       3703000.5       10520705.        3703038.       10520600.
      3702954.25       10520465.       3702960.5       10520353.
        3702870.       10520280.      3702886.25       10520132.
      3702632.75       10519844.      3702573.25       10519709.
       3702682.5       10519521.       3702598.5       10519458.
      3702517.75       10519273.        3702359.       10519176.
      3702123.75       10519248.       3701880.5       10519143.
      3701547.25       10519152.      3701482.25       10519018.
       3701216.5       10519039.        3701136.       10518904.

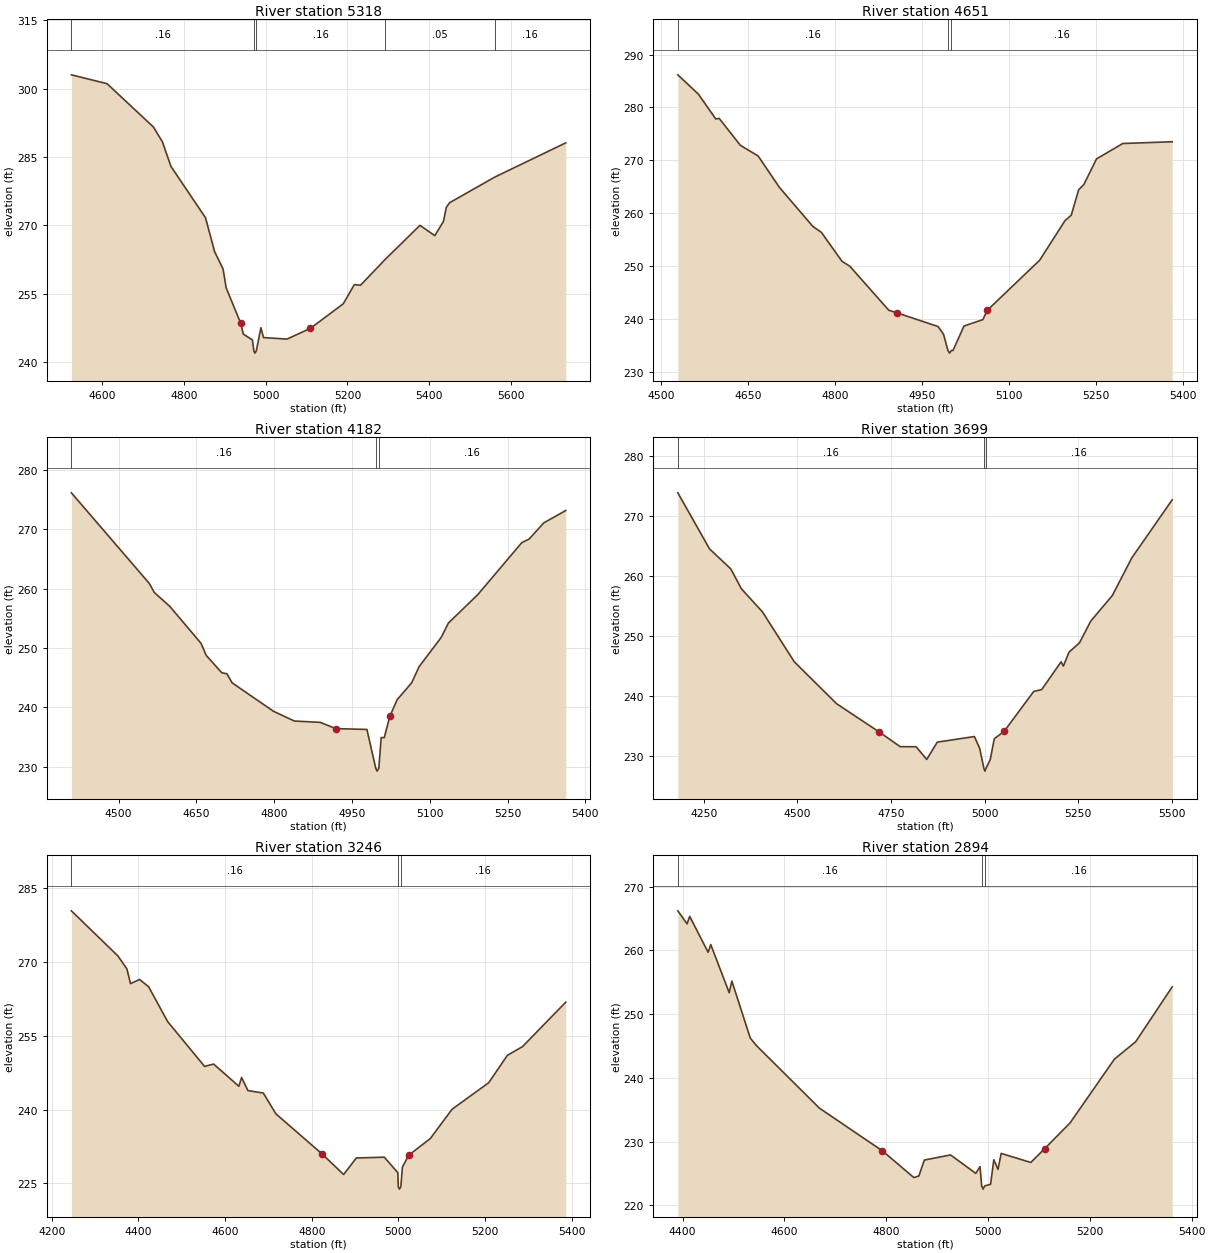
Type RM Length L Ch R = 1 ,5318    ,667,667,667
BEGIN DESCRIPTION:
UNT 190 IN UKCR 10.0
END DESCRIPTION:
XS GIS Cut Line= 3
      3704350.27     10521368.09      3703989.14     10521805.62
      3703642.57     10522346.26
#Sta/Elev= 30
  4524.6  303.05  4611.8  301.11  4725.2  291.61  4747.3  288.35  4768.2  282.95
  4852.8  271.68    4875  264.24  4895.8  260.42  4903.3  256.29  4938.8  248.54
  4945.3  246.15  4967.5  244.86    4971  242.47  4973.8  241.97    4977  242.47
  4988.3  247.54  4994.8  245.38  5052.2  245.05  5109.2   247.4  5189.7  252.79
  5216.8  257.01    5232  256.87  5291.3  262.44  5377.4  270.02  5413.7  267.76
  5434.9  270.86  5441.8  273.96  5450.1  274.99  5560.8  280.62  5734.1  288.12
#Mann= 5 ,-1 , 0
  4524.6     .16       0    4971     .07       0    4977     .16       0
  5291.3     .05       0  5560.8     .16       0
Bank Sta=4938.8,5109.2
XS Rating Curve= 0 ,0
Exp/Cntr=0.3,0.1

Type RM Length L Ch R = 1 ,4651    ,469,469,469
BEGIN DESCRIPTION:
UNT 190 IN UKCR 9.0
END DESCRIPTION:
XS GIS Cut Line= 3
      3703999.57     10521310.21      3703599.61     10521560.19
      3703449.62     10521910.15
#Sta/Elev= 30
    4529  286.17  4564.3  282.54  4594.4  277.84  4600.3  277.94  4636.9  272.85
  4667.5  270.84  4704.1  264.92  4761.9  257.53  4776.6  256.41    4812  250.96
  4825.5  250.03  4892.7  241.71  4906.3  241.24  4977.7  238.63  4987.1  237.18
  4994.7  234.11  4997.5  233.61  5000.7  234.11  5003.4  234.11  5022.4  238.73
    5055  239.94  5062.3  241.67    5153  251.17  5196.5  258.62  5207.4  259.67
  5220.1  264.46  5229.1  265.45  5250.9  270.29  5296.2   273.2  5381.4  273.53
#Mann= 3 ,-1 , 0
    4529     .16       0  4994.7     .07       0  5000.7     .16       0
Bank Sta=4906.3,5062.3
XS Rating Curve= 0 ,0
Exp/Cntr=0.3,0.1

Type RM Length L Ch R = 1 ,4182    ,483,483,483
BEGIN DESCRIPTION:
UNT 190 IN UKCR 8.0
END DESCRIPTION:
XS GIS Cut Line= 3
      3703899.57     10521260.19      3703299.61     10521260.19
      3703049.62     10521510.18
#Sta/Elev= 30
  4408.8  276.12  4558.8  260.89  4568.8  259.33  4598.8  256.98  4658.8  250.78
  4668.8  248.75  4698.8  245.82  4708.8  245.64  4718.8  244.12  4798.8  239.32
  4838.8  237.69  4888.8  237.46  4918.8  236.41  4978.8  236.27  4995.8  229.75
  4998.5  229.25  5001.8  229.75  5006.3   234.9  5012.3   234.9  5022.9  238.46
    5037  241.26  5065.3  244.15  5079.5  246.85  5121.9  251.75    5136  254.19
  5192.6  258.97  5277.5  267.73  5291.6  268.33  5319.9  271.06  5362.3  273.14
#Mann= 3 ,-1 , 0
  4408.8     .16       0  4995.8     .07       0  5001.8     .16       0
Bank Sta=4918.8,5022.9
XS Rating Curve= 0 ,0
Exp/Cntr=0.3,0.1

Type RM Length L Ch R = 1 ,3699    ,453,453,453
BEGIN DESCRIPTION:
UNT 190 IN UKCR 7.0
END DESCRIPTION:
XS GIS Cut Line= 3
      3703749.59     10520260.21      3703149.61     10520860.19
      3702749.61     10521110.19
#Sta/Elev= 30
  4180.6  273.89  4265.4  264.52    4322   261.2  4350.3  257.88  4406.8     254
  4491.7  245.68  4604.8  238.68    4718  233.99  4774.5  231.52    4817  231.51
  4845.3  229.39  4873.5  232.28  4972.5  233.21  4986.7  231.24  4997.8  227.94
  5000.6  227.44  5003.8  227.94    5015  229.39  5025.6  232.84  5052.1  234.08
  5131.1  240.75  5152.3  241.05  5204.2  245.69  5210.1  244.97  5225.4   247.3
  5253.2  248.85  5283.2  252.47    5341  256.76  5392.9  263.03  5500.8  272.73
#Mann= 3 ,-1 , 0
  4180.6     .16       0  4997.8     .07       0  5003.8     .16       0
Bank Sta=4718,5052.1
XS Rating Curve= 0 ,0
Exp/Cntr=0.3,0.1

Type RM Length L Ch R = 1 ,3246    ,352,352,352
BEGIN DESCRIPTION:
UNT 190 IN UKCR 6.0
END DESCRIPTION:
XS GIS Cut Line= 3
      3703599.59      10520110.2      3702999.61     10520560.19
       3702749.6      10520860.2
#Sta/Elev= 30
  4245.5  280.41  4352.8  271.24  4373.6   268.6  4381.9  265.61  4402.8  266.45
  4423.6  264.99  4467.4  257.91  4552.8  248.77  4573.6  249.26  4631.9  244.73
  4638.2  246.52  4652.8  243.85  4688.2  243.36  4717.4  239.12  4823.6  230.99
  4873.6  226.79  4902.8  230.15  4967.4  230.32  4998.7  227.15  4999.6  224.32
  5002.4  223.82  5005.6  224.32  5009.1  228.28  5023.5   230.7  5073.6  234.11
  5123.7  240.06  5208.3  245.46  5251.3  251.02  5286.4  252.81    5386  261.83
#Mann= 3 ,-1 , 0
  4245.5     .16       0  4999.6     .07       0  5005.6     .16       0
Bank Sta=4823.6,5023.5
XS Rating Curve= 0 ,0
Exp/Cntr=0.3,0.1

Type RM Length L Ch R = 1 ,2894    ,577,577,577
BEGIN DESCRIPTION:
UNT 190 IN UKCR 5.0
END DESCRIPTION:
XS GIS Cut Line= 3
       3703449.6     10520110.19      3702884.97     10520250.07
      3702649.62     10520560.17
#Sta/Elev= 30
  4390.8  266.19  4408.9  264.15  4414.1  265.32  4450.3  259.69  4455.5   260.9
  4491.7  253.35  4496.9  255.18  4533.1  246.24  4545.3  245.05    4669  235.25
  4792.6  228.56  4854.4  224.37  4864.3  224.63    4875  227.12  4926.5  227.92
    4976  225.03  4984.3  226.09  4987.6  223.06  4990.3  222.56  4993.6  223.06
  5005.1  223.33  5011.4  227.17  5019.7  225.66  5025.9  228.16  5084.1  226.74
  5111.2   228.9  5161.1  232.93  5248.4  242.95  5290.1  245.67  5361.8  254.27
#Mann= 3 ,-1 , 0
  4390.8     .16       0  4987.6     .07       0  4993.6     .16       0
Bank Sta=4792.6,5111.2
XS Rating Curve= 0 ,0
Exp/Cntr=0.3,0.1

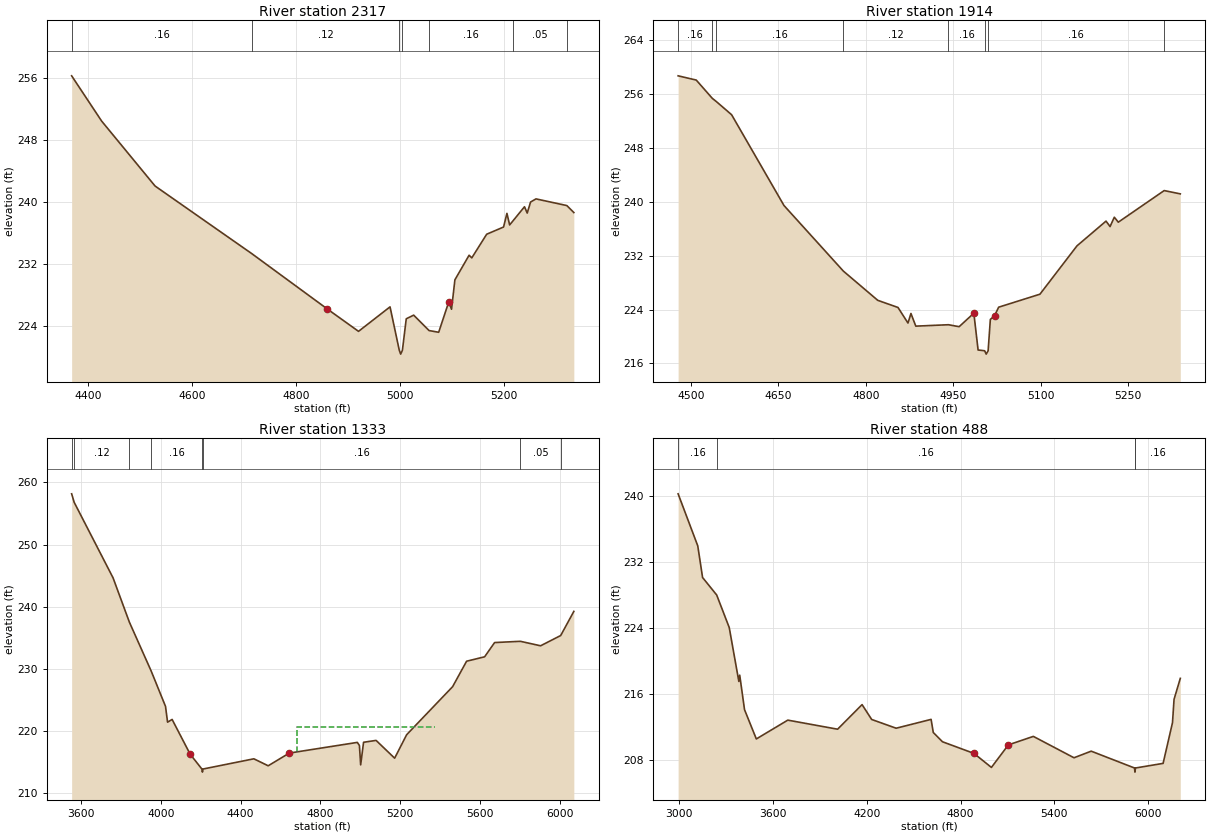
Type RM Length L Ch R = 1 ,2317    ,403,403,403
BEGIN DESCRIPTION:
UNT 190 IN UKCR 4.0
END DESCRIPTION:
XS GIS Cut Line= 3
      3703249.59     10519760.19      3702649.61     10519810.19
      3702299.57      10519910.2
#Sta/Elev= 30
  4367.7  256.28  4425.4  250.44  4528.2  242.06  4714.6  233.32  4859.4   226.2
  4919.6  223.31  4980.2  226.47    4998  220.87  5000.7  220.37    5004  220.87
  5011.4  224.93  5025.7   225.4  5055.3  223.41  5073.8  223.19  5093.3  227.13
  5098.5  226.16    5105  229.96  5132.3  233.13  5137.5  232.79  5166.1  235.84
  5198.6  236.77  5205.1  238.53  5210.3  237.04  5216.3  237.53  5238.9  239.39
  5244.1  238.57  5250.6     240    5261   240.4  5320.3  239.54  5333.8  238.64
#Mann= 7 ,-1 , 0
  4367.7     .16       0  4714.6     .12       0    4998     .07       0
    5004     .12       0  5055.3     .16       0  5216.3     .05       0
  5320.3     .12       0
Bank Sta=4859.4,5093.3
XS Rating Curve= 0 ,0
Exp/Cntr=0.3,0.1

Type RM Length L Ch R = 1 ,1914    ,581,581,581
BEGIN DESCRIPTION:
UNT 190 IN UKCR 3.0
END DESCRIPTION:
XS GIS Cut Line= 3
      3703149.65     10519360.18      3702676.64     10519451.46
      3702399.61     10519710.19
#Sta/Elev= 30
  4478.4  258.67  4509.5  258.04  4537.1  255.32    4543  254.92  4570.1   252.9
  4659.9  239.43  4761.6  229.71  4820.6  225.37  4855.3  224.31  4872.4     222
  4877.5  223.42  4885.8  221.54  4941.8  221.75  4960.1  221.46  4985.3  223.46
  4992.6     218  5003.8  217.89  5006.5  217.39  5009.8  217.89  5013.6  222.54
  5020.9  223.09  5027.8  224.35  5098.6  226.28  5162.1  233.45  5211.9  237.12
  5218.8  236.31  5226.1   237.7  5232.9  236.96  5311.6  241.65  5339.2  241.16
#Mann= 8 ,-1 , 0
  4478.4     .16       0  4537.1     .12       0    4543     .16       0
  4761.6     .12       0  4941.8     .16       0  5003.8     .07       0
  5009.8     .16       0  5311.6     .12       0
Bank Sta=4985.3,5020.9
XS Rating Curve= 0 ,0
Exp/Cntr=0.3,0.1

Type RM Length L Ch R = 1 ,1333    ,845,845,845
BEGIN DESCRIPTION:
UNT 190 IN UKCR 2.0
END DESCRIPTION:
XS GIS Cut Line= 4
      3703426.67     10518645.89      3702322.47     10518916.73
      3702190.53     10519368.12      3702252.93     10520276.48
#Sta/Elev= 30
  3552.6  258.15  3565.2  256.79  3760.1  244.65  3841.8  237.54  3951.1  229.68
  4023.2  223.98  4033.5  221.44  4056.3  221.88  4146.8  216.29  4205.5  213.91
  4208.3  213.41  4211.5  213.91    4466  215.55    4538  214.43  4643.6  216.47
  4984.8  218.19  4995.3  217.69  5001.6  214.58  5016.1  218.21  5078.9  218.51
  5171.9  215.65    5232  219.42  5462.6  227.15  5532.7  231.24    5623  231.95
  5673.1  234.24  5802.1  234.44  5903.6  233.72  6004.4  235.37  6070.3  239.25
#Mann= 8 ,-1 , 0
  3552.6     .16       0  3565.2     .12       0  3841.8     .16       0
  3951.1     .16       0  4205.5     .07       0  4211.5     .16       0
  5802.1     .05       0  6004.4     .16       0
#XS Ineff= 1 ,-1
 4682.95  5373.3  220.65
Permanent Ineff=
       F
Bank Sta=4146.8,4643.6
XS Rating Curve= 0 ,0
Exp/Cntr=0.3,0.1

Type RM Length L Ch R = 1 ,488     ,0,0,0
BEGIN DESCRIPTION:
UNT 190 IN UKCR 1.0
END DESCRIPTION:
XS GIS Cut Line= 3
       3703299.6     10518160.19      3701499.61     10519060.19
      3701499.61     10520260.14
#Sta/Elev= 30
  2992.8   240.3  3118.6  233.99  3149.3  230.16  3239.6  228.04  3319.8   224.1
  3381.3  217.57  3386.9  218.33  3417.6  214.15  3493.1   210.6  3694.4  212.88
    4013  211.78  4169.5  214.76    4231  212.96  4387.5   211.9  4611.1  212.97
  4625.1  211.38  4683.8  210.26  4885.1  208.85  4996.9  207.15  5105.3  209.88
  5265.2  210.91  5525.2  208.32  5635.2  209.12  5912.2  207.08    5915  206.58
  5918.2  207.08  6095.2  207.64  6155.2  212.57  6165.2   215.4  6205.2  217.94
#Mann= 4 ,-1 , 0
  2992.8     .16       0  3239.6     .16       0  5912.2     .07       0
  5918.2     .16       0
Bank Sta=4885.1,5105.3
XS Rating Curve= 0 ,0
Exp/Cntr=0.3,0.1

Chan Stop Cuts=-1
Use User Specified Reach Order=0
Composite Channel Slope=5