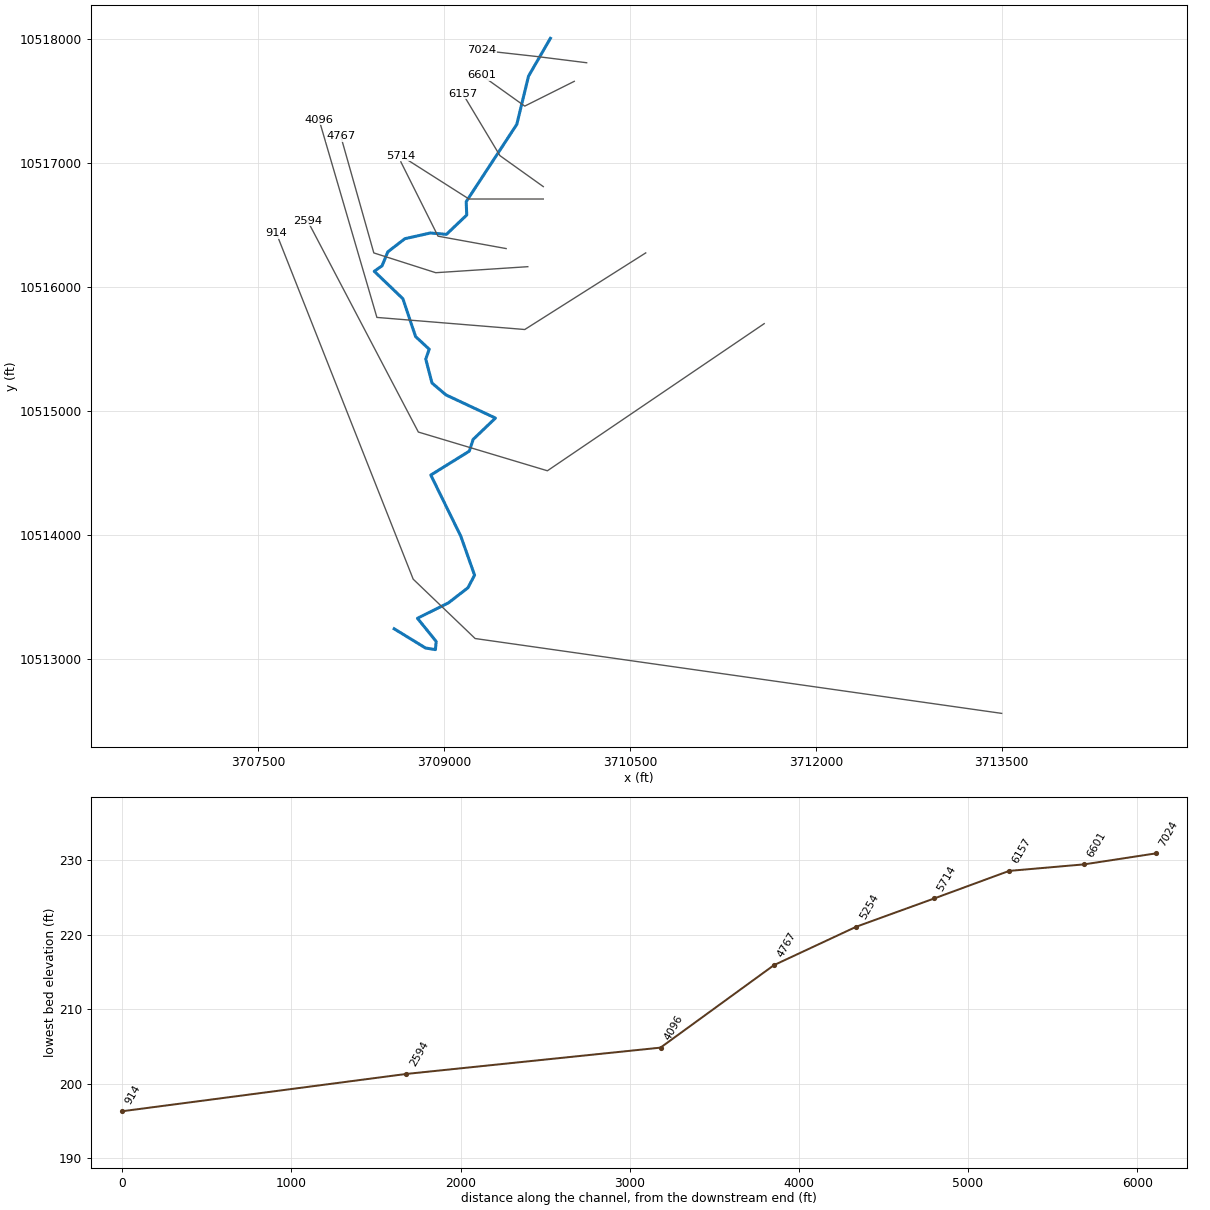
--- UNT 193 IN UKCR.prj (project) ---

Proj Title=UNT 193 IN UKCR Base Level Engineering
Current Plan=p01
Default Exp/Contr=0.3,0.1
English Units
Geom File=g01
Flow File=f01
Plan File=p01
Y Axis Title=Elevation
X Axis Title(PF)=Main Channel Distance
X Axis Title(XS)=Station
BEGIN DESCRIPTION:
UNT 193 IN UKCR
END DESCRIPTION:
DSS Export Rating Curves= 0
DSS Export Rating Curve Sorted= 0
DSS Export Volume Flow Curves= 0
DXF OffsetX= 0
DXF OffsetY= 0
DXF ScaleX= 1
DXF ScaleY= 10

--- UNT 193 IN UKCR.p01 (plan) ---

Plan Title=Multiple Run
Short Identifier=Multiple
Geom File=g01
Flow File=f01
Subcritical Flow
K Sum by GR= 0
Std Step Tol= 0.01
Critical Tol= 0.01
Num of Std Step Trials= 20
Max Error Tol= 0.3
Flow Tol Ratio= 0.001
Split Flow NTrial= 30
Split Flow Tol= 0.02
Split Flow Ratio= 0.02
Log Output Level= 0
Friction Slope Method= 1
Unsteady Friction Slope Method= 2
Unsteady Bridges Friction Slope Method= 1
Parabolic Critical Depth
Global Vel Dist=  1 , 1 , 1
Global Log Level= 0
CheckData=True
Encroach Param= -1, 0, 0, 0
BEGIN DESCRIPTION:
Multiple Run
END DESCRIPTION:

--- UNT 193 IN UKCR.f01 (steady flow) ---

Flow Title=Multiple
Number of Profiles=7
Profile Names=10-year,25-year,50-year,1pct_min,100-year,1pct_plu,500-year
River Rch & RM= UNT 193 IN UKCR,Reach-1,7024
     675     937    1159    1055    1427    1929    2169
River Rch & RM= UNT 193 IN UKCR,Reach-1,6157
     722     999    1232    1118    1512    2044    2284
Boundary for River Rch & Prof#=UNT 193 IN UKCR,Reach-1,1
Up Type=0
Dn Type=3
Dn Slope=0.005
Boundary for River Rch & Prof#=UNT 193 IN UKCR,Reach-1,2
Up Type=0
Dn Type=3
Dn Slope=0.005
Boundary for River Rch & Prof#=UNT 193 IN UKCR,Reach-1,3
Up Type=0
Dn Type=3
Dn Slope=0.005
Boundary for River Rch & Prof#=UNT 193 IN UKCR,Reach-1,4
Up Type=0
Dn Type=3
Dn Slope=0.005
Boundary for River Rch & Prof#=UNT 193 IN UKCR,Reach-1,5
Up Type=0
Dn Type=3
Dn Slope=0.005
Boundary for River Rch & Prof#=UNT 193 IN UKCR,Reach-1,6
Up Type=0
Dn Type=3
Dn Slope=0.005
Boundary for River Rch & Prof#=UNT 193 IN UKCR,Reach-1,7
Up Type=0
Dn Type=3
Dn Slope=0.005

--- UNT 193 IN UKCR.g01 (geometry) ---

Geom Title=Existing Conditions
Program Version=4.10

River Reach=UNT 193 IN UKCR ,Reach-1
Reach XY= 30
      3709856.75     10518007.21      3709680.25       10517702.
      3709585.75       10517313.      3709177.25       10516689.
       3709181.5       10516581.      3709017.75       10516425.
       3708888.5       10516436.       3708682.5       10516390.
      3708544.75       10516284.        3708498.       10516171.
        3708435.       10516127.      3708666.25       10515905.
       3708768.5       10515600.       3708878.5       10515498.
      3708850.75       10515418.        3708901.       10515225.
      3709013.75       10515129.      3709413.25       10514942.
       3709233.5       10514770.      3709202.25       10514675.
       3708891.5       10514482.       3709133.5       10513989.
      3709244.75       10513674.        3709191.       10513572.
      3709034.75       10513451.      3708783.75       10513326.
      3708934.75       10513139.      3708928.75       10513073.
        3708849.       10513086.      3708595.75       10513241.

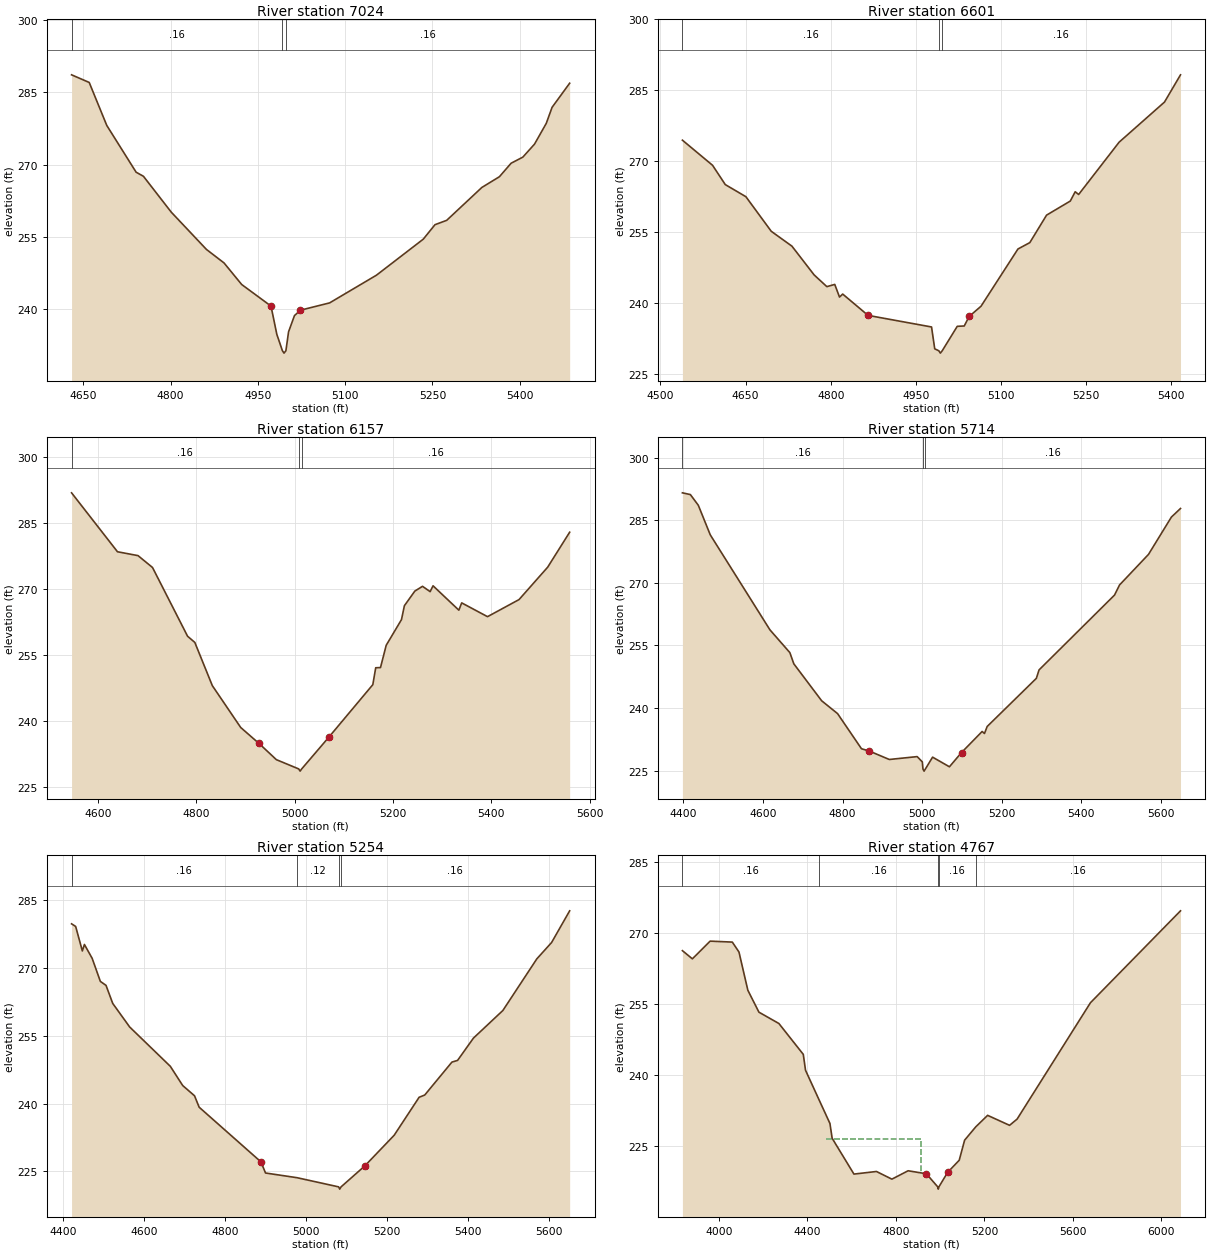
Type RM Length L Ch R = 1 ,7024    ,423,423,423
BEGIN DESCRIPTION:
UNT 193 IN UKCR 8.0
END DESCRIPTION:
XS GIS Cut Line= 3
      3710149.63     10517810.19      3709749.61     10517860.19
      3709299.61     10517910.19
#Sta/Elev= 30
  4629.8  288.66  4660.1  287.08  4690.3  278.16  4740.7  268.46  4753.3  267.61
  4801.1  260.17  4861.6  252.43  4891.8  249.63  4922.1  245.16  4972.5  240.68
  4982.5  234.82  4992.1  231.42  4994.9  230.92  4998.1  231.42  5002.7  235.35
  5012.8   238.7  5022.9  239.82  5073.2  241.34  5153.7  247.09  5234.2  254.57
  5254.3  257.57  5274.4  258.47  5334.8  265.29    5365  267.52  5385.1  270.32
  5405.2  271.58  5425.3  274.28  5445.5  278.59  5455.5  281.92  5485.7  286.92
#Mann= 3 ,-1 , 0
  4629.8     .16       0  4992.1     .07       0  4998.1     .16       0
Bank Sta=4972.5,5022.9
XS Rating Curve= 0 ,0
Exp/Cntr=0.3,0.1

Type RM Length L Ch R = 1 ,6601    ,444,444,444
BEGIN DESCRIPTION:
UNT 193 IN UKCR 7.0
END DESCRIPTION:
XS GIS Cut Line= 3
      3710049.61     10517660.19      3709649.61     10517460.19
      3709299.63     10517710.17
#Sta/Elev= 30
  4538.8  274.48  4591.9  269.17  4614.3  265.09  4650.6  262.53  4695.3  255.21
  4731.7  252.07  4770.8  245.99  4793.2  243.51  4807.1  243.98  4815.5   241.3
  4821.1  241.94  4865.8  237.43  4977.6  234.98  4983.2  230.36  4990.4  229.95
  4993.1  229.45  4996.4  229.95  5022.9  235.12  5035.2  235.19  5043.8   237.2
  5064.7  239.36  5129.8  251.47  5150.7  252.82  5180.2  258.63    5222  261.61
  5230.6  263.57  5236.7     263    5308  274.06  5387.9  282.54  5416.1   288.3
#Mann= 3 ,-1 , 0
  4538.8     .16       0  4990.4     .07       0  4996.4     .16       0
Bank Sta=4865.8,5043.8
XS Rating Curve= 0 ,0
Exp/Cntr=0.3,0.1

Type RM Length L Ch R = 1 ,6157    ,443,443,443
BEGIN DESCRIPTION:
UNT 193 IN UKCR 6.0
END DESCRIPTION:
XS GIS Cut Line= 3
      3709799.61     10516810.19      3709449.61     10517060.19
      3709149.62     10517560.18
#Sta/Elev= 30
  4546.3  291.94  4639.7  278.52  4681.5  277.64    4711  274.93  4782.3  259.28
    4797  257.88  4832.6  248.04  4890.4   238.5  4927.3   234.9  4962.9  231.18
  5008.4  229.07  5011.2  228.57  5014.4  229.07  5069.7  236.31  5159.1  248.26
    5165  252.11  5174.7  252.15  5186.3  257.22  5217.4  263.07  5223.3  266.23
  5244.6  269.57  5260.2  270.65  5275.7  269.44  5281.6  270.77  5334.1  265.22
  5339.9  266.88  5392.4  263.74  5456.5  267.63  5514.8  275.01  5559.5  282.97
#Mann= 3 ,-1 , 0
  4546.3     .16       0  5008.4     .07       0  5014.4     .16       0
Bank Sta=4927.3,5069.7
XS Rating Curve= 0 ,0
Exp/Cntr=0.3,0.1

Type RM Length L Ch R = 1 ,5714    ,460,460,460
BEGIN DESCRIPTION:
UNT 193 IN UKCR 5.0
END DESCRIPTION:
XS GIS Cut Line= 3
      3709799.64     10516710.19      3709199.61     10516710.19
      3708649.65     10517060.16
#Sta/Elev= 30
  4397.6  291.57  4417.6  291.15  4437.6  288.58  4467.6   281.5  4617.6  258.73
  4667.6  253.28  4677.6  250.59  4747.6  241.73  4787.6  238.65  4847.6  230.24
  4867.6  229.67  4917.6  227.66  4987.6  228.35  5000.6  227.08  5002.2  225.37
    5005  224.87  5008.2  225.37  5026.4  228.22  5068.7  225.91  5099.2  229.33
  5150.9  234.37  5156.8  233.89  5163.6  235.57  5287.2  247.11    5294  249.13
  5483.6  267.06  5496.3  269.49  5569.1  276.82  5626.7  285.77  5649.5  287.82
#Mann= 3 ,-1 , 0
  4397.6     .16       0  5002.2     .07       0  5008.2     .16       0
Bank Sta=4867.6,5099.2
XS Rating Curve= 0 ,0
Exp/Cntr=0.3,0.1

Type RM Length L Ch R = 1 ,5254    ,487,487,487
BEGIN DESCRIPTION:
UNT 193 IN UKCR 4.0
END DESCRIPTION:
XS GIS Cut Line= 3
      3709499.57      10516310.2      3708949.61     10516410.19
      3708649.61     10517010.19
#Sta/Elev= 30
  4421.4  279.83  4431.5  279.25    4448  273.83  4453.1  275.26  4472.2   272.2
  4492.5  267.08  4506.5   266.2    4523  262.21  4564.9  256.98  4665.3  248.27
  4695.8  244.02    4725  241.75  4736.4  239.22  4888.9  227.12  4900.3  224.65
  4978.1  223.61  5080.8  221.58  5083.5  221.08  5086.8  221.58  5145.3  226.21
    5218  233.02  5279.5  241.42  5293.4  241.92  5360.5  249.21  5374.5  249.59
  5413.6  254.52  5486.3  260.64  5570.1  272.07  5606.5  275.68  5651.2  282.71
#Mann= 4 ,-1 , 0
  4421.4     .16       0  4978.1     .12       0  5080.8     .07       0
  5086.8     .16       0
Bank Sta=4888.9,5145.3
XS Rating Curve= 0 ,0
Exp/Cntr=0.3,0.1

Type RM Length L Ch R = 1 ,4767    ,671,671,671
BEGIN DESCRIPTION:
Mapping XS fc2ba41e
END DESCRIPTION:
XS GIS Cut Line= 4
      3709674.55     10516163.97      3708931.45     10516115.35
      3708431.45     10516275.07      3708164.35     10517218.62
#Sta/Elev= 30
  3835.7  266.34  3880.7  264.61  3960.9  268.35  4061.1  268.15  4091.2  266.05
  4131.3  257.97  4181.4  253.33  4271.5  250.94  4381.8  244.41  4391.8  241.06
  4453.8  234.72  4502.1  229.81  4512.1  226.68  4610.6   219.1  4712.4  219.65
    4782  218.03  4855.3   219.8  4937.7  219.17  4988.7  216.42  4991.5  215.92
  4994.7  216.42  5033.7  219.45  5086.2  222.03  5110.6  226.27  5160.8  229.08
  5214.5  231.52  5313.6  229.41  5347.6  230.72  5679.1  255.33  6085.9  274.76
#Mann= 5 ,-1 , 0
  3835.7     .16       0  4453.8     .16       0  4988.7     .07       0
  4994.7     .16       0  5160.8     .16       0
#XS Ineff= 1 ,-1
 4483.52 4914.77  226.59
Permanent Ineff=
       F
Bank Sta=4937.7,5033.7
XS Rating Curve= 0 ,0
Exp/Cntr=0.3,0.1

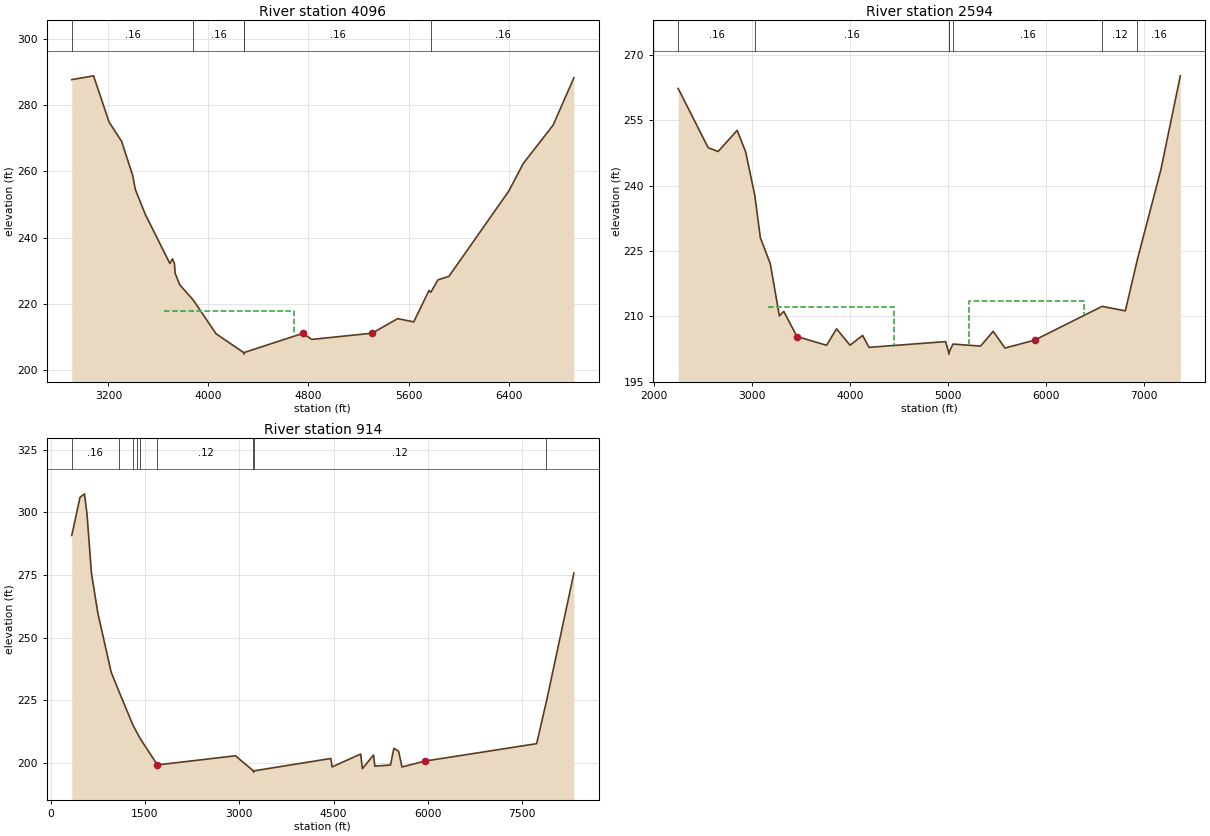
Type RM Length L Ch R = 1 ,4096    ,1502,1502,1502
BEGIN DESCRIPTION:
UNT 193 IN UKCR 3.0
END DESCRIPTION:
XS GIS Cut Line= 4
      3710626.51     10516275.33      3709649.92     10515656.82
      3708456.34     10515754.48      3707989.77      10517349.5
#Sta/Elev= 30
    2907  287.64  3081.1  288.79  3205.7  274.83  3305.8  269.01  3393.9  258.76
  3415.1  254.53  3495.2  246.99  3691.4  232.18  3712.5  233.58  3727.8  232.19
  3733.7  229.23  3770.2  225.77  3880.3  221.07  4060.2     211  4280.6  205.34
  4283.4  204.84  4286.6  205.34  4755.6  211.12  4825.8  209.28  5308.2  211.15
  5513.7  215.55  5641.6  214.57  5763.4  224.02  5778.5  223.52  5835.5  227.25
  5922.9   228.3  6401.7  254.03  6517.7  262.36  6756.4  273.93  6922.4  288.21
#Mann= 5 ,-1 , 0
    2907     .16       0  3880.3     .16       0  4280.6     .07       0
  4286.6     .16       0  5778.5     .16       0
#XS Ineff= 1 ,-1
 3647.73  4687.5  217.87
Permanent Ineff=
       F
Bank Sta=4755.6,5308.2
XS Rating Curve= 0 ,0
Exp/Cntr=0.3,0.1

Type RM Length L Ch R = 1 ,2594    ,1680,1680,1680
BEGIN DESCRIPTION:
UNT 193 IN UKCR 2.0
END DESCRIPTION:
XS GIS Cut Line= 4
      3711582.62     10515704.11      3709832.65     10514516.63
      3708790.98     10514829.13      3707895.76     10516536.28
#Sta/Elev= 30
  2243.1  262.28  2549.4  248.69  2651.2  247.81  2845.8  252.67  2932.6  247.73
  3026.2  237.73  3082.4  228.06  3184.2  222.06  3277.1  210.08  3321.9  211.12
  3456.7  205.35  3759.2  203.34    3861  207.12  3998.7  203.36  4127.5   205.6
  4192.4  202.87  4975.6  204.18  5005.4  201.81  5008.2  201.31  5011.4  201.81
  5050.8  203.62  5332.3  203.15  5461.4  206.55  5582.2   202.7  5885.6  204.53
  6574.5  212.27  6811.5  211.24  6935.5  223.12  7174.3  243.61  7373.1  265.18
#Mann= 7 ,-1 , 0
  2243.1     .16       0  3026.2     .16       0  5005.4     .07       0
  5011.4     .12       0  5050.8     .16       0  6574.5     .12       0
  6935.5     .16       0
#XS Ineff= 2 ,-1
  3162.5 4447.73  212.24 5211.36 6390.91   213.4
Permanent Ineff=
       F       F
Bank Sta=3456.7,5885.6
XS Rating Curve= 0 ,0
Exp/Cntr=0.3,0.1

Type RM Length L Ch R = 1 ,914     ,0,0,0
BEGIN DESCRIPTION:
UNT 193 IN UKCR 1.0
END DESCRIPTION:
XS GIS Cut Line= 4
      3713499.33     10512558.29      3709249.31     10513162.46
      3708749.31     10513641.63      3707645.14     10516433.31
#Sta/Elev= 30
   336.5  290.77   467.5  305.99   538.2  307.38   578.6  299.41   649.3  275.74
   750.3  259.93   962.5  236.24  1084.7  228.66  1310.7     215  1369.7  212.26
  1426.9   209.6  1699.8  199.18  2940.2  202.83  3225.8   196.8  3228.6   196.3
  3231.8   196.8  4457.2  201.75  4477.4  198.38  4931.7  203.52    4960   197.7
  5136.7  203.14  5157.8  198.71  5406.3  199.13    5460   205.8  5535.3  204.64
  5589.1  198.36  5954.6  200.71  7730.8  207.66  7886.1  224.41  8323.9  275.77
#Mann= 9 ,-1 , 0
   336.5     .16       0  1084.7     .12       0  1310.7     .16       0
  1369.7     .12       0  1426.9     .16       0  1699.8     .12       0
  3225.8     .07       0  3231.8     .12       0  7886.1     .16       0
Bank Sta=1699.8,5954.6
XS Rating Curve= 0 ,0
Exp/Cntr=0.3,0.1

Chan Stop Cuts=-1
Use User Specified Reach Order=0
Composite Channel Slope=5