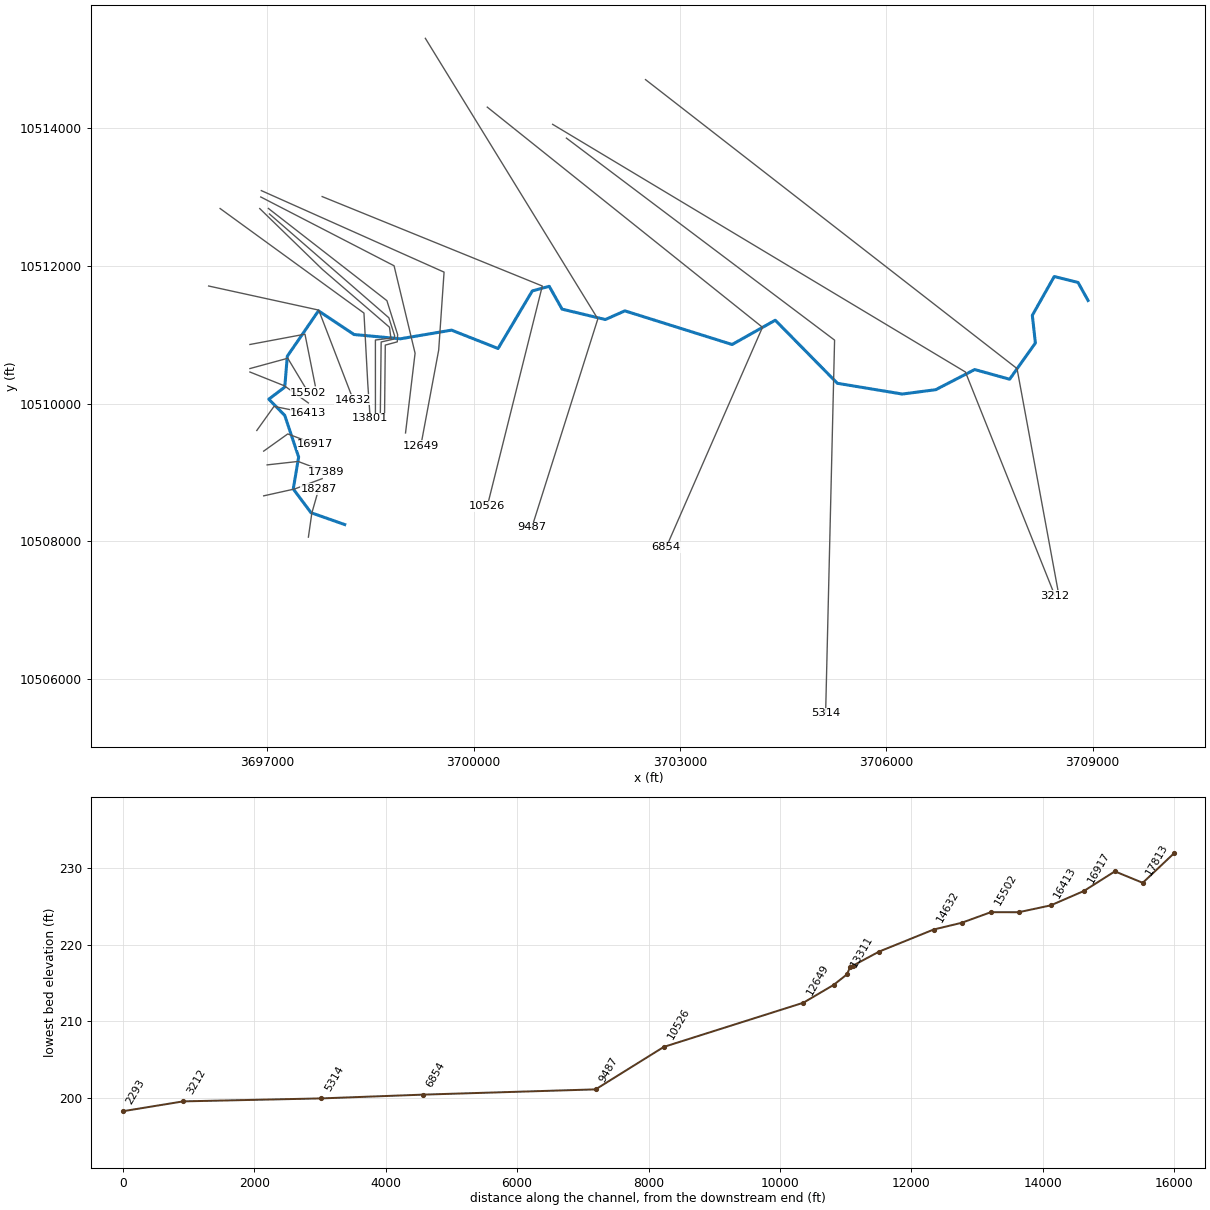
--- UNT 194 IN UKCR.prj (project) ---

Proj Title=UNT 194 IN UKCR Base Level Engineering
Current Plan=p01
Default Exp/Contr=0.3,0.1
English Units
Geom File=g01
Flow File=f01
Plan File=p01
Y Axis Title=Elevation
X Axis Title(PF)=Main Channel Distance
X Axis Title(XS)=Station
BEGIN DESCRIPTION:
UNT 194 IN UKCR
END DESCRIPTION:
DSS Export Rating Curves= 0
DSS Export Rating Curve Sorted= 0
DSS Export Volume Flow Curves= 0
DXF OffsetX= 0
DXF OffsetY= 0
DXF ScaleX= 1
DXF ScaleY= 10

--- UNT 194 IN UKCR.p01 (plan) ---

Plan Title=Multiple Run
Short Identifier=Multiple
Geom File=g01
Flow File=f01
Subcritical Flow
K Sum by GR= 0
Std Step Tol= 0.01
Critical Tol= 0.01
Num of Std Step Trials= 20
Max Error Tol= 0.3
Flow Tol Ratio= 0.001
Split Flow NTrial= 30
Split Flow Tol= 0.02
Split Flow Ratio= 0.02
Log Output Level= 0
Friction Slope Method= 1
Unsteady Friction Slope Method= 2
Unsteady Bridges Friction Slope Method= 1
Parabolic Critical Depth
Global Vel Dist=  1 , 1 , 1
Global Log Level= 0
CheckData=True
Encroach Param= -1, 0, 0, 0
BEGIN DESCRIPTION:
Multiple Run
END DESCRIPTION:

--- UNT 194 IN UKCR.f01 (steady flow) ---

Flow Title=Multiple
Program Version=4.10
Number of Profiles= 7
Profile Names=10-year,25-year,50-year,1pct_min,100-year,1pct_plu,500-year
River Rch & RM=UNT 194 IN UKCR,Reach-1         ,18287
     666     921    1136    1031    1394    1885    2108
River Rch & RM=UNT 194 IN UKCR,Reach-1         ,17813
    1327    1890    2376    2191    2963    4007    4629
River Rch & RM=UNT 194 IN UKCR,Reach-1         ,6854
    1722    2475    3131    2902    3924    5307    6196
River Rch & RM=UNT 194 IN UKCR,Reach-1         ,5314
    1712    2448    3085    2847    3850    5207    6028
Boundary for River Rch & Prof#=UNT 194 IN UKCR,Reach-1         , 1
Up Type= 0
Dn Type= 3
Dn Slope=0.005
Boundary for River Rch & Prof#=UNT 194 IN UKCR,Reach-1         , 2
Up Type= 0
Dn Type= 3
Dn Slope=0.005
Boundary for River Rch & Prof#=UNT 194 IN UKCR,Reach-1         , 3
Up Type= 0
Dn Type= 3
Dn Slope=0.005
Boundary for River Rch & Prof#=UNT 194 IN UKCR,Reach-1         , 4
Up Type= 0
Dn Type= 3
Dn Slope=0.005
Boundary for River Rch & Prof#=UNT 194 IN UKCR,Reach-1         , 5
Up Type= 0
Dn Type= 3
Dn Slope=0.005
Boundary for River Rch & Prof#=UNT 194 IN UKCR,Reach-1         , 6
Up Type= 0
Dn Type= 3
Dn Slope=0.005
Boundary for River Rch & Prof#=UNT 194 IN UKCR,Reach-1         , 7
Up Type= 0
Dn Type= 3
Dn Slope=0.005
DSS Import GetInterval= 0
DSS Import GetPeak= 0
DSS Import FillOption= 0

--- UNT 194 IN UKCR.g01 (geometry) ---

Geom Title=Existing Conditions
Program Version=4.10

River Reach=UNT 194 IN UKCR ,Reach-1
Reach XY= 30
        3698127.       10508243.      3697637.41     10508415.34
      3697379.75       10508760.        3697458.       10509225.
      3697256.25       10509829.        3697024.       10510065.
      3697256.25       10510241.      3697292.75       10510689.
      3697745.75       10511349.      3698264.25       10511005.
      3698937.25       10510943.      3699680.25       10511069.
      3700356.75       10510802.        3700854.       10511639.
        3701100.       10511706.      3701286.75       10511374.
      3701915.75       10511223.       3702199.5       10511349.
       3703758.5       10510860.      3704385.25       10511213.
       3705288.5       10510296.       3706231.5       10510140.
        3706718.       10510203.      3707284.75       10510496.
        3707792.       10510355.       3708166.5       10510882.
        3708122.       10511284.       3708440.5       10511848.
      3708786.25       10511762.      3708932.25       10511500.

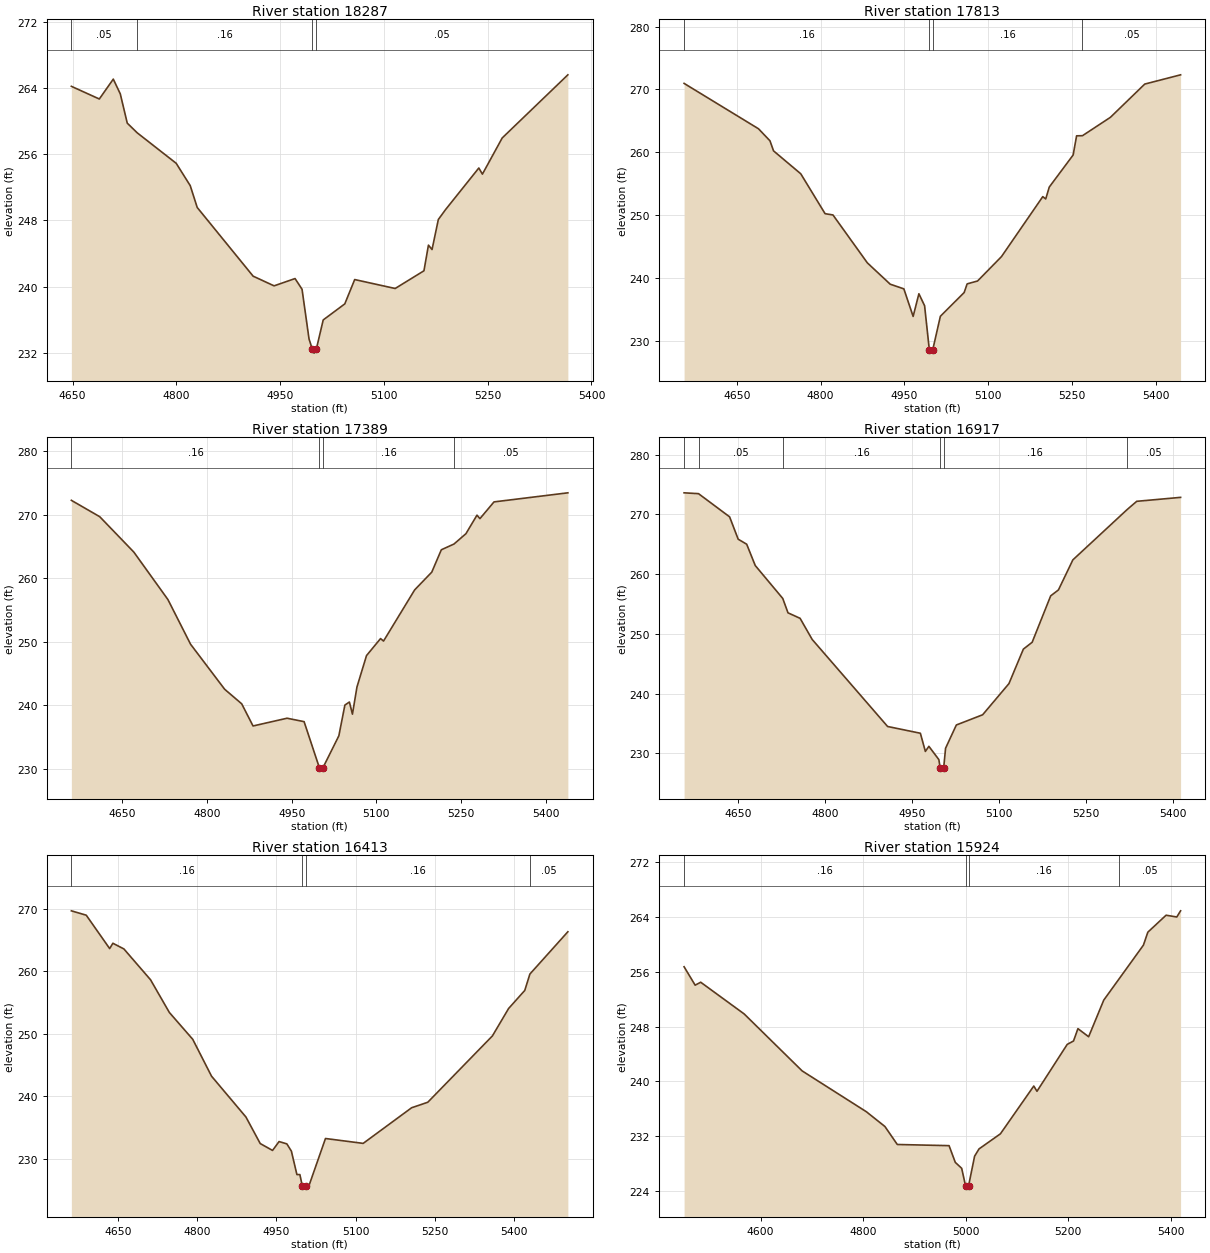
Type RM Length L Ch R = 1 ,18287   ,474,474,474
BEGIN DESCRIPTION:
UNT 194 IN UKCR 16.0
END DESCRIPTION:
XS GIS Cut Line= 3
      3697599.61     10508060.16      3697649.61     10508410.19
      3697749.61      10508760.2
#Sta/Elev= 30
  4648.3  264.21  4688.7  262.68  4708.9  265.08    4719   263.3  4729.1  259.76
  4743.5  258.59  4799.8  254.91  4820.1  252.21  4830.2  249.57    4911  241.27
  4941.3   240.1  4971.6  240.98  4981.7  239.69  4991.8  233.69  4996.4  232.47
  4999.1  231.97  5002.4  232.47  5012.3  235.98  5043.5  237.92  5057.8  240.86
  5116.3  239.78  5157.9  241.92  5164.4  245.02  5169.6  244.49  5178.7  248.12
  5189.1  249.31  5237.2  254.34  5242.4   253.6    5271  257.97  5365.9   265.6
#Mann= 4 ,-1 , 0
  4648.3     .05       0  4743.5     .16       0  4996.4     .07       0
  5002.4     .05       0
Bank Sta=4996.4,5002.4
XS Rating Curve= 0 ,0
Exp/Cntr=0.3,0.1

Type RM Length L Ch R = 1 ,17813   ,424,424,424
BEGIN DESCRIPTION:
UNT 194 IN UKCR 15.0
END DESCRIPTION:
XS GIS Cut Line= 3
      3696949.66      10508660.2      3697399.61     10508760.19
      3697799.58     10508910.18
#Sta/Elev= 30
  4555.8  270.97  4688.9  263.76  4709.4  261.85  4715.8  260.25  4764.5  256.61
    4808  250.27  4822.1  250.07  4883.6  242.46  4924.5  239.07  4948.9  238.33
  4965.5  233.95  4975.8  237.55    4986  235.65  4994.5  228.62  4997.3  228.12
  5000.5  228.62  5014.2  233.97  5056.8  237.75  5062.1  239.12  5080.8  239.58
  5123.5  243.45  5197.4  252.98  5202.7  252.61    5209   254.5  5251.7  259.59
  5257.9  262.64  5268.4  262.66  5318.4  265.58  5379.8  270.86  5443.9  272.33
#Mann= 4 ,-1 , 0
  4555.8     .16       0  4994.5     .07       0  5000.5     .16       0
  5268.4     .05       0
Bank Sta=4994.5,5000.5
XS Rating Curve= 0 ,0
Exp/Cntr=0.3,0.1

Type RM Length L Ch R = 1 ,17389   ,472,472,472
BEGIN DESCRIPTION:
UNT 194 IN UKCR 14.0
END DESCRIPTION:
XS GIS Cut Line= 3
       3696999.6     10509110.19      3697449.61     10509160.19
      3697849.63     10509010.18
#Sta/Elev= 30
  4559.5  272.26  4609.8  269.68  4670.2  264.11  4730.6  256.64  4770.8   249.6
  4831.2  242.51  4861.4  240.22  4881.5  236.73  4941.8  237.95    4972  237.41
  4999.2  230.12    5002  229.62  5005.2  230.12  5033.6  235.18  5044.3  240.02
  5052.3   240.5  5057.7  238.59  5065.7  242.87  5082.6  247.81  5107.5  250.49
  5112.8   250.1    5168  258.16  5198.3  260.95  5215.2  264.47  5237.7  265.38
  5258.8     267  5278.4  269.92  5283.7  269.38  5308.6  272.01  5439.5  273.44
#Mann= 4 ,-1 , 0
  4559.5     .16       0  4999.2     .07       0  5005.2     .16       0
  5237.7     .05       0
Bank Sta=4999.2,5005.2
XS Rating Curve= 0 ,0
Exp/Cntr=0.3,0.1

Type RM Length L Ch R = 1 ,16917   ,504,504,504
BEGIN DESCRIPTION:
UNT 194 IN UKCR 13.0
END DESCRIPTION:
XS GIS Cut Line= 3
      3696949.63      10509310.2      3697299.61     10509560.19
      3697699.62     10509410.19
#Sta/Elev= 30
  4556.4  273.62  4581.3  273.48    4635   269.6  4649.8  265.86  4664.5  265.02
  4679.3  261.45  4726.8  255.94  4735.8  253.54  4756.7  252.62  4777.6  249.08
  4907.8  234.52  4964.4  233.39    4973  230.35  4979.1   231.2  4996.3  228.98
  4998.6  227.55  5001.4  227.05  5004.6  227.55  5007.9  230.88  5026.5  234.77
  5071.9  236.48  5117.3  241.69  5142.2  247.46  5157.4  248.61  5189.4  256.38
  5202.8  257.37  5227.7   262.4  5321.3  270.81    5338   272.2  5413.7  272.86
#Mann= 6 ,-1 , 0
  4556.4     .16       0  4581.3     .05       0  4726.8     .16       0
  4998.6     .07       0  5004.6     .16       0  5321.3     .05       0
Bank Sta=4998.6,5004.6
XS Rating Curve= 0 ,0
Exp/Cntr=0.3,0.1

Type RM Length L Ch R = 1 ,16413   ,489,489,489
BEGIN DESCRIPTION:
UNT 194 IN UKCR 12.0
END DESCRIPTION:
XS GIS Cut Line= 3
      3696849.63     10509610.22      3697099.61     10509960.19
      3697599.63     10509860.19
#Sta/Elev= 30
  4561.9   269.7  4590.1     269  4634.4  263.66  4640.5  264.51  4661.4   263.6
  4711.8  258.67  4747.4  253.44  4791.7  249.14  4827.3  243.24  4892.4  236.71
  4919.5  232.46  4942.8  231.36  4955.1  232.78  4969.9  232.41  4978.5  231.24
  4988.9   227.5  4994.5   227.5  4999.2  225.67  5001.9  225.17  5005.2  225.67
  5012.4  225.88    5043  233.27  5114.4  232.49  5206.1  238.19  5236.7  239.07
  5359.1  249.69  5389.7  254.07  5420.3  256.96    5430  259.58  5501.9  266.35
#Mann= 4 ,-1 , 0
  4561.9     .16       0  4999.2     .07       0  5005.2     .16       0
    5430     .05       0
Bank Sta=4999.2,5005.2
XS Rating Curve= 0 ,0
Exp/Cntr=0.3,0.1

Type RM Length L Ch R = 1 ,15924   ,422,422,422
BEGIN DESCRIPTION:
UNT 194 IN UKCR 11.0
END DESCRIPTION:
XS GIS Cut Line= 3
      3696749.57     10510460.21      3697249.61     10510260.19
      3697599.63     10510010.18
#Sta/Elev= 30
  4450.9  256.75  4472.5  254.06  4483.3  254.49  4568.1  249.86  4681.2  241.54
  4806.4  235.58  4842.7  233.42  4866.9  230.79  4967.9  230.62    4980  228.18
  4992.5  227.31    5000  224.77  5002.7  224.27    5006  224.77  5017.7  229.08
  5026.3  230.14  5068.1  232.35  5133.2  239.33  5139.4  238.56  5198.4  245.41
  5210.7  245.91  5219.3  247.71  5240.2  246.53  5269.7  251.88  5299.8     255
  5347.1  259.91  5355.7   261.8  5391.3  264.28  5412.2  264.02  5419.6  264.92
#Mann= 4 ,-1 , 0
  4450.9     .16       0    5000     .07       0    5006     .16       0
  5299.8     .05       0
Bank Sta=5000,5006
XS Rating Curve= 0 ,0
Exp/Cntr=0.3,0.1

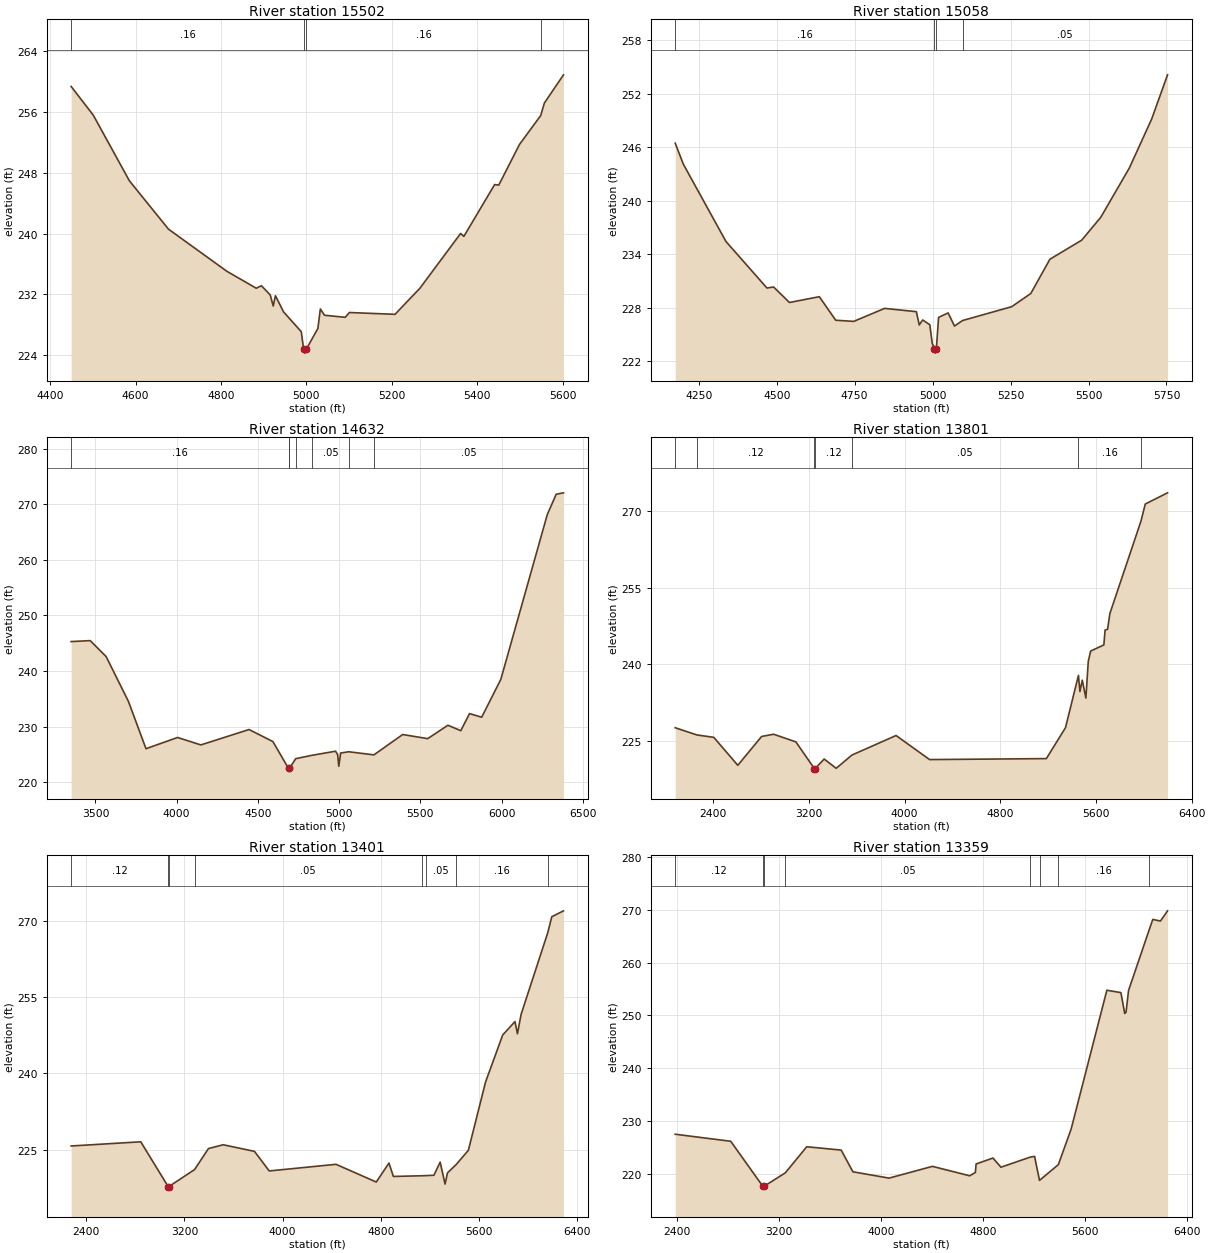
Type RM Length L Ch R = 1 ,15502   ,444,444,444
BEGIN DESCRIPTION:
UNT 194 IN UKCR 10.0
END DESCRIPTION:
XS GIS Cut Line= 3
       3696749.6     10510510.19      3697299.61     10510660.19
      3697599.62     10510160.18
#Sta/Elev= 30
    4449  259.34  4500.8  255.57  4585.5  246.93    4677  240.58  4813.5  235.05
  4882.6  232.81  4894.7  233.14  4915.4  231.92  4922.3  230.47  4927.5  231.83
  4946.5   229.7    4988   227.1  4993.6  224.78  4996.4  224.28  4999.6  224.78
  5026.9  227.52  5032.7  230.09  5042.4  229.26    5091  228.99  5100.7  229.62
  5207.6  229.38  5265.9  232.81  5361.2  240.01  5368.9  239.63  5440.9  246.44
  5450.6  246.37  5499.2  251.72  5548.9  255.52  5557.5  257.17  5602.2  260.87
#Mann= 4 ,-1 , 0
    4449     .16       0  4993.6     .07       0  4999.6     .16       0
  5548.9     .05       0
Bank Sta=4993.6,4999.6
XS Rating Curve= 0 ,0
Exp/Cntr=0.3,0.1

Type RM Length L Ch R = 1 ,15058   ,426,426,426
BEGIN DESCRIPTION:
UNT 194 IN UKCR 9.0
END DESCRIPTION:
XS GIS Cut Line= 3
      3696749.56     10510860.18      3697549.61     10511010.19
       3697699.6     10510260.23
#Sta/Elev= 30
  4174.6  246.44  4200.9  244.07  4337.4  235.41  4468.9  230.19  4490.1  230.31
  4540.9  228.57  4636.7  229.22  4689.3  226.58    4747  226.45  4846.2  227.91
  4947.9  227.54  4957.2  226.05  4968.2  226.61  4991.1  226.07  4998.8  223.99
    5006  223.39  5008.7  222.89    5012  223.39  5019.2   226.9  5049.8   227.4
  5070.2  225.93  5096.3  226.55  5253.7   228.1  5314.9  229.58  5376.1  233.42
  5478.1  235.56  5539.3  238.13  5631.1  243.67  5702.5  249.15  5753.4  254.11
#Mann= 4 ,-1 , 0
  4174.6     .16       0    5006     .07       0    5012     .16       0
  5096.3     .05       0
Bank Sta=5006,5012
XS Rating Curve= 0 ,0
Exp/Cntr=0.3,0.1

Type RM Length L Ch R = 1 ,14632   ,831,831,831
BEGIN DESCRIPTION:
UNT 194 IN UKCR 8.0
END DESCRIPTION:
XS GIS Cut Line= 3
      3696149.57      10511710.2      3697749.61     10511360.19
       3698249.6      10510060.2
#Sta/Elev= 30
  3350.5   245.3  3467.9  245.47  3565.9   242.6  3702.6  234.58  3811.2  226.04
  4005.7  228.06    4149  226.72  4445.5  229.49  4592.4  227.32  4688.5  222.51
  4691.3  222.01  4694.5  222.51  4732.9  224.25  4834.2  224.86  4978.1  225.59
  4991.1  224.98    4998  222.88  5009.8  225.27  5059.6  225.49  5214.2  224.93
  5391.2  228.59  5545.5  227.85  5669.8  230.26  5749.1  229.28  5802.7  232.35
  5877.7   231.7  5995.5  238.51  6281.6  268.14  6336.2  271.78  6381.2  272.04
#Mann= 7 ,-1 , 0
  3350.5     .16       0  4688.5     .03       0  4694.5     .16       0
  4732.9     .12       0  4834.2     .05       0  5059.6     .12       0
  5214.2     .05       0
Bank Sta=4688.5,4694.5
XS Rating Curve= 0 ,0
Exp/Cntr=0.3,0.1

Type RM Length L Ch R = 1 ,13801   ,400,400,400
BEGIN DESCRIPTION:
UNT 194 IN UKCR 7.0
END DESCRIPTION:
XS GIS Cut Line= 4
      3696316.32     10512836.55       3698407.2     10511316.93
      3698462.75     10510289.15      3698497.48      10509789.1
#Sta/Elev= 30
  2083.1  227.61  2264.2   226.2  2405.5  225.73  2606.4  220.26  2805.1   225.9
  2905.6  226.34  3091.8  224.84  3246.2  219.62    3249  219.12  3252.2  219.62
  3328.3  221.48  3428.8  219.67  3559.7  222.26  3929.1  226.09  4209.4  221.38
  5185.4  221.57  5345.6  227.63  5453.7  237.86  5465.8   234.7  5485.8  236.91
  5515.8  233.42  5535.9  240.61  5555.9  242.62  5666.1  243.82  5676.1  246.71
  5697.1  246.87  5716.2  249.94  5976.2  268.04  6012.3  271.39  6198.4  273.58
#Mann= 7 ,-1 , 0
  2083.1     .16       0  2264.2     .12       0  3246.2     .03       0
  3252.2     .12       0  3559.7     .05       0  5453.7     .16       0
  5976.2     .05       0
Bank Sta=3246.2,3252.2
XS Rating Curve= 0 ,0
Exp/Cntr=0.3,0.1

Type RM Length L Ch R = 1 ,13401   ,42,42,42
BEGIN DESCRIPTION:
Mapping XS 7273fad3
END DESCRIPTION:
XS GIS Cut Line= 6
      3696892.55     10512835.79      3697804.03     10511950.35
      3698777.99     10511111.29      3698798.82     10510953.74
      3698573.56     10510925.09      3698573.99     10509874.79
#Sta/Elev= 30
  2276.4  225.74  2843.9  226.56  3067.3  217.77    3070  217.27  3073.3  217.77
  3282.7  221.11  3395.6  225.23  3515.8  225.98  3770.9  224.68  3891.2  220.84
  4435.7  222.14  4763.8  218.66  4867.3  222.39  4903.2  219.76  5133.9  219.89
  5167.5  219.92  5233.5  219.99  5284.6  222.57  5324.6  218.26  5344.6  220.47
  5412.7  222.03  5514.6  224.89  5654.6  238.29  5794.6  247.53  5894.6  250.16
  5914.6  247.77  5944.6  251.59  6161.8   267.6  6194.6  270.74    6290   271.9
#Mann= 8 ,-1 , 0
  2276.4     .12       0  3067.3     .03       0  3073.3     .12       0
  3282.7     .05       0  5133.9     .07       0  5167.5     .05       0
  5412.7     .16       0  6161.8     .05       0
Bank Sta=3067.3,3073.3
XS Rating Curve= 0 ,0
Exp/Cntr=0.3,0.1

Type RM Length L Ch R = 1 ,13359   ,48,48,48
BEGIN DESCRIPTION:
Mapping XS 235fa6d5
END DESCRIPTION:
XS GIS Cut Line= 6
      3697032.95     10512757.67      3698768.98     10511248.42
      3698853.62     10510984.75      3698842.77     10510939.18
      3698657.22     10510896.86      3698645.18     10509854.56
#Sta/Elev= 30
  2388.4  227.47  2823.7  226.13  3076.3  217.55    3079  217.05  3082.3  217.55
  3251.1  220.13  3419.4  225.09  3689.2  224.46  3781.4  220.34  4064.5  219.14
  4404.6  221.37  4697.1  219.58  4741.4  220.22    4747  221.82  4879.3  222.95
  4941.8  221.21  5172.2  223.13  5205.3  223.27    5244  218.71  5391.8   221.7
    5492  228.45    5772  254.79    5882  254.34    5912  250.38  5922.1   250.6
  5942.1  254.75  6105.5  266.38  6132.1  268.23  6192.1  267.92  6247.7  269.86
#Mann= 8 ,-1 , 0
  2388.4     .12       0  3076.3     .03       0  3082.3     .12       0
  3251.1     .05       0  5172.2     .07       0    5244     .05       0
  5391.8     .16       0  6105.5     .05       0
Bank Sta=3076.3,3082.3
XS Rating Curve= 0 ,0
Exp/Cntr=0.3,0.1

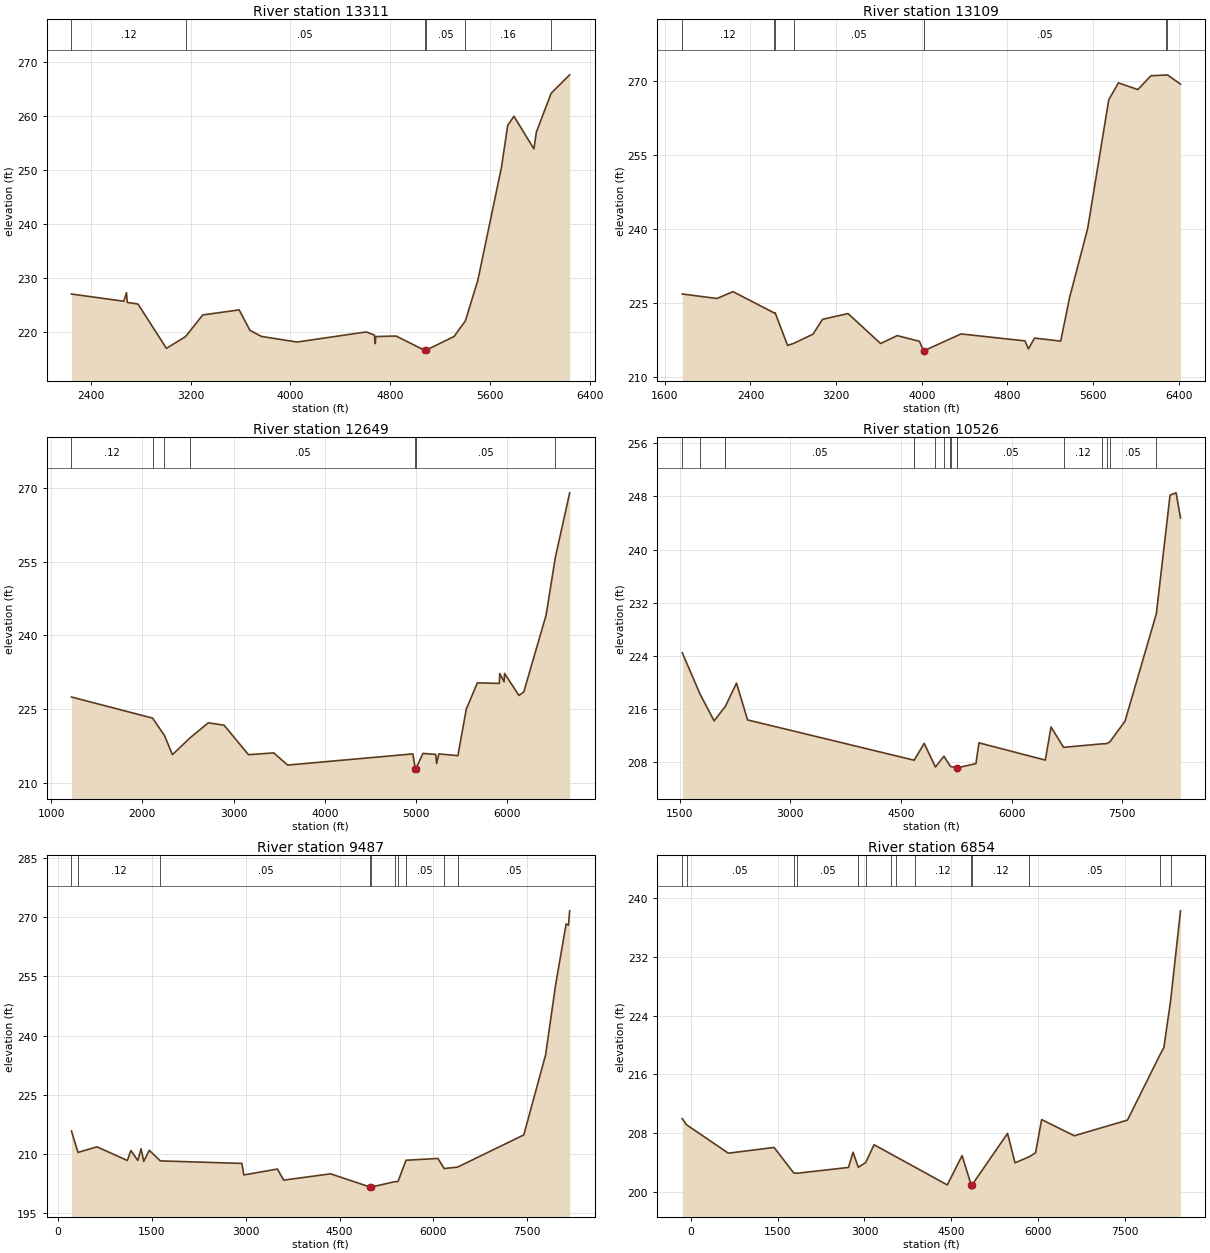
Type RM Length L Ch R = 1 ,13311   ,202,202,202
BEGIN DESCRIPTION:
Mapping XS 02409733
END DESCRIPTION:
XS GIS Cut Line= 6
      3697018.28     10512837.79      3698740.53     10511497.49
      3698896.78      10511002.7      3698891.57     10510898.53
      3698717.09     10510851.65       3698706.7      10509843.2
#Sta/Elev= 30
  2243.8  227.05  2663.6  225.72  2685.2   227.3  2691.5   225.5  2777.7   225.2
  3005.8  217.01  3159.4  219.19  3297.2  223.19  3589.1  224.12  3675.9  220.34
  3767.3  219.22  4053.3  218.18  4609.4  220.05  4674.1  219.46  4680.5  217.89
  4685.7  219.19  4847.9  219.29  5078.7  216.63  5081.5  216.13  5084.7  216.63
  5313.4  219.21    5404   222.1  5503.4  229.56  5693.4  250.48  5743.4  258.22
  5793.4   259.9  5953.4  253.88  5973.4  256.98    6092  264.16  6240.4  267.56
#Mann= 6 ,-1 , 0
  2243.8     .12       0  3159.4     .05       0  5078.7     .03       0
  5084.7     .05       0    5404     .16       0    6092     .05       0
Bank Sta=5078.7,5084.7
XS Rating Curve= 0 ,0
Exp/Cntr=0.3,0.1

Type RM Length L Ch R = 1 ,13109   ,460,460,460
BEGIN DESCRIPTION:
Mapping XS ffadeed4
END DESCRIPTION:
XS GIS Cut Line= 4
      3696907.24     10513004.41       3698844.7     10512004.43
      3699150.25      10510733.6      3699011.44     10509574.53
#Sta/Elev= 30
  1763.2  226.74  2087.6  225.83    2237  227.22    2623  222.89  2631.1  222.93
  2746.6  216.33  2803.7  216.73  2984.7  218.61  3073.3   221.6  3311.4  222.78
  3615.9  216.71    3771  218.31  3978.7  217.16  4016.9  215.26  4019.6  214.76
  4022.9  215.26  4367.6  218.65  4965.3  217.24  4996.9  215.62  5054.4  217.81
  5298.7  217.19    5381  225.96  5550.7  240.02  5747.5  266.08  5838.1  269.52
  6019.4  268.16  6142.1  270.97  6281.6  271.11  6295.7  271.15  6417.9  269.26
#Mann= 8 ,-1 , 0
  1763.2     .12       0    2623     .16       0  2631.1     .12       0
  2803.7     .05       0  4016.9     .03       0  4022.9     .05       0
  6281.6     .16       0  6295.7     .05       0
Bank Sta=4016.9,4022.9
XS Rating Curve= 0 ,0
Exp/Cntr=0.3,0.1

Type RM Length L Ch R = 1 ,12649   ,2123,2123,2123
BEGIN DESCRIPTION:
Mapping XS 51b59f9b
END DESCRIPTION:
XS GIS Cut Line= 4
      3696915.28     10513096.96      3699571.56     10511912.05
      3699493.43     10510779.24      3699233.02     10509386.05
#Sta/Elev= 30
  1222.7  227.49  2112.3   223.2  2242.4  219.67  2329.8  215.77  2524.7  219.22
  2723.2  222.25  2896.8  221.75  3163.2  215.77  3440.5  216.13  3592.6  213.66
  4965.1  215.93  4992.2  212.93  4994.9  212.43  4998.2  212.93  5075.4  216.03
  5215.7  215.82  5225.7  213.97  5250.2  215.93  5459.1  215.58  5550.7  225.03
  5672.7  230.37  5912.7  230.25  5917.7  232.27  5965.3  230.58  5970.4  232.29
  6128.3  227.81    6181  228.52  6425.6  244.12    6527  255.84  6684.1  268.98
#Mann= 7 ,-1 , 0
  1222.7     .12       0  2112.3     .16       0  2242.4     .12       0
  2524.7     .05       0  4992.2     .03       0  4998.2     .05       0
    6527     .16       0
Bank Sta=4992.2,4998.2
XS Rating Curve= 0 ,0
Exp/Cntr=0.3,0.1

Type RM Length L Ch R = 1 ,10526   ,1039,1039,1039
BEGIN DESCRIPTION:
UNT 194 IN UKCR 6.0
END DESCRIPTION:
XS GIS Cut Line= 3
      3697799.58      10513010.2      3700999.61     10511710.19
      3700199.61     10508510.19
#Sta/Elev= 30
  1536.6  224.47  1778.7  218.22  1968.4  214.21  2111.9  216.29  2116.2   216.3
  2271.6   219.9  2421.5  214.36    4680  208.29  4681.7  208.34  4815.2  210.83
  4967.8  207.27  5082.9   208.9  5171.4  207.35  5185.1  207.32  5258.2  207.15
  5260.9  206.65  5264.2  207.15  5516.3  207.78  5557.5  210.91  6456.9  208.31
  6534.2   213.3  6704.1  210.23  7227.5  210.76  7289.4  210.79  7331.2  211.05
  7536.6  214.16  7961.7  230.35  8147.4   248.2  8229.8  248.55  8289.1  244.77
#Mann= 17 ,-1 , 0
  1536.6     .16       0  1778.7     .12       0  2111.9     .07       0
  2116.2     .05       0    4680     .07       0  4681.7     .05       0
  4967.8     .07       0  5082.9     .05       0  5171.4     .07       0
  5185.1     .05       0  5258.2     .07       0  5264.2     .05       0
  6704.1     .12       0  7227.5     .07       0  7289.4     .12       0
  7331.2     .05       0  7961.7     .16       0
Bank Sta=5258.2,5264.2
XS Rating Curve= 0 ,0
Exp/Cntr=0.3,0.1

Type RM Length L Ch R = 1 ,9487    ,2633,2633,2633
BEGIN DESCRIPTION:
UNT 194 IN UKCR 5.0
END DESCRIPTION:
XS GIS Cut Line= 3
       3699299.6     10515310.21       3701806.5       10511232.
      3700847.58     10508201.07
#Sta/Elev= 30
   212.9  215.83     318   210.4   620.7  211.81  1105.9  208.36  1163.9  210.88
    1274  208.35  1326.1  211.32  1368.7  208.12  1457.2  210.93    1634  208.25
  2938.1  207.61  2968.9  204.68  3506.2  206.18  3606.8  203.37  4356.5  204.97
  4993.3  201.59  4996.1  201.09  4999.3  201.59  5386.7  202.99  5434.1     203
  5562.3  208.41  6072.1  208.87  6172.2  206.31    6387  206.67  7445.7  214.83
  7794.1  235.12  7955.6  252.99  8122.4  268.33    8160  267.99    8179  271.64
#Mann= 10 ,-1 , 0
   212.9     .16       0     318     .12       0    1634     .05       0
  4993.3     .03       0  4999.3     .05       0  5386.7     .12       0
  5434.1     .07       0  5562.3     .05       0  6172.2     .12       0
    6387     .05       0
Bank Sta=4993.3,4999.3
XS Rating Curve= 0 ,0
Exp/Cntr=0.3,0.1

Type RM Length L Ch R = 1 ,6854    ,1540,1540,1540
BEGIN DESCRIPTION:
UNT 194 IN UKCR 4.0
END DESCRIPTION:
XS GIS Cut Line= 3
      3700199.58     10514310.21      3704199.61     10511110.19
       3702799.6     10507910.17
#Sta/Elev= 30
  -150.7     210   -75.6  209.15   645.7  205.29  1436.5  206.07  1776.5   202.6
  1833.5  202.56  2723.5  203.35    2802  205.42  2892.4  203.38  3020.6  204.01
  3165.4  206.44  3450.5  205.21  3552.5  204.77  3870.4   203.4  4431.6  200.97
  4687.7  204.96    4848   200.9  4850.7   200.4    4854   200.9  5473.9  207.98
  5603.7  203.98  5851.3  204.81  5958.5  205.34  6063.3  209.86  6628.2  207.66
  7547.8  209.79  8102.1  218.55  8176.6  219.64  8293.7  226.02  8464.7  238.26
#Mann= 14 ,-1 , 0
  -150.7     .12       0   -75.6     .05       0  1776.5     .07       0
  1833.5     .05       0  2892.4     .07       0  3020.6     .05       0
  3450.5     .07       0  3552.5     .05       0  3870.4     .12       0
    4848     .07       0    4854     .12       0  5851.3     .05       0
  8102.1     .12       0  8293.7     .16       0
Bank Sta=4848,4854
XS Rating Curve= 0 ,0
Exp/Cntr=0.3,0.1

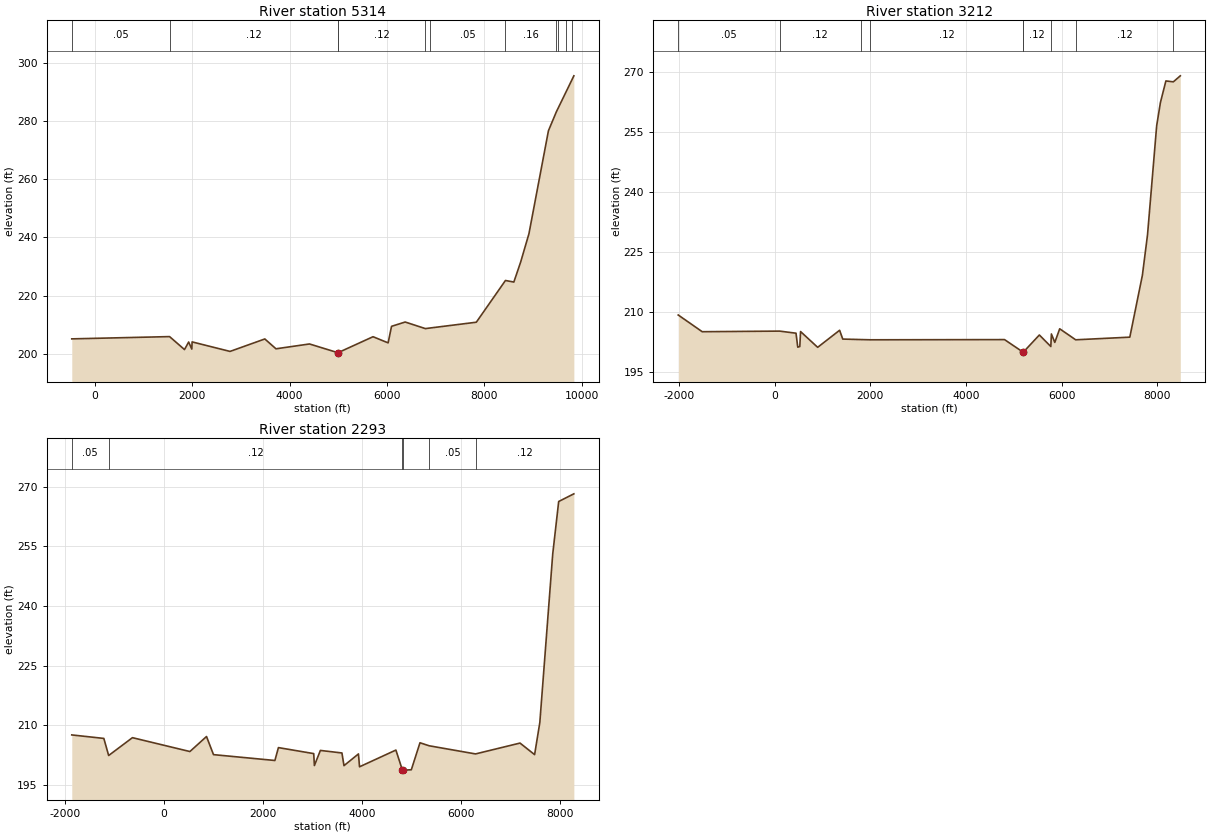
Type RM Length L Ch R = 1 ,5314    ,2102,2102,2102
BEGIN DESCRIPTION:
UNT 194 IN UKCR 3.0
END DESCRIPTION:
XS GIS Cut Line= 3
      3701349.63     10513860.17      3705247.79     10510923.75
      3705117.58      10505498.4
#Sta/Elev= 30
  -470.4  205.15  1537.1  205.93  1843.8  201.48  1929.1  204.07  1993.7  201.64
  1999.9  204.11  2778.6  200.84  3492.8  205.12  3721.8  201.74    4410   203.4
  4990.7  200.41  4993.5  199.91  4996.7  200.41  5713.9  205.89    6024  203.78
    6094  209.46  6374.1  210.94  6788.5  208.68  6886.7  208.89  7834.5  210.87
  8432.7  225.21  8604.8  224.67  8744.8  231.55  8914.8  241.27    9315  276.65
  9477.7  283.16  9502.8  284.02  9672.5  289.86  9792.8     294  9836.9  295.52
#Mann= 11 ,-1 , 0
  -470.4     .05       0  1537.1     .12       0  4990.7     .07       0
  4996.7     .12       0  6788.5     .16       0  6886.7     .05       0
  8432.7     .16       0  9477.7     .12       0  9502.8     .16       0
  9672.5     .12       0  9792.8     .16       0
Bank Sta=4990.7,4996.7
XS Rating Curve= 0 ,0
Exp/Cntr=0.3,0.1

Type RM Length L Ch R = 1 ,3212    ,919,919,919
BEGIN DESCRIPTION:
UNT 194 IN UKCR 2.0
END DESCRIPTION:
XS GIS Cut Line= 3
      3701149.59      10514060.2      3707149.61     10510460.19
       3708449.6     10507210.21
#Sta/Elev= 30
 -2016.1   209.3 -1514.6  205.12   102.7  205.27   446.5  204.75   483.5  201.26
   526.2  201.42   541.8  205.16   899.4  201.22  1358.1  205.48  1424.2  203.28
  1797.7  203.16  1999.1   203.1  4806.1  203.15  5193.5  200.02  5196.2  199.52
  5199.5  200.02  5534.4   204.3    5774  201.42  5786.2  204.56  5857.5  202.45
  5959.8  205.85  6293.9   203.1  7425.9  203.76  7688.5  219.22  7796.2  229.37
  7987.3  256.59  8065.4  262.37  8179.9  267.77  8335.4  267.55  8481.4  269.05
#Mann= 9 ,-1 , 0
 -2016.1     .05       0   102.7     .12       0  1797.7     .07       0
  1999.1     .12       0  5193.5     .07       0  5199.5     .12       0
  5786.2     .05       0  6293.9     .12       0  8335.4     .16       0
Bank Sta=5193.5,5199.5
XS Rating Curve= 0 ,0
Exp/Cntr=0.3,0.1

Type RM Length L Ch R = 1 ,2293    ,0,0,0
BEGIN DESCRIPTION:
UNT 194 IN UKCR 1.0
END DESCRIPTION:
XS GIS Cut Line= 3
       3702499.6     10514710.19      3707899.61     10510510.19
      3708499.61     10507260.17
#Sta/Elev= 30
 -1859.7  207.59 -1211.8  206.71 -1114.3  202.41  -633.5   206.9   527.4  203.41
   863.2  207.19  1004.3  202.63  2244.9  201.16  2316.4   204.4  3029.5  202.89
  3043.1  199.89  3164.3  203.69  3599.6  203.05  3641.2  199.86  3933.5  202.81
  3955.2  199.57    4690  203.78  4821.8  198.73  4824.6  198.23  4827.8  198.73
  5001.7  198.82  5176.9  205.62  5361.5  204.86  6299.3  202.81  7198.2  205.54
  7493.1  202.63  7598.8  210.74  7859.2  253.11  7979.7  266.32  8286.3  268.25
#Mann= 6 ,-1 , 0
 -1859.7     .05       0 -1114.3     .12       0  4821.8     .07       0
  4827.8     .12       0  5361.5     .05       0  6299.3     .12       0
Bank Sta=4821.8,4827.8
XS Rating Curve= 0 ,0
Exp/Cntr=0.3,0.1

Chan Stop Cuts=-1
Use User Specified Reach Order=0
Composite Channel Slope=5