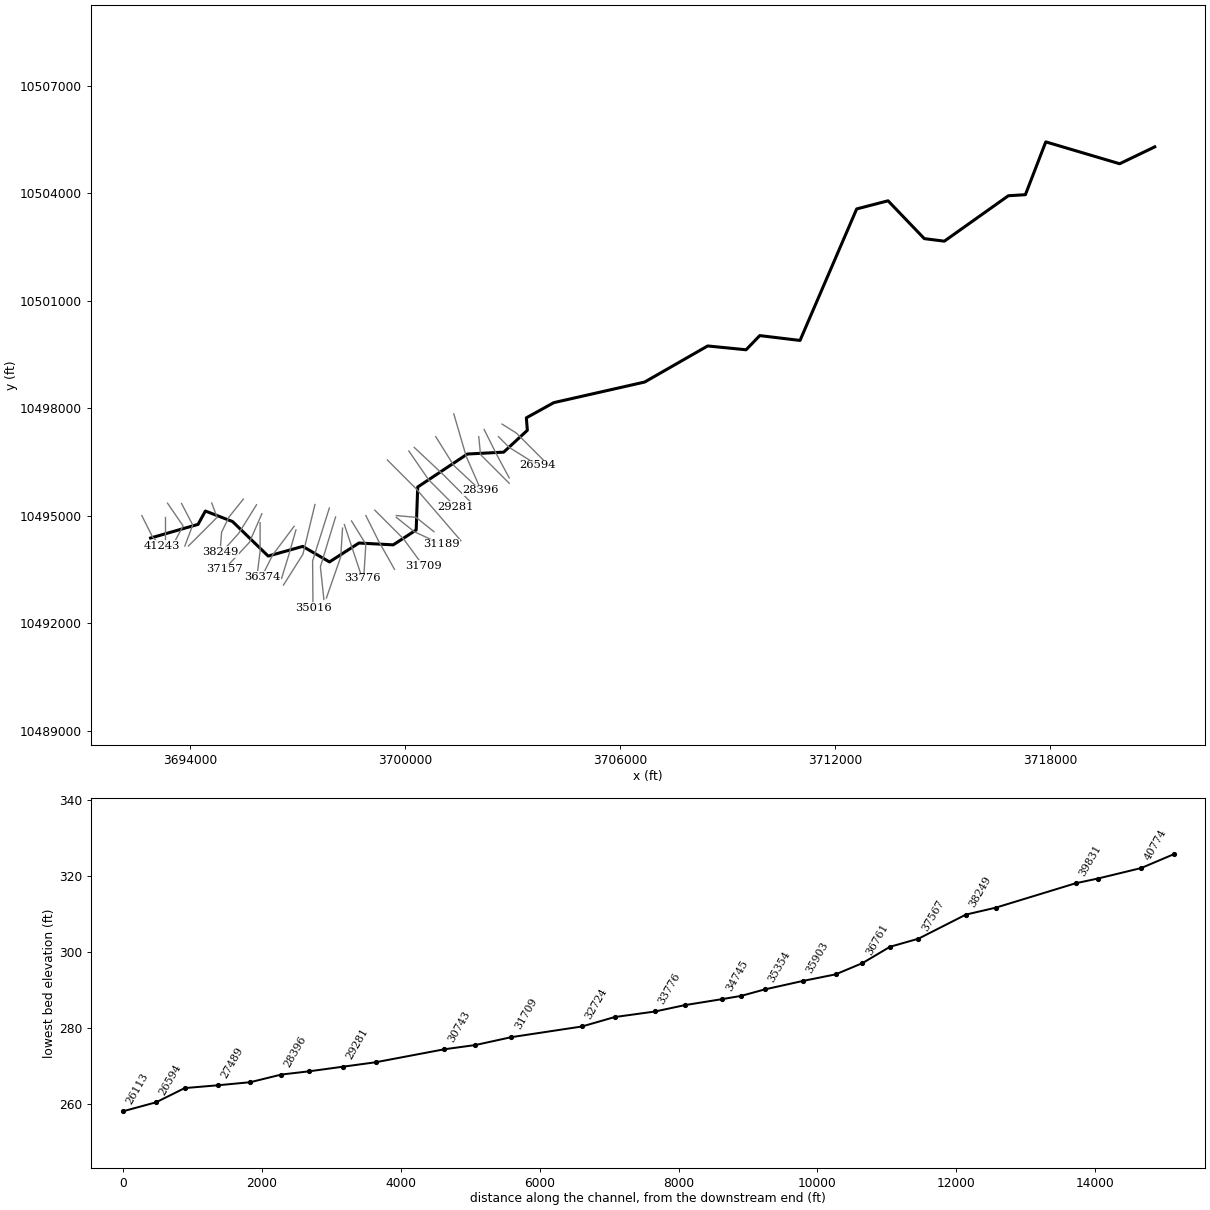
--- UNT 199 IN UKCR.prj (project) ---

Proj Title=UNT 199 IN UKCR Base Level Engineering
Current Plan=p01
Default Exp/Contr=0.3,0.1
English Units
Geom File=g01
Flow File=f01
Plan File=p01
Y Axis Title=Elevation
X Axis Title(PF)=Main Channel Distance
X Axis Title(XS)=Station
BEGIN DESCRIPTION:
UNT 199 IN UKCR
END DESCRIPTION:
DSS Export Rating Curves= 0
DSS Export Rating Curve Sorted= 0
DSS Export Volume Flow Curves= 0
DXF OffsetX= 0
DXF OffsetY= 0
DXF ScaleX= 1
DXF ScaleY= 10

--- UNT 199 IN UKCR.p01 (plan) ---

Plan Title=Multiple Run
Short Identifier=Multiple
Geom File=g01
Flow File=f01
Subcritical Flow
K Sum by GR= 0
Std Step Tol= 0.01
Critical Tol= 0.01
Num of Std Step Trials= 20
Max Error Tol= 0.3
Flow Tol Ratio= 0.001
Split Flow NTrial= 30
Split Flow Tol= 0.02
Split Flow Ratio= 0.02
Log Output Level= 0
Friction Slope Method= 1
Unsteady Friction Slope Method= 2
Unsteady Bridges Friction Slope Method= 1
Parabolic Critical Depth
Global Vel Dist=  1 , 1 , 1
Global Log Level= 0
CheckData=True
Encroach Param= -1, 0, 0, 0
BEGIN DESCRIPTION:
Multiple Run
END DESCRIPTION:

--- UNT 199 IN UKCR.f01 (steady flow) ---

Flow Title=Multiple
Program Version=4.10
Number of Profiles= 7
Profile Names=10-year,25-year,50-year,1pct_min,100-year,1pct_plu,500-year
River Rch & RM=UNT 199 IN UKCR,Reach-1         ,41243
     796    1117    1392    1275    1725    2332    2660
River Rch & RM=UNT 199 IN UKCR,Reach-1         ,38676
    1060    1505    1889    1741    2355    3185    3679
River Rch & RM=UNT 199 IN UKCR,Reach-1         ,34203
    1318    1887    2382    2206    2984    4035    4706
River Rch & RM=UNT 199 IN UKCR,Reach-1         ,31709
    1525    2191    2772    2572    3478    4704    5503
River Rch & RM=UNT 199 IN UKCR,Reach-1         ,26594
    1636    2356    2985    2772    3749    5070    5943
River Rch & RM=UNT 199 IN UKCR,Reach-1         ,25087
    1797    2592    3287    3054    4130    5585    6553
River Rch & RM=UNT 199 IN UKCR,Reach-1         ,20134
    1960    2833    3597    3345    4524    6118    7191
River Rch & RM=UNT 199 IN UKCR,Reach-1         ,16702
    2130    3084    3921    3649    4935    6674    7859
River Rch & RM=UNT 199 IN UKCR,Reach-1         ,11936
    2188    3159    4008    3721    5033    6806    7975
River Rch & RM=UNT 199 IN UKCR,Reach-1         ,2082
    2279    3291    4176    3877    5243    7091    8308
Boundary for River Rch & Prof#=UNT 199 IN UKCR,Reach-1         , 1
Up Type= 0
Dn Type= 3
Dn Slope=0.0036
Boundary for River Rch & Prof#=UNT 199 IN UKCR,Reach-1         , 2
Up Type= 0
Dn Type= 3
Dn Slope=0.0036
Boundary for River Rch & Prof#=UNT 199 IN UKCR,Reach-1         , 3
Up Type= 0
Dn Type= 3
Dn Slope=0.0036
Boundary for River Rch & Prof#=UNT 199 IN UKCR,Reach-1         , 4
Up Type= 0
Dn Type= 3
Dn Slope=0.0036
Boundary for River Rch & Prof#=UNT 199 IN UKCR,Reach-1         , 5
Up Type= 0
Dn Type= 3
Dn Slope=0.0036
Boundary for River Rch & Prof#=UNT 199 IN UKCR,Reach-1         , 6
Up Type= 0
Dn Type= 3
Dn Slope=0.0036
Boundary for River Rch & Prof#=UNT 199 IN UKCR,Reach-1         , 7
Up Type= 0
Dn Type= 3
Dn Slope=0.0036
DSS Import GetInterval= 0
DSS Import GetPeak= 0
DSS Import FillOption= 0

--- UNT 199 IN UKCR.g01 (geometry) ---

Geom Title=Existing Conditions
Program Version=4.10

River Reach=UNT 199 IN UKCR ,Reach-1
Reach XY= 30
       3692893.5       10494383.        3694219.       10494764.
      3694423.25       10495136.      3695180.75       10494843.
      3696174.75       10493880.       3697139.5       10494150.
       3697884.5       10493717.      3698706.75       10494244.
        3699664.       10494193.      3700304.25       10494608.
       3700346.5       10495806.      3701733.25       10496726.
      3702745.25       10496778.      3703405.25       10497387.
      3703377.75       10497735.      3704144.75       10498159.
      3706678.75       10498733.      3708435.25       10499739.
      3709508.25       10499633.      3709889.25       10500028.
        3711013.       10499893.       3712593.5       10503560.
       3713468.5       10503787.       3714480.5       10502732.
        3715039.       10502661.      3716825.25       10503928.
      3717300.25       10503957.        3717869.       10505430.
       3719929.5       10504820.      3720909.75       10505291.

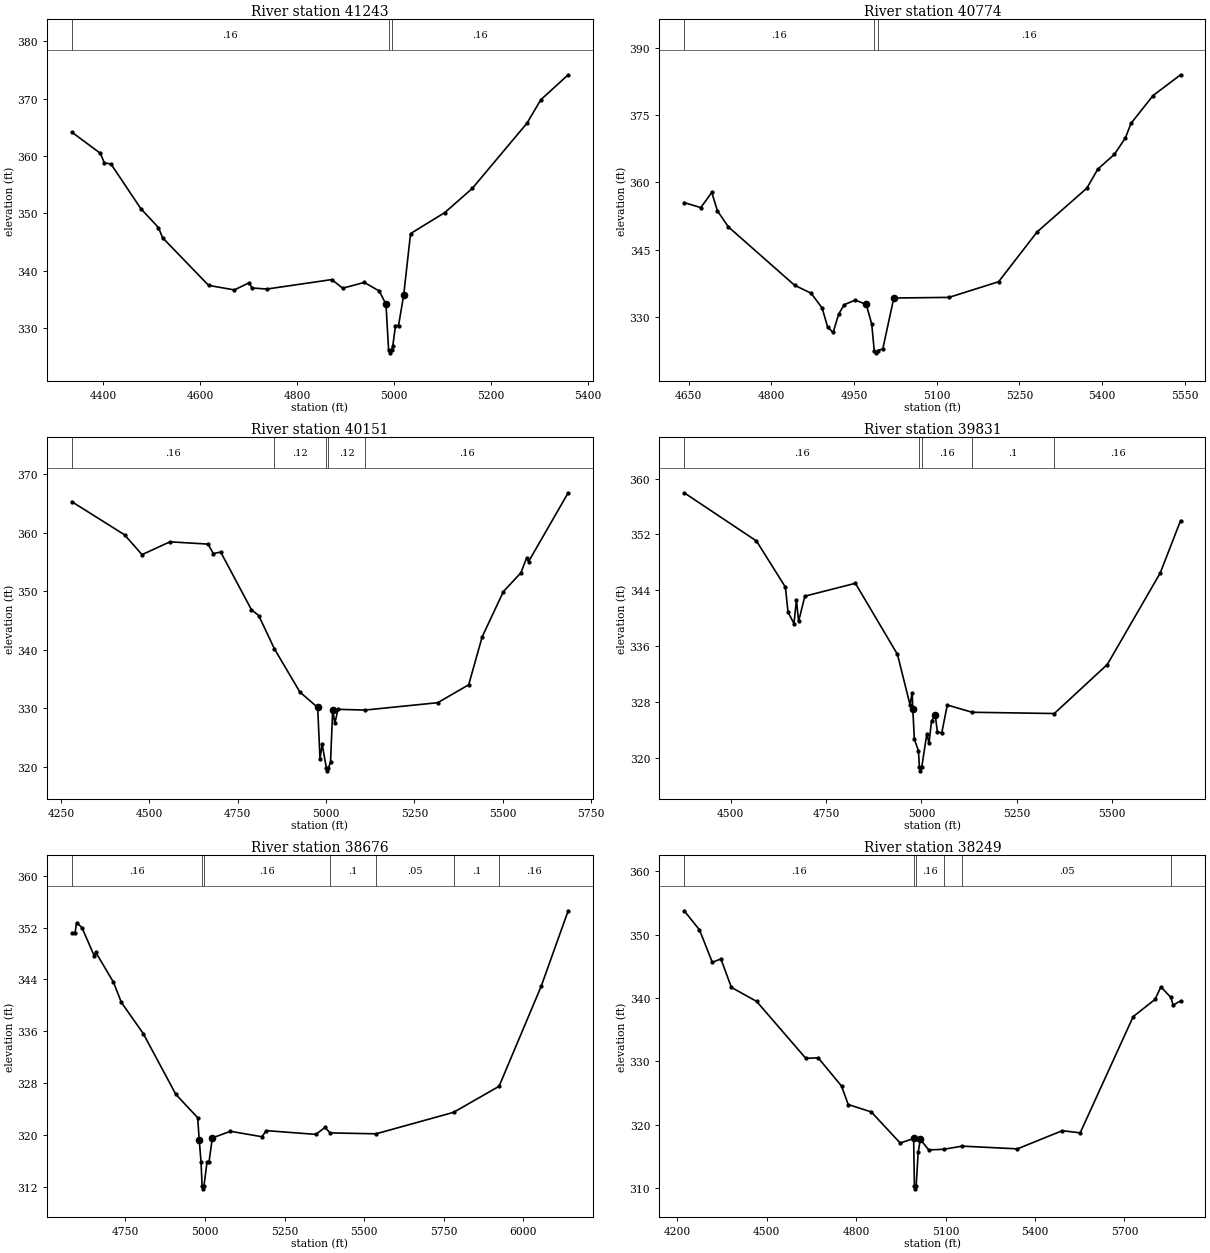
Type RM Length L Ch R = 1 ,41243   ,469,469,469
BEGIN DESCRIPTION:
UNT 199 IN UKCR 80.0
END DESCRIPTION:
XS GIS Cut Line= 3
      3692649.62     10495010.17      3692949.61     10494410.19
      3693199.64     10494160.15
#Sta/Elev= 30
  4334.7  364.17  4393.4   360.5  4401.8  358.84  4415.7   358.6  4477.2  350.84
  4513.6  347.54  4521.9  345.79    4617  337.48  4670.1  336.69  4700.8  337.94
  4706.4  337.03  4737.2  336.84  4871.3  338.49  4893.7  336.99  4938.4  337.99
  4969.2   336.5  4983.1  334.19  4988.5  326.23  4991.3  325.73  4994.5  326.23
  4997.1  326.86  5002.7  330.48    5009  330.48  5019.6  335.76  5033.8   346.5
  5104.5  350.16  5161.1  354.36  5274.2  365.74  5302.5   369.8  5359.1  374.16
#Mann= 3 ,-1 , 0
  4334.7     .16       0  4988.5     .07       0  4994.5     .16       0
Bank Sta=4983.1,5019.6
XS Rating Curve= 0 ,0
Exp/Cntr=0.3,0.1

Type RM Length L Ch R = 1 ,40774   ,623,623,623
BEGIN DESCRIPTION:
UNT 199 IN UKCR 79.0
END DESCRIPTION:
XS GIS Cut Line= 3
      3693299.61     10494960.17      3693299.61     10494610.19
      3693299.61     10494060.17
#Sta/Elev= 30
  4642.1  355.53  4672.1  354.41  4692.1  357.79  4702.1  353.73  4722.1  350.13
  4842.1  337.14  4872.1  335.36  4892.1  332.08  4902.1  327.85  4912.1  326.62
  4922.1  330.69  4932.1   332.8  4952.1  333.83  4972.1  332.87  4982.1   328.5
  4986.6  322.59  4989.3  322.09  4992.6  322.59  5002.1  322.95  5022.1  334.29
  5122.1  334.43  5212.1  337.91  5282.1  349.02  5372.1  358.73  5392.1  362.99
  5422.1  366.26  5442.1  369.94  5452.1  373.14  5492.1  379.34  5542.1  383.97
#Mann= 3 ,-1 , 0
  4642.1     .16       0  4986.6     .07       0  4992.6     .16       0
Bank Sta=4972.1,5022.1
XS Rating Curve= 0 ,0
Exp/Cntr=0.3,0.1

Type RM Length L Ch R = 1 ,40151   ,320,320,320
BEGIN DESCRIPTION:
UNT 199 IN UKCR 78.0
END DESCRIPTION:
XS GIS Cut Line= 3
      3693367.44     10495354.16      3693801.47     10494720.48
      3693499.61     10494160.19
#Sta/Elev= 30
  4280.5  365.27  4429.7  359.62  4479.2  356.23  4558.3  358.42    4666  358.03
  4680.9  356.42  4701.8  356.67  4788.5  346.86  4809.5  345.82  4853.9  340.14
    4926  332.77  4976.2  330.15  4982.8  321.36  4988.9  323.87  5000.8  319.83
  5003.5  319.33  5006.8  319.83  5012.6  320.83  5018.7  329.79  5024.7  327.43
  5033.6  329.83  5109.7   329.7  5315.9  330.96  5403.5  334.02  5441.7  342.21
  5501.7  349.93  5551.2  353.13  5567.4  355.67  5573.1  355.06    5685  366.79
#Mann= 5 ,-1 , 0
  4280.5     .16       0  4853.9     .12       0  5000.8     .07       0
  5006.8     .12       0  5109.7     .16       0
Bank Sta=4976.2,5018.7
XS Rating Curve= 0 ,0
Exp/Cntr=0.3,0.1

Type RM Length L Ch R = 1 ,39831   ,1155,1155,1155
BEGIN DESCRIPTION:
UNT 199 IN UKCR 77.0
END DESCRIPTION:
XS GIS Cut Line= 3
      3693758.08     10495345.46      3694070.56     10494746.52
      3693849.62     10494160.22
#Sta/Elev= 30
  4377.7  357.97  4567.3  351.05  4643.1  344.44    4650  340.86  4665.6  339.22
  4672.1   342.6  4677.7  339.52  4694.2  343.14  4826.7  344.99  4937.1  334.79
    4970  327.57  4975.7  329.29 4977.27  326.96  4981.4  322.64  4992.1  320.96
  4994.7  318.59  4997.5  318.09  5000.7  318.59  5014.2  323.42  5019.8  322.04
  5026.6  325.28  5036.3  326.03  5041.9  323.65  5053.3  323.54  5067.8  327.53
  5133.1  326.49  5348.5  326.31  5487.5  333.34  5626.4  346.47  5679.8  353.98
#Mann= 5 ,-1 , 0
  4377.7     .16       0  4994.7     .07       0  5000.7     .16       0
  5133.1      .1       0  5348.5     .16       0
Bank Sta=4977.27,5036.3
XS Rating Curve= 0 ,0
Exp/Cntr=0.3,0.1

Type RM Length L Ch R = 1 ,38676   ,427,427,427
BEGIN DESCRIPTION:
UNT 199 IN UKCR 76.0
END DESCRIPTION:
XS GIS Cut Line= 3
      3694599.61     10495360.18      3694749.61     10494960.19
      3693949.58     10494160.16
#Sta/Elev= 30
    4582  351.18  4591.8  351.11  4597.1  352.77    4614  351.99  4652.3  347.65
  4657.6  348.16  4712.8  343.57  4737.7  340.44  4806.3  335.64  4908.6  326.25
  4977.2  322.64 4982.17  319.19  4987.8  315.77  4991.1  312.15  4993.8  311.65
  4997.1  312.15  5006.5  315.74  5012.7  315.74  5023.3  319.51  5079.9  320.54
  5178.9   319.7    5193  320.64  5348.6  320.06  5376.9  321.14  5393.1  320.29
  5537.4  320.15  5780.9  323.47  5923.6  327.49  6055.7  342.92  6140.6   354.6
#Mann= 7 ,-1 , 0
    4582     .16       0  4991.1     .07       0  4997.1     .16       0
  5393.1      .1       0  5537.4     .05       0  5780.9      .1       0
  5923.6     .16       0
Bank Sta=4982.17,5023.3
XS Rating Curve= 0 ,0
Exp/Cntr=0.3,0.1

Type RM Length L Ch R = 1 ,38249   ,682,682,682
BEGIN DESCRIPTION:
UNT 199 IN UKCR 75.0
END DESCRIPTION:
XS GIS Cut Line= 4
      3695483.31     10495469.16      3695081.85     10494970.04
      3694875.69     10494546.87      3694832.35     10493994.33
#Sta/Elev= 30
  4223.1  353.79  4274.2  350.78  4317.4  345.64  4346.2  346.18  4381.4  341.68
  4466.2  339.46    4631  330.47  4672.6  330.55    4751  326.08  4773.3  323.17
  4850.6     322  4947.8  317.08  4992.9   317.8  4995.4  310.34  4998.2  309.84
  5001.4  310.34  5008.1  315.64  5015.4  317.65  5043.5  315.99  5093.2  316.09
    5156  316.59  5341.1  316.16  5491.5  319.03  5551.7  318.69  5729.5  337.06
  5802.5  339.77  5822.5  341.76  5855.7  340.11  5863.7  338.88  5888.6  339.55
#Mann= 6 ,-1 , 0
  4223.1     .16       0  4995.4     .07       0  5001.4     .16       0
  5093.2      .1       0    5156     .05       0  5855.7     .16       0
Bank Sta=4992.9,5015.4
XS Rating Curve= 0 ,0
Exp/Cntr=0.3,0.1

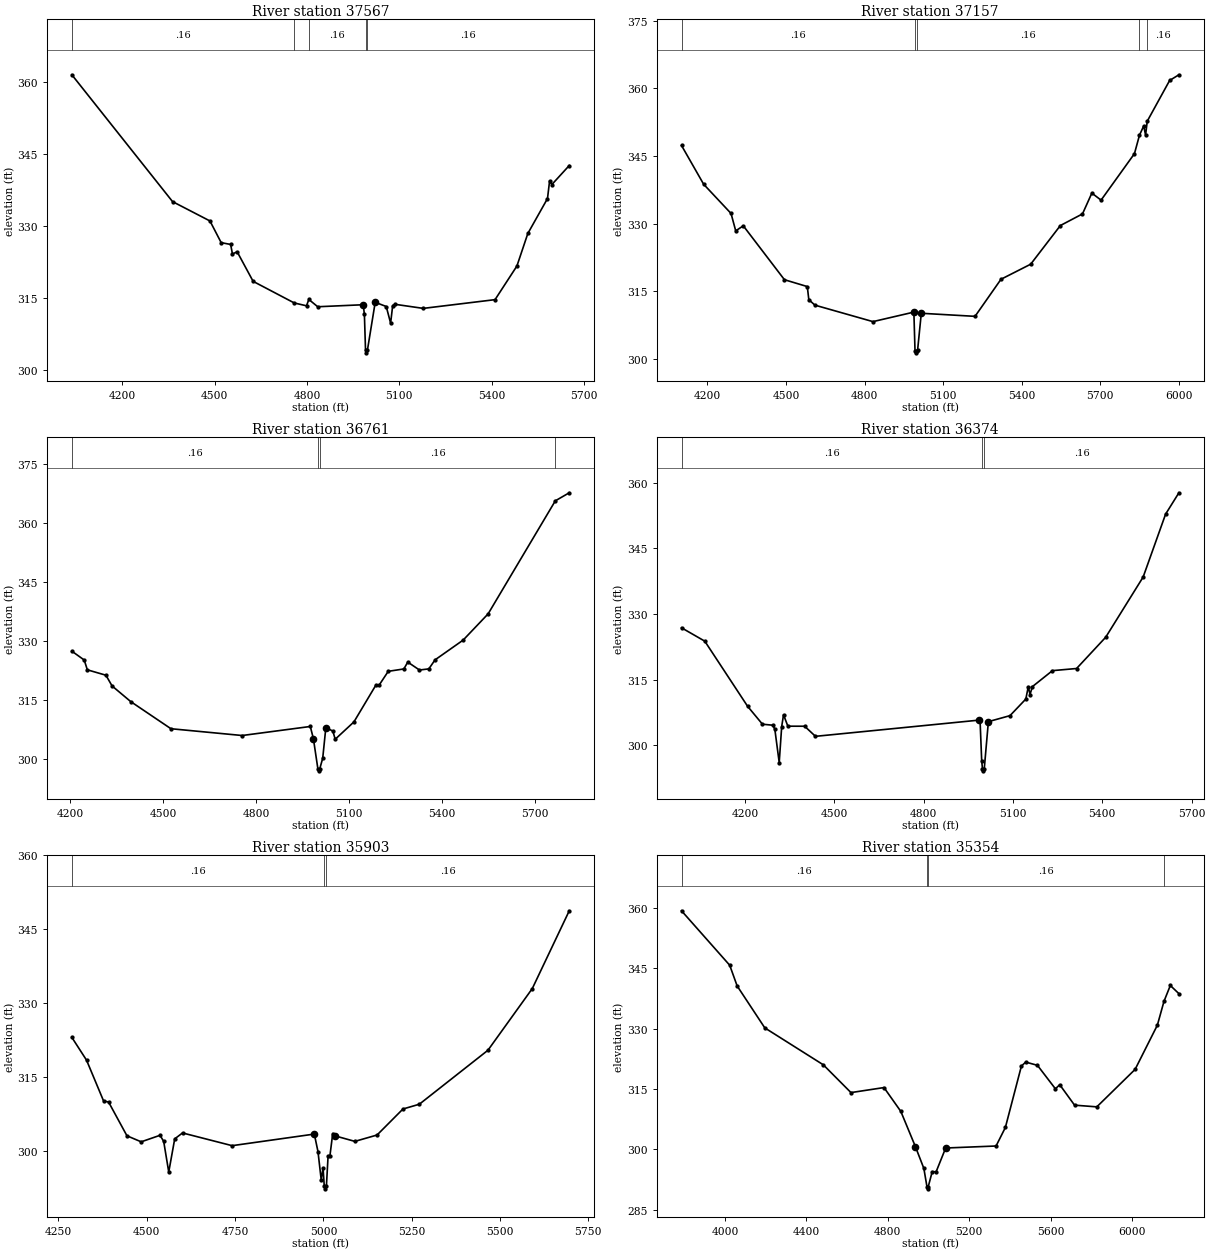
Type RM Length L Ch R = 1 ,37567   ,410,410,410
BEGIN DESCRIPTION:
UNT 199 IN UKCR 74.0
END DESCRIPTION:
XS GIS Cut Line= 3
       3695849.6     10495310.17      3695349.61     10494510.19
      3694899.58     10494010.16
#Sta/Elev= 30
  4036.3  361.43  4363.5  335.01    4485  330.98  4521.5  326.46  4552.2  326.09
  4558.1  324.11  4573.4  324.56  4625.3   318.4  4759.2  313.89  4798.7  313.31
  4806.3  314.63  4835.2  313.11    4983  313.53  4986.8  311.52  4990.5  304.01
  4993.3  303.51  4996.5  304.01  5021.9  314.04  5057.8  313.16    5072  309.69
  5078.7  313.36  5086.2  313.62  5178.1  312.77  5411.3  314.59  5482.3  321.59
  5517.8  328.37  5581.7  335.65  5588.5  339.32  5595.9  338.57  5652.4  342.53
#Mann= 5 ,-1 , 0
  4036.3     .16       0  4759.2      .1       0  4806.3     .16       0
  4990.5     .07       0  4996.5     .16       0
Bank Sta=4983,5021.9
XS Rating Curve= 0 ,0
Exp/Cntr=0.3,0.1

Type RM Length L Ch R = 1 ,37157   ,396,396,396
BEGIN DESCRIPTION:
UNT 199 IN UKCR 73.0
END DESCRIPTION:
XS GIS Cut Line= 3
      3695999.62     10495060.21      3695649.61     10494260.19
      3694949.64     10493510.22
#Sta/Elev= 30
  4100.9  347.35  4185.5  338.75    4290  332.28  4307.9  328.42  4336.8  329.54
  4493.9  317.59  4581.2  316.07    4587  313.16  4610.4  311.95  4831.8   308.3
  4988.1  310.41  4992.4  301.88  4995.1  301.38  4998.4  301.88  5002.2  301.91
  5016.4  310.15  5221.6  309.47  5320.7  317.69  5434.1  321.03  5547.4   329.6
  5631.9  332.18  5667.6  336.79  5702.8  335.23  5830.3  345.54  5849.5  349.64
  5865.5  351.66  5872.8  349.66  5879.1  352.73  5964.6  361.76    6000  363.02
#Mann= 5 ,-1 , 0
  4100.9     .16       0  4992.4     .07       0  4998.4     .16       0
  5849.5     .12       0  5879.1     .16       0
Bank Sta=4988.1,5016.4
XS Rating Curve= 0 ,0
Exp/Cntr=0.3,0.1

Type RM Length L Ch R = 1 ,36761   ,387,387,387
BEGIN DESCRIPTION:
UNT 199 IN UKCR 72.0
END DESCRIPTION:
XS GIS Cut Line= 3
      3695949.61     10494810.18      3695949.61     10494010.19
      3695849.61     10493210.21
#Sta/Elev= 30
  4205.1  327.44  4245.1  325.19  4255.1  322.71  4315.1  321.34  4335.1  318.61
  4395.1  314.66  4525.1  307.77  4755.1  306.05  4975.1  308.34  4985.1  305.24
  4999.6  297.59  5002.3  297.09  5005.6  297.59  5015.2   300.3  5025.3  308.07
  5047.9  307.17  5055.5   305.1    5116   309.5  5186.5  318.78  5196.6  318.74
  5226.8  322.33  5277.2  322.93  5289.8  324.67  5327.6  322.66  5357.8  322.95
    5378  325.24  5468.7  330.25  5549.3   336.9  5766.3  365.57  5811.3  367.61
#Mann= 4 ,-1 , 0
  4205.1     .16       0  4999.6     .07       0  5005.6     .16       0
  5766.3     .05       0
Bank Sta=4985.1,5025.3
XS Rating Curve= 0 ,0
Exp/Cntr=0.3,0.1

Type RM Length L Ch R = 1 ,36374   ,471,471,471
BEGIN DESCRIPTION:
UNT 199 IN UKCR 71.0
END DESCRIPTION:
XS GIS Cut Line= 3
      3696899.63     10494710.21      3696299.61     10493910.19
      3695999.63     10493310.23
#Sta/Elev= 30
  3986.5  326.84  4064.7  323.78  4208.4   308.9  4258.4  304.79  4293.8  304.56
  4300.1  303.59  4314.7  296.03    4323  304.23  4329.2  306.95  4343.8  304.34
  4400.1  304.33  4436.5  302.02  4986.5  305.73  4989.3  305.73  4994.9  296.35
  4997.5  294.63  5000.3  294.13  5003.5  294.63  5017.3  305.38  5089.9  306.75
  5143.1  310.55  5151.4  313.39    5157  311.58  5165.4   313.4  5232.5  317.04
  5313.6  317.53  5411.4  324.68  5537.2  338.45  5612.6  352.83  5657.3  357.71
#Mann= 3 ,-1 , 0
  3986.5     .16       0  4997.5     .07       0  5003.5     .16       0
Bank Sta=4986.5,5017.3
XS Rating Curve= 0 ,0
Exp/Cntr=0.3,0.1

Type RM Length L Ch R = 1 ,35903   ,549,549,549
BEGIN DESCRIPTION:
UNT 199 IN UKCR 70.0
END DESCRIPTION:
XS GIS Cut Line= 3
      3696949.61     10494610.19      3696749.61     10493910.19
       3696549.6     10493260.17
#Sta/Elev= 30
  4287.8   323.1  4329.4  318.48  4377.5  310.23  4391.8  309.99  4443.8  303.15
  4484.1  301.93  4537.4  303.25  4547.8  302.02  4562.1  295.81    4579  302.53
  4601.1  303.73  4741.5  301.15  4974.2   303.5  4984.6  299.94  4993.7  294.23
  4998.9  296.66  5002.4   292.9  5005.2   292.4  5008.4   292.9  5013.2   299.1
  5018.4   299.1  5026.3  303.61  5032.2  303.15    5089  302.02  5151.8  303.31
  5225.1  308.58  5271.5  309.55  5465.7  320.49  5591.3     333  5695.9  348.76
#Mann= 3 ,-1 , 0
  4287.8     .16       0  5002.4     .07       0  5008.4     .16       0
Bank Sta=4974.2,5032.2
XS Rating Curve= 0 ,0
Exp/Cntr=0.3,0.1

Type RM Length L Ch R = 1 ,35354   ,338,338,338
BEGIN DESCRIPTION:
UNT 199 IN UKCR 69.0
END DESCRIPTION:
XS GIS Cut Line= 3
      3697479.86      10495317.3      3697143.48     10493928.38
      3696600.97      10493071.2
#Sta/Elev= 30
  3786.5  359.36  4023.3  345.81  4059.9  340.65  4195.7  330.22  4483.2  321.03
    4619  314.12  4781.2  315.37  4863.9  309.44  4935.9  300.63  4977.1  295.24
  4992.4  290.67  4995.2  290.17  4998.4  290.67  5018.2  294.45  5037.2   294.4
  5084.2  300.33  5331.8  300.83  5377.5  305.44  5456.3  320.73  5477.5  321.71
  5535.1   320.9  5623.3  315.06  5644.5  316.08  5717.4  310.99  5826.7  310.57
  6014.9   319.9  6124.2   330.9  6156.7  336.83  6187.8  340.77    6230  338.74
#Mann= 4 ,-1 , 0
  3786.5     .16       0  4992.4     .07       0  4998.4     .16       0
  6156.7     .05       0
Bank Sta=4935.9,5084.2
XS Rating Curve= 0 ,0
Exp/Cntr=0.3,0.1

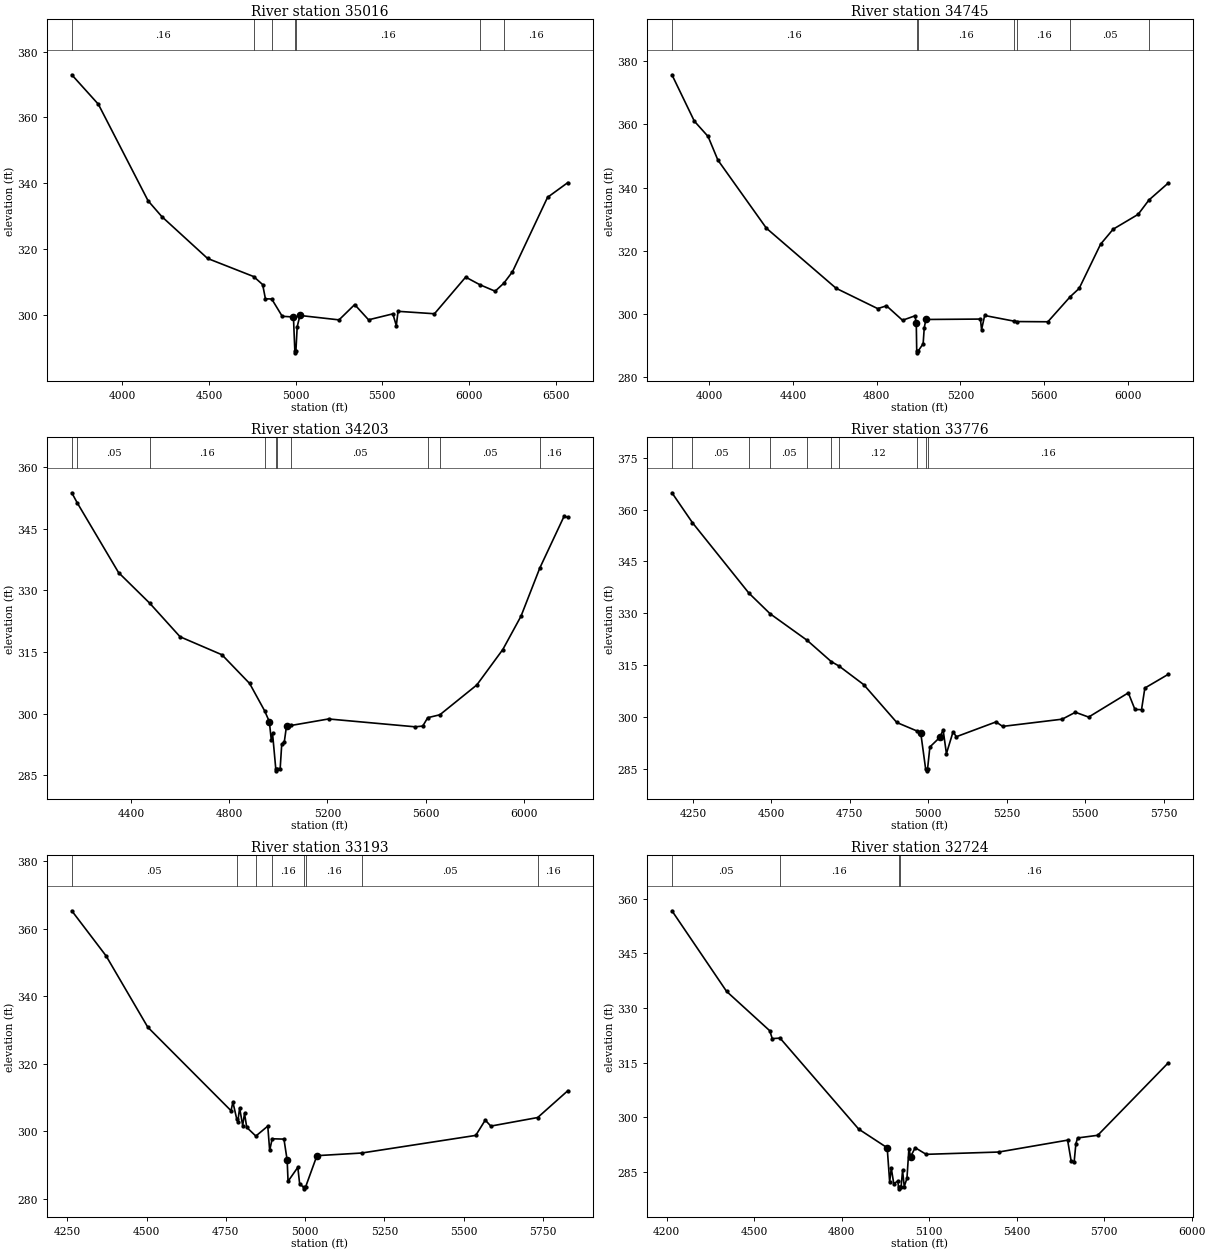
Type RM Length L Ch R = 1 ,35016   ,271,271,271
BEGIN DESCRIPTION:
UNT 199 IN UKCR 68.0
END DESCRIPTION:
XS GIS Cut Line= 3
      3697881.34     10495219.64      3697414.75     10493743.92
       3697425.6     10492430.99
#Sta/Elev= 30
  3708.9  372.93  3862.2  363.98  4148.8  334.67  4228.1  329.86  4491.9  317.15
  4757.7  311.65  4809.6  309.21  4825.6  304.89  4861.9  304.83  4922.5  299.58
  4987.2  299.37  4995.3  288.98  4998.1  288.48  5001.3  288.98  5008.8  296.41
  5024.7  299.83  5250.1  298.49  5340.4  303.14  5420.4  298.51  5560.4  300.32
  5580.4  296.75  5590.4  301.09  5800.4  300.35  5980.4  311.48  6062.1  309.17
  6150.4   307.2  6200.9  309.66  6250.4  313.12  6452.6  335.71  6569.6  340.19
#Mann= 7 ,-1 , 0
  3708.9     .16       0  4757.7     .12       0  4861.9     .16       0
  4995.3     .07       0  5001.3     .16       0  6062.1     .05       0
  6200.9     .16       0
Bank Sta=4987.2,5024.7
XS Rating Curve= 0 ,0
Exp/Cntr=0.3,0.1

Type RM Length L Ch R = 1 ,34745   ,542,542,542
BEGIN DESCRIPTION:
UNT 199 IN UKCR 67.0
END DESCRIPTION:
XS GIS Cut Line= 3
      3698054.95     10494970.08      3697631.76     10493581.16
      3697729.41     10492669.73
#Sta/Elev= 30
  3822.7  375.72  3929.6  361.03  3995.2  356.18  4042.1  348.69  4273.6  327.12
  4606.6  308.08  4805.2  301.64  4847.1  302.53  4923.6  297.95    4983  299.35
  4989.3  297.04  4991.5  288.13  4994.3  287.63  4997.5  288.13  5022.1   290.5
  5027.4  295.57  5035.2   298.2  5295.7  298.33  5301.1  294.97  5315.9  299.46
  5454.7  297.69  5471.2  297.54  5617.6  297.47  5724.6  305.43  5767.1  308.04
  5869.3  322.04  5929.4   326.8  6048.7   331.5  6100.2  336.04  6191.3  341.35
#Mann= 7 ,-1 , 0
  3822.7     .16       0  4991.5     .07       0  4997.5     .16       0
  5454.7     .05       0  5471.2     .16       0  5724.6     .05       0
  6100.2     .16       0
Bank Sta=4989.3,5035.2
XS Rating Curve= 0 ,0
Exp/Cntr=0.3,0.1

Type RM Length L Ch R = 1 ,34203   ,427,427,427
BEGIN DESCRIPTION:
UNT 199 IN UKCR 66.0
END DESCRIPTION:
XS GIS Cut Line= 3
      3698249.61     10494660.17      3698199.61     10493860.19
      3697799.62     10492710.21
#Sta/Elev= 30
  4159.5  353.74  4181.1  351.35  4349.9  334.31  4476.8  326.85  4600.3  318.68
  4770.7   314.3  4883.4  307.31  4944.3  300.67  4963.7  298.01  4971.3  293.63
  4976.6  295.19  4989.8  286.54  4992.6  286.04  4995.8  286.54  5007.7   286.6
    5014  292.46  5024.6  293.13  5033.5  296.95  5053.2   297.1  5204.6  298.67
  5556.9  296.76    5588  296.94  5608.3  298.98  5657.7  299.69  5808.1  306.95
  5913.9  315.58    5988   323.7  6064.4  335.41  6163.1     348  6178.6  347.77
#Mann= 10 ,-1 , 0
  4159.5     .16       0  4181.1     .05       0  4476.8     .16       0
  4944.3     .12       0  4989.8     .07       0  4995.8     .12       0
  5053.2     .05       0  5608.3     .16       0  5657.7     .05       0
  6064.4     .16       0
Bank Sta=4963.7,5033.5
XS Rating Curve= 0 ,0
Exp/Cntr=0.3,0.1

Type RM Length L Ch R = 1 ,33776   ,583,583,583
BEGIN DESCRIPTION:
UNT 199 IN UKCR 65.0
END DESCRIPTION:
XS GIS Cut Line= 3
       3698299.6     10494760.22      3698549.61     10494010.19
      3698799.62     10493260.17
#Sta/Elev= 30
  4182.9  364.84  4248.3  356.18    4428  335.82  4495.9  329.82  4613.7  322.15
  4690.5     316  4715.9  314.67  4794.3  309.31  4899.7  298.36  4963.5  295.92
  4976.1  295.25  4991.6  284.87  4994.3  284.37  4997.6  284.87  5005.1  291.28
  5036.8  294.06  5047.3  296.22  5057.8  289.34  5078.9  295.65  5089.5  294.25
  5215.9  298.53    5237  297.23  5426.8  299.32  5468.9  301.32  5511.1  299.93
  5637.6  306.94  5658.7  302.13  5679.7  302.07  5690.3  308.33  5764.1  312.26
#Mann= 10 ,-1 , 0
  4182.9     .16       0  4248.3     .05       0    4428     .16       0
  4495.9     .05       0  4613.7     .16       0  4690.5     .05       0
  4715.9     .12       0  4963.5     .16       0  4991.6     .07       0
  4997.6     .16       0
Bank Sta=4976.1,5036.8
XS Rating Curve= 0 ,0
Exp/Cntr=0.3,0.1

Type RM Length L Ch R = 1 ,33193   ,469,469,469
BEGIN DESCRIPTION:
UNT 199 IN UKCR 64.0
END DESCRIPTION:
XS GIS Cut Line= 3
      3698499.59     10494860.23      3698899.61     10494210.19
      3698849.61     10493410.21
#Sta/Elev= 30
  4264.1  365.37  4372.4  351.98  4503.8  330.85  4766.5  306.07  4772.3  308.64
  4784.1  303.74  4787.8  302.83  4793.6  306.87  4803.2  301.67    4809  305.28
    4816  301.13  4844.7  298.55  4882.4  301.51  4888.3  294.29  4896.3  297.75
  4933.4  297.65 4943.52  291.39  4946.3  285.13  4977.1  289.28    4983  284.29
  4995.4   283.4  4998.1   282.9  5001.4   283.4  5037.4  292.74  5178.1  293.52
  5538.4  298.75  5568.4  303.29  5585.9  301.51  5733.8  304.05  5828.9  312.01
#Mann= 8 ,-1 , 0
  4264.1     .05       0  4784.1     .16       0  4844.7     .12       0
  4896.3     .16       0  4995.4     .07       0  5001.4     .16       0
  5178.1     .05       0  5733.8     .16       0
Bank Sta=4943.52,5037.4
XS Rating Curve= 0 ,0
Exp/Cntr=0.3,0.1

Type RM Length L Ch R = 1 ,32724   ,1015,1015,1015
BEGIN DESCRIPTION:
UNT 199 IN UKCR 63.0
END DESCRIPTION:
XS GIS Cut Line= 3
      3698899.61     10495010.19      3699249.61     10494310.19
      3699699.61     10493510.19
#Sta/Elev= 30
  4218.4  356.66  4405.7  334.56  4553.8  323.76  4562.2  321.62    4589  321.75
  4858.5  296.81  4956.3  291.69  4964.7  282.34  4970.3  286.06  4978.7  281.89
  4992.6  282.53  4995.2  280.93    4998  280.43  5001.2  280.93  5003.9  280.93
    5009  285.47  5014.7  281.06    5024  283.29  5030.7  291.45  5036.4  289.26
  5052.3   291.7  5089.9  289.89  5338.5  290.52  5574.7  293.78  5587.1  287.97
  5597.3  287.91  5603.1  292.81  5609.1  294.38    5678  295.11  5918.9   314.9
#Mann= 4 ,-1 , 0
  4218.4     .05       0    4589     .16       0  4995.2     .07       0
  5001.2     .16       0
Bank Sta=4956.3,5036.4
XS Rating Curve= 0 ,0
Exp/Cntr=0.3,0.1

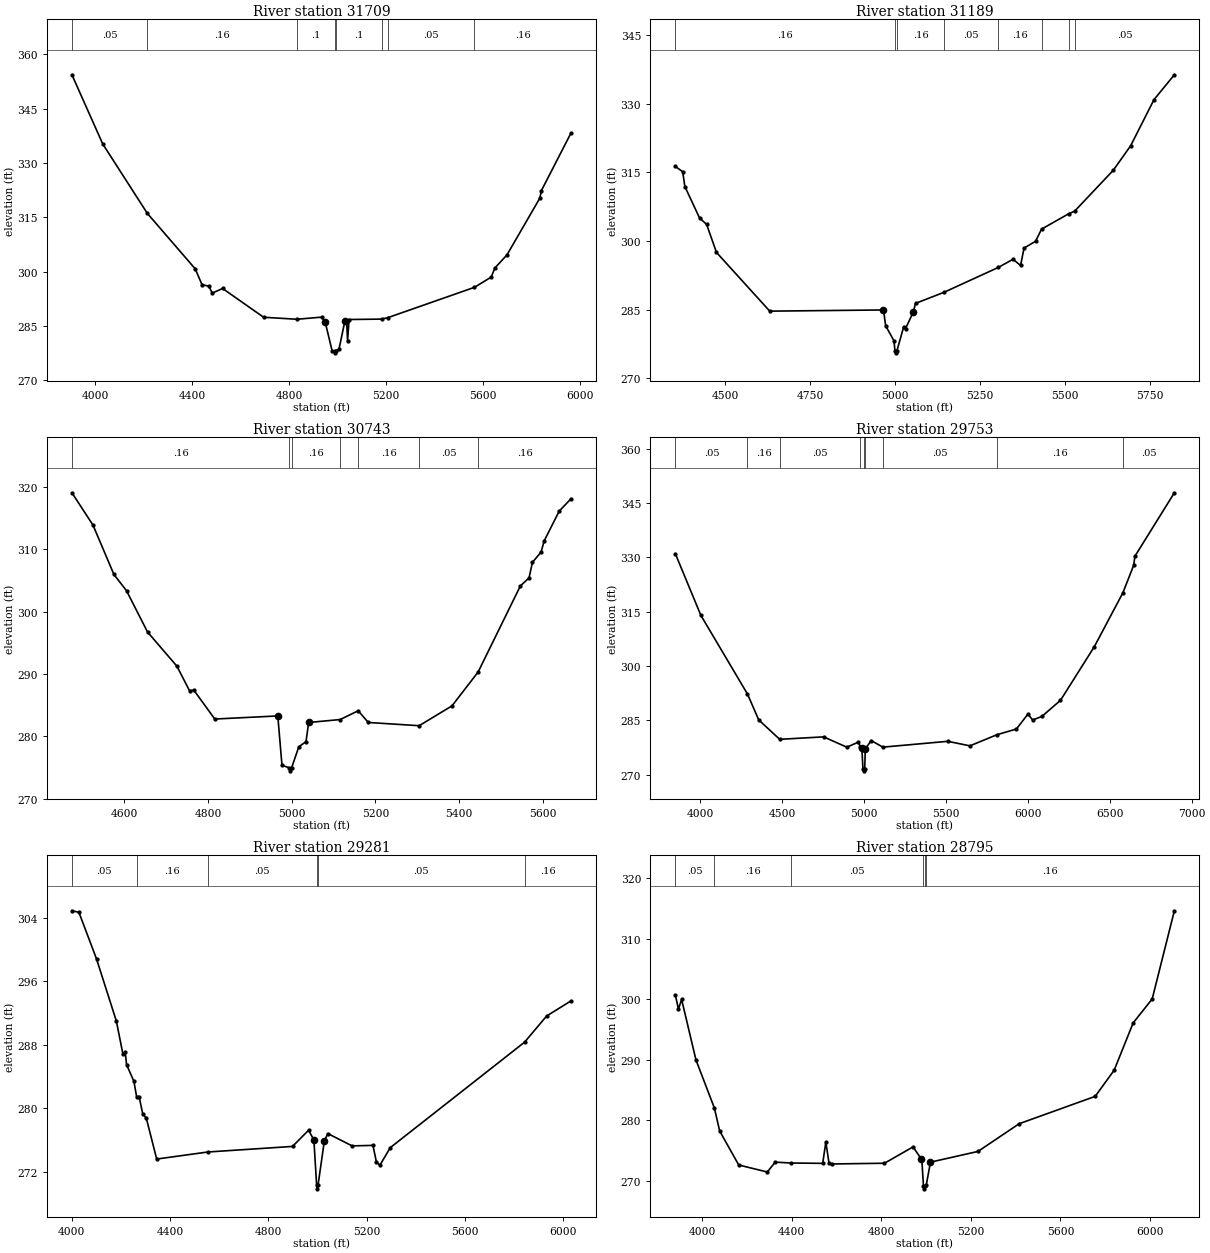
Type RM Length L Ch R = 1 ,31709   ,520,520,520
BEGIN DESCRIPTION:
UNT 199 IN UKCR 61.0
END DESCRIPTION:
XS GIS Cut Line= 3
      3699149.62     10495160.18      3699949.61     10494360.19
      3700499.61     10493610.19
#Sta/Elev= 30
    3903  354.38  4030.3  335.28  4214.6  316.11  4412.1  300.83  4440.4  296.45
  4468.7  296.03  4482.8  294.11  4525.2   295.4  4694.9  287.45  4832.8   286.9
  4935.4  287.49  4949.5  286.04  4977.8  278.19  4988.9  278.13  4991.7  277.63
  4994.9  278.13  5006.1  278.63  5030.8  286.45  5037.5  286.45  5041.7  280.97
  5047.9  286.83  5182.5  286.94  5208.7  287.36  5565.7  295.71  5635.2  298.54
  5649.9  301.03    5700  304.65  5835.9  320.33  5842.1  322.38  5964.4  338.28
#Mann= 8 ,-1 , 0
    3903     .05       0  4214.6     .16       0  4832.8      .1       0
  4988.9     .07       0  4994.9      .1       0  5182.5     .16       0
  5208.7     .05       0  5565.7     .16       0
Bank Sta=4949.5,5030.8
XS Rating Curve= 0 ,0
Exp/Cntr=0.3,0.1

Type RM Length L Ch R = 1 ,31189   ,446,446,446
BEGIN DESCRIPTION:
UNT 199 IN UKCR 60.0
END DESCRIPTION:
XS GIS Cut Line= 3
      3699749.61     10494960.19      3700249.61     10494560.19
      3700999.65     10494210.17
#Sta/Elev= 30
  4353.3  316.28  4374.9  315.12  4381.3  311.89  4424.5  305.01  4445.3  303.62
  4474.2   297.5    4631  284.66  4965.6  284.92    4972  281.46  4996.4  278.19
  4999.3  276.05    5002  275.55  5005.3  276.05  5025.1  281.25  5030.7  280.86
  5053.5  284.52  5059.8  286.35  5143.8  288.78  5303.4  294.21  5346.7  295.99
  5368.8  294.64  5379.1  298.43    5413  299.93  5430.6  302.58  5510.1  305.92
  5527.9   306.5  5641.5  315.43  5692.8   320.8  5761.4  330.87  5821.3   336.3
#Mann= 8 ,-1 , 0
  4353.3     .16       0  4999.3     .07       0  5005.3     .16       0
  5143.8     .05       0  5303.4     .16       0  5430.6     .05       0
  5510.1     .16       0  5527.9     .05       0
Bank Sta=4965.6,5053.5
XS Rating Curve= 0 ,0
Exp/Cntr=0.3,0.1

Type RM Length L Ch R = 1 ,30743   ,990,990,990
BEGIN DESCRIPTION:
UNT 199 IN UKCR 59.0
END DESCRIPTION:
XS GIS Cut Line= 3
      3699749.63     10495010.19      3700299.61     10494960.19
      3700799.64     10494560.16
#Sta/Elev= 30
  4474.7  319.05  4524.9  313.88  4575.1  305.94  4605.2  303.33  4655.4  296.71
  4725.7  291.22  4755.8  287.28  4765.9   287.4  4816.1  282.75  4966.7  283.25
  4976.7  275.33  4993.8  274.94  4996.6  274.44  4999.8  274.94  5016.9   278.3
  5034.1  279.12  5040.5   282.2  5115.8  282.67  5158.9  284.08    5183   282.2
  5304.6  281.68  5383.1  284.87  5445.5   290.3  5546.4   304.1  5567.2   305.4
  5575.2  307.88    5596  309.55  5603.2  311.32  5639.2   316.1  5667.3  318.09
#Mann= 7 ,-1 , 0
  4474.7     .16       0  4993.8     .07       0  4999.8     .16       0
  5115.8     .05       0  5158.9     .16       0  5304.6     .05       0
  5445.5     .16       0
Bank Sta=4966.7,5040.5
XS Rating Curve= 0 ,0
Exp/Cntr=0.3,0.1

Type RM Length L Ch R = 1 ,29753   ,472,472,472
BEGIN DESCRIPTION:
UNT 199 IN UKCR 58.0
END DESCRIPTION:
XS GIS Cut Line= 3
       3699499.6      10496560.2      3700299.61     10495760.19
      3701549.61     10494310.19
#Sta/Elev= 30
  3848.7  330.96  4004.3  313.96  4289.1  292.21  4357.8  285.07  4485.6  279.72
  4753.8   280.4  4895.2  277.55  4965.9  278.94  4978.6  277.56  4987.2  277.26
  4993.8  271.53  4998.5  271.52  5001.2  271.02  5004.5  271.52  5008.1   277.1
  5044.3  279.39    5115  277.56  5511.6  279.17  5646.6  277.92  5809.4  280.95
  5930.7  282.58  6000.9   286.7  6029.5  285.05  6086.5  286.06  6199.5  290.49
  6405.7  305.27  6580.2  320.16    6646  327.73  6653.7  330.26  6894.5  347.78
#Mann= 9 ,-1 , 0
  3848.7     .05       0  4289.1     .16       0  4485.6     .05       0
  4978.6     .16       0  4998.5     .07       0  5004.5     .16       0
    5115     .05       0  5809.4     .16       0  6580.2     .05       0
Bank Sta=4987.2,5008.1
XS Rating Curve= 0 ,0
Exp/Cntr=0.3,0.1

Type RM Length L Ch R = 1 ,29281   ,486,486,486
BEGIN DESCRIPTION:
UNT 199 IN UKCR 57.0
END DESCRIPTION:
XS GIS Cut Line= 3
      3700099.59     10496810.21      3700649.61     10496010.19
       3701399.6      10495260.2
#Sta/Elev= 30
  4000.6  304.86    4029  304.67  4100.7   298.8  4181.3  290.99  4208.3   286.8
  4217.1  287.14  4223.2  285.48    4253  283.38  4264.2   281.4  4273.9  281.47
  4288.8  279.31  4303.7  278.71  4345.7   273.6  4554.1  274.49  4898.6  275.19
    4964  277.23  4985.6  276.01  4996.7  270.35  4999.5  269.85  5002.7  270.35
    5028  275.84  5042.2  276.81  5141.2  275.26    5226  275.32  5240.2  273.22
  5254.3  272.82  5296.7  275.04  5843.1  288.31  5933.1  291.61  6032.1  293.51
#Mann= 6 ,-1 , 0
  4000.6     .05       0  4264.2     .16       0  4554.1     .05       0
  4996.7     .03       0  5002.7     .05       0  5843.1     .16       0
Bank Sta=4985.6,5028
XS Rating Curve= 0 ,0
Exp/Cntr=0.3,0.1

Type RM Length L Ch R = 1 ,28795   ,399,399,399
BEGIN DESCRIPTION:
UNT 199 IN UKCR 56.0
END DESCRIPTION:
XS GIS Cut Line= 3
      3700249.63     10496910.17      3701049.61     10496160.19
      3701849.59     10495360.21
#Sta/Elev= 30
  3880.9  300.67  3894.8  298.35    3909  299.93  3972.9  289.95  4055.1     282
  4078.9  278.19  4163.9  272.58  4291.4  271.42  4326.6  273.05  4397.3  272.91
  4538.8  272.85  4552.8  276.38  4566.9  272.89  4581.1  272.75  4814.6  272.87
  4942.1  275.57  4977.5  273.65    4981  273.65  4988.6  269.14  4991.4  268.64
  4994.6  269.14  5000.9  269.21  5019.9  273.05    5232  274.82  5415.9   279.4
  5755.3  283.92  5840.1  288.25    5925  296.07  6009.8  300.01  6108.8  314.59
#Mann= 6 ,-1 , 0
  3880.9     .05       0  4055.1     .16       0  4397.3     .05       0
  4988.6     .03       0  4994.6     .05       0  5000.9     .16       0
Bank Sta=4977.5,5019.9
XS Rating Curve= 0 ,0
Exp/Cntr=0.3,0.1

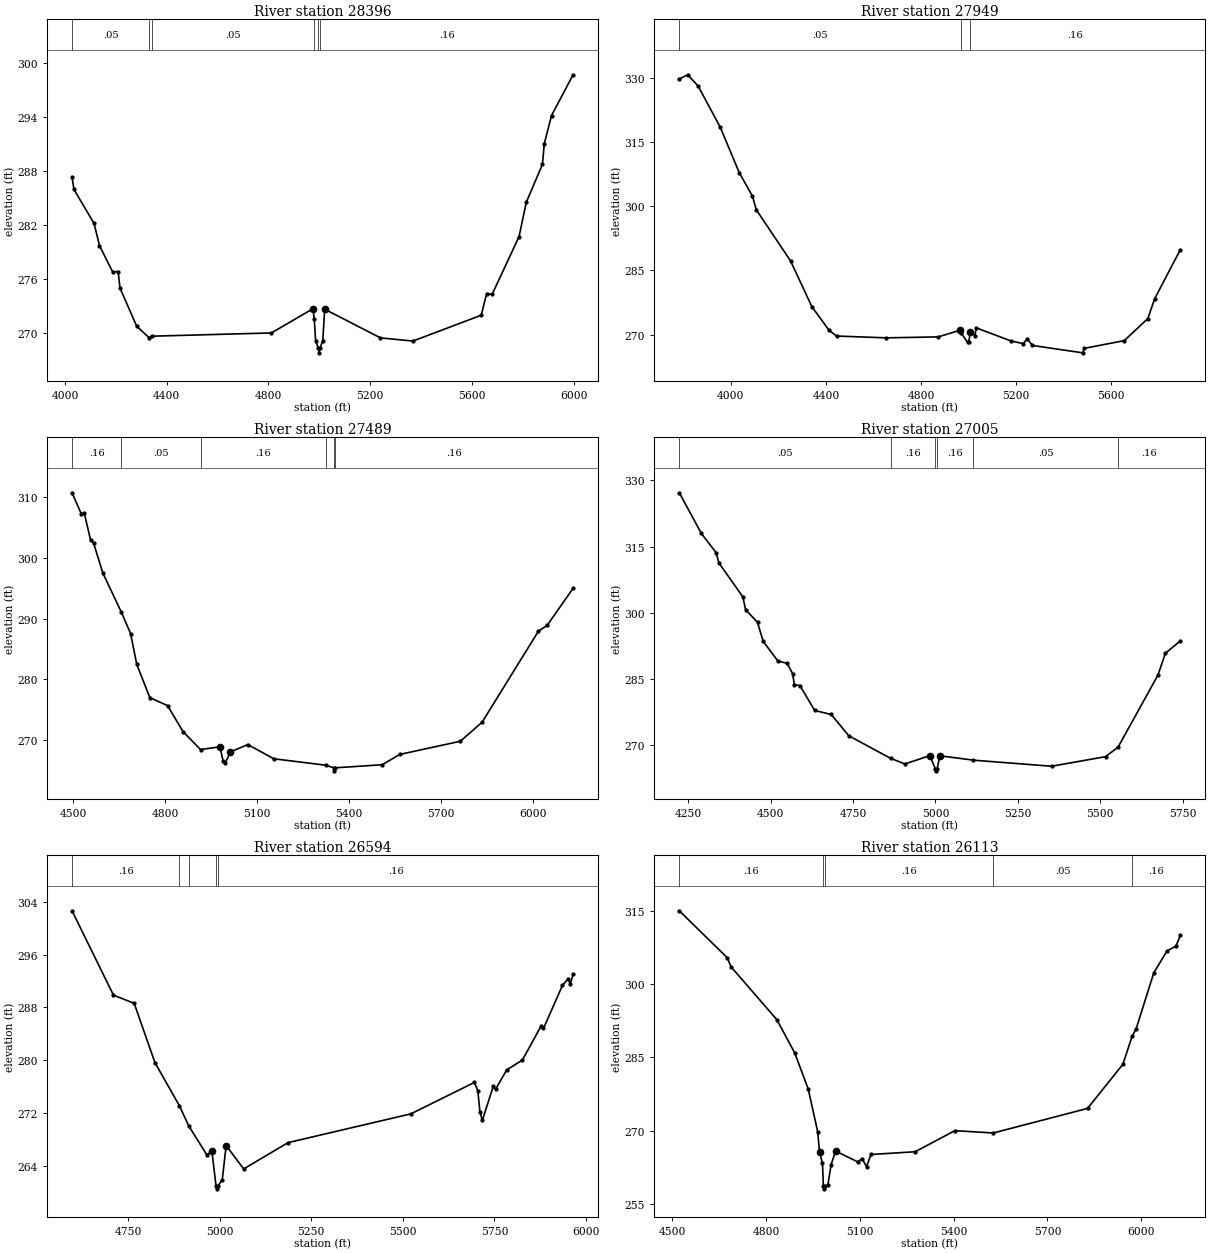
Type RM Length L Ch R = 1 ,28396   ,447,447,447
BEGIN DESCRIPTION:
UNT 199 IN UKCR 55.0
END DESCRIPTION:
XS GIS Cut Line= 3
      3700849.62     10497210.17      3701349.61     10496410.19
      3702099.61     10495710.19
#Sta/Elev= 30
  4027.9  287.32  4035.5  285.94  4114.6  282.16  4135.8  279.71  4187.7  276.77
  4208.9  276.82  4216.6  274.98    4282  270.75  4331.3  269.46  4341.8  269.64
  4811.5     270  4974.7  272.69    4980  271.55  4985.2  269.15  4996.4  268.29
  4999.1  267.79  5002.4  268.29  5013.5  269.16  5020.9  272.64  5240.2  269.45
  5367.7   269.1  5636.4  271.97  5657.4  274.38  5678.9  274.28  5784.9  280.71
  5813.3  284.52  5876.8  288.73  5884.1  291.04  5912.4  294.15  5997.2  298.68
#Mann= 6 ,-1 , 0
  4027.9     .05       0  4331.3     .07       0  4341.8     .05       0
    4980     .16       0  4996.4     .07       0  5002.4     .16       0
Bank Sta=4974.7,5020.9
XS Rating Curve= 0 ,0
Exp/Cntr=0.3,0.1

Type RM Length L Ch R = 1 ,27949   ,460,460,460
BEGIN DESCRIPTION:
UNT 199 IN UKCR 54.0
END DESCRIPTION:
XS GIS Cut Line= 3
      3701353.56     10497845.45      3701699.61     10496660.19
      3702049.63     10495860.15
#Sta/Elev= 30
  3783.4  329.68  3818.9  330.66  3862.8  328.01  3955.6  318.43  4035.3  307.85
    4091  302.34  4107.4  299.15  4251.7   287.2    4341  276.56  4413.9  271.01
  4445.2   269.7  4653.5  269.28  4872.3   269.5  4962.7  271.02  4967.9  270.51
  4996.2  268.24  5001.4  268.34  5007.7  270.67  5027.1   269.8  5032.6  271.61
  5178.4  268.56  5230.6  267.93  5247.4  269.05  5269.2   267.5  5480.6  265.78
  5487.5  266.83  5655.5  268.63  5754.5  273.78  5783.4  278.42  5891.4  289.86
#Mann= 3 ,-1 , 0
  3783.4     .05       0  4967.9     .07       0  5007.7     .16       0
Bank Sta=4962.7,5007.7
XS Rating Curve= 0 ,0
Exp/Cntr=0.3,0.1

Type RM Length L Ch R = 1 ,27489   ,484,484,484
BEGIN DESCRIPTION:
UNT 199 IN UKCR 53.0
END DESCRIPTION:
XS GIS Cut Line= 3
      3702049.61     10497210.23      3702099.61     10496710.19
      3702899.61     10495910.19
#Sta/Elev= 30
  4497.2  310.68  4527.4  307.21  4537.4  307.29  4557.5  302.96  4567.6  302.39
  4597.7  297.49  4657.2  291.15  4688.2  287.54  4708.3  282.47    4751  277.01
  4808.8   275.7    4859  271.43  4916.2  268.48  4979.6  268.93  4989.7  266.61
  4997.2  266.31  5013.9  268.09  5070.4   269.3  5155.3  266.96  5324.4  265.91
  5350.3  265.48    5353  264.98  5356.3  265.48  5508.9  265.98  5565.4  267.67
  5763.4  269.84  5834.1  272.95    6018  287.93  6046.3  288.87  6131.1  294.98
#Mann= 6 ,-1 , 0
  4497.2     .16       0  4657.2     .05       0  4916.2     .16       0
  5324.4     .05       0  5350.3     .07       0  5356.3     .16       0
Bank Sta=4979.6,5013.9
XS Rating Curve= 0 ,0
Exp/Cntr=0.3,0.1

Type RM Length L Ch R = 1 ,27005   ,411,411,411
BEGIN DESCRIPTION:
UNT 199 IN UKCR 52.0
END DESCRIPTION:
XS GIS Cut Line= 3
      3702199.63     10497410.15      3702549.61     10496710.19
       3702899.6     10496060.21
#Sta/Elev= 30
  4222.7  327.19  4289.7  317.97  4334.5  313.63  4342.8  311.31  4415.5  303.63
  4423.9  300.73  4460.2  297.83    4477   293.6  4521.7  289.11  4549.7  288.58
  4566.5  286.27    4572  283.73  4588.8  283.53  4633.5   277.9  4683.8  276.99
    4737  272.18  4863.9  267.06  4907.5  265.79  4982.9  267.67  4999.5  264.73
  5002.2  264.23  5005.5  264.73  5013.4  267.64  5115.1  266.65  5352.5  265.27
  5516.4  267.44  5554.3  269.58  5675.4  285.89  5698.1  290.85  5743.5  293.66
#Mann= 6 ,-1 , 0
  4222.7     .05       0  4863.9     .16       0  4999.5     .07       0
  5005.5     .16       0  5115.1     .05       0  5554.3     .16       0
Bank Sta=4982.9,5013.4
XS Rating Curve= 0 ,0
Exp/Cntr=0.3,0.1

Type RM Length L Ch R = 1 ,26594   ,481,481,481
BEGIN DESCRIPTION:
UNT 199 IN UKCR 51.0
END DESCRIPTION:
XS GIS Cut Line= 3
      3702599.61     10497210.19      3702899.61     10496910.19
      3703699.64     10496410.17
#Sta/Elev= 30
  4597.1  302.66  4710.2  289.87  4766.8  288.62  4823.4  279.64  4890.4  273.08
  4915.6  270.05  4964.8  265.67  4978.9  266.19  4990.1     261  4992.8   260.5
  4996.1     261  5007.2  261.89  5017.8  267.06  5065.6  263.52    5187  267.51
    5522  271.87  5695.3  276.63  5704.7  275.41  5710.6  272.14  5717.1  270.88
  5747.2   276.1  5753.1  275.59  5783.7  278.54  5826.2  280.01  5878.1  285.24
    5884  284.82  5935.9  291.36  5951.2  292.36  5957.1  291.53  5964.8  293.05
#Mann= 5 ,-1 , 0
  4597.1     .16       0  4890.4     .05       0  4915.6     .16       0
  4990.1     .07       0  4996.1     .16       0
Bank Sta=4978.9,5017.8
XS Rating Curve= 0 ,0
Exp/Cntr=0.3,0.1

Type RM Length L Ch R = 1 ,26113   ,340,340,340
BEGIN DESCRIPTION:
UNT 199 IN UKCR 50.0
END DESCRIPTION:
XS GIS Cut Line= 3
      3702699.62     10497560.18      3703099.61     10497310.19
      3703899.64     10496510.16
#Sta/Elev= 30
  4522.1  315.02  4675.4  305.41  4687.8  303.54    4834  292.75  4891.8  285.88
  4934.8  278.48  4964.9  269.77  4970.8  265.59  4980.2  263.33  4983.1  258.61
  4985.9  258.11  4989.1  258.61  4997.3  258.87  5007.9  263.08  5022.1  265.85
  5092.8  263.63  5106.9   264.3  5121.1  262.64  5135.2  265.14  5276.6   265.7
  5403.9  270.02  5526.5  269.54  5828.2  274.57  5941.3   283.6  5970.7   289.3
  5983.7  290.85  6040.3  302.34  6082.7  306.82    6111  307.77  6125.2  309.98
#Mann= 5 ,-1 , 0
  4522.1     .16       0  4983.1     .07       0  4989.1     .16       0
  5526.5     .05       0  5970.7     .16       0
Bank Sta=4970.8,5022.1
XS Rating Curve= 0 ,0
Exp/Cntr=0.3,0.1