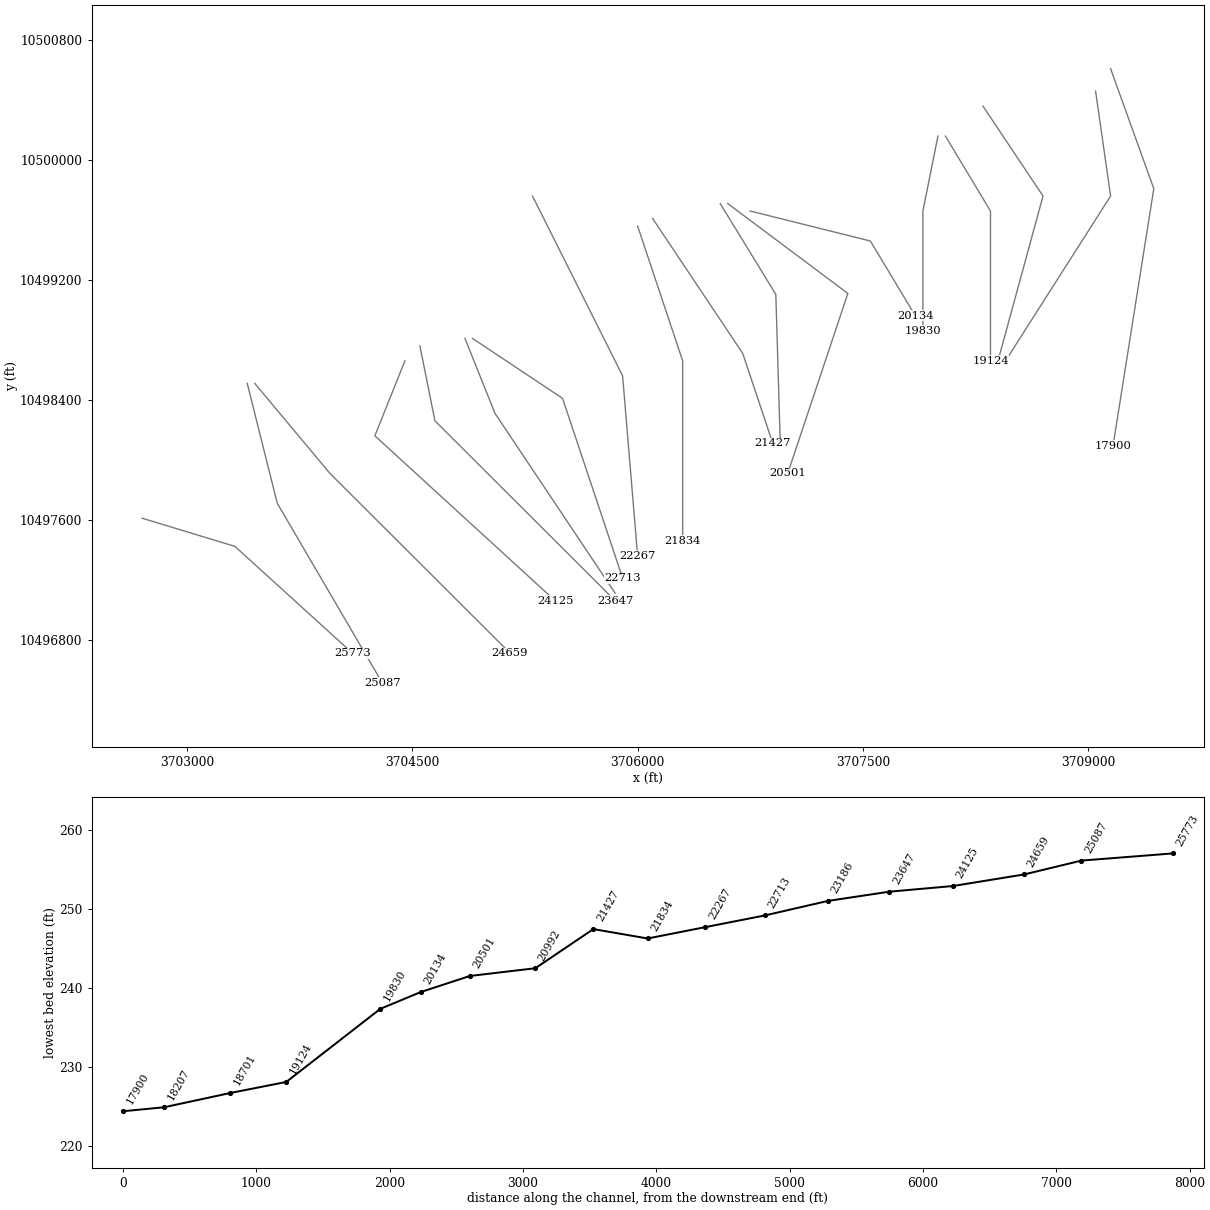
HEC-RAS study UNT 199 IN UKCR.prj: UNT 199 IN UKCR Base Level Engineering

--- UNT 199 IN UKCR.g01 (geometry) --- (continued)

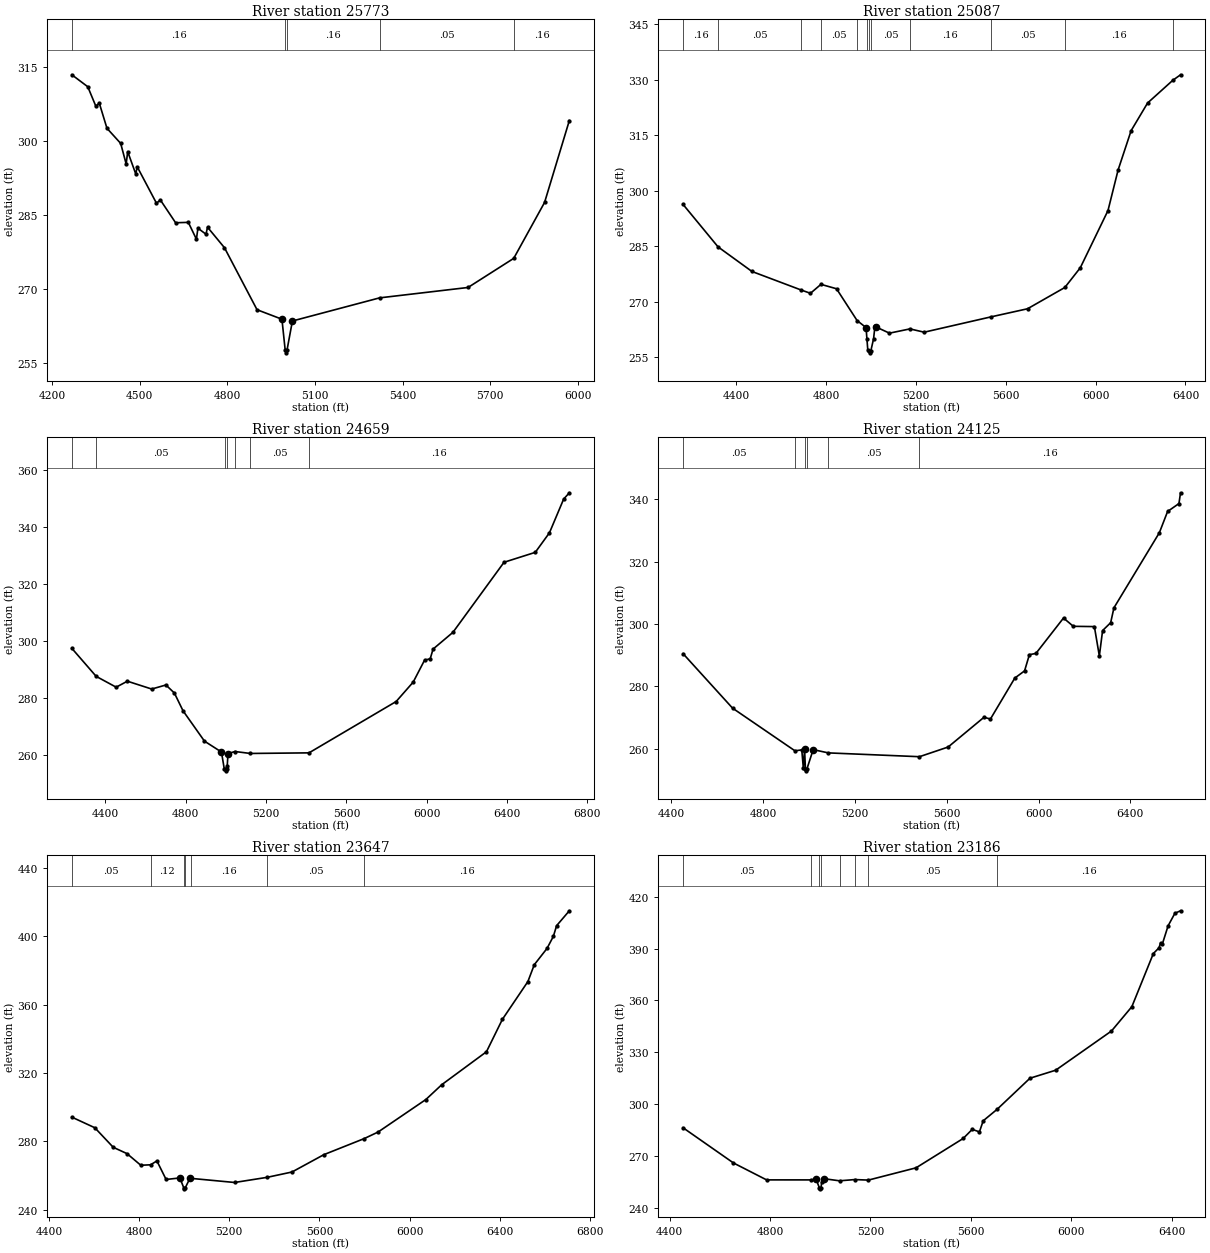
Type RM Length L Ch R = 1 ,25773   ,686,686,686
BEGIN DESCRIPTION:
UNT 199 IN UKCR 49.0
END DESCRIPTION:
XS GIS Cut Line= 3
      3702699.64     10497610.18      3703317.53      10497422.3
      3704099.58     10496710.21
#Sta/Elev= 30
  4267.6  313.33  4322.1  310.91  4349.7  306.98  4361.6  307.59  4387.8  302.51
  4434.8  299.45  4453.6  295.28  4458.8  297.79  4486.4  293.28  4491.6   294.7
  4557.4  287.35  4570.7  288.01  4622.9   283.4  4666.4  283.48  4694.1  280.08
  4699.3   282.3  4726.9  281.08  4732.2   282.5  4790.2  278.35  4901.7  265.81
    4987  263.89  4998.2  257.59  5000.9  257.09  5004.2  257.59  5022.8  263.53
  5321.5  268.21  5624.2  270.31  5780.7   276.2  5886.3  287.51  5971.1  304.07
#Mann= 5 ,-1 , 0
  4267.6     .16       0  4998.2     .07       0  5004.2     .16       0
  5321.5     .05       0  5780.7     .16       0
Bank Sta=4987,5022.8
XS Rating Curve= 0 ,0
Exp/Cntr=0.3,0.1

Type RM Length L Ch R = 1 ,25087   ,428,428,428
BEGIN DESCRIPTION:
UNT 199 IN UKCR 48.0
END DESCRIPTION:
XS GIS Cut Line= 3
      3703399.61     10498510.17      3703599.61     10497710.19
      3704299.58     10496510.23
#Sta/Elev= 30
  4164.2  296.29    4320  284.81  4470.8  278.17  4688.4  273.19  4731.1  272.27
  4777.8  274.69  4847.1   273.5  4938.6  264.91  4978.5  263.01  4982.5  259.88
  4986.2  256.99  4993.7  256.68  4996.4  256.18  4999.7  256.68    5012  259.99
  5018.2  263.41  5023.9  263.14  5082.7   261.5  5173.8  262.65  5237.3  261.76
    5533  265.88  5697.1  268.09    5863  273.84  5931.9  279.17  6055.1  294.63
  6100.2  305.61  6158.1  316.23  6231.3   323.7  6343.2  329.82    6378  331.33
#Mann= 12 ,-1 , 0
  4164.2     .16       0    4320     .05       0  4688.4     .16       0
  4777.8     .05       0  4938.6     .16       0  4982.5     .05       0
  4993.7     .03       0  4999.7     .05       0  5173.8     .16       0
    5533     .05       0    5863     .16       0  6343.2     .05       0
Bank Sta=4978.5,5023.9
XS Rating Curve= 0 ,0
Exp/Cntr=0.3,0.1

Type RM Length L Ch R = 1 ,24659   ,534,534,534
BEGIN DESCRIPTION:
UNT 199 IN UKCR 47.0
END DESCRIPTION:
XS GIS Cut Line= 3
       3703449.6      10498510.2      3703949.61     10497910.19
      3705149.61     10496710.19
#Sta/Elev= 30
  4232.5  297.42  4353.6  287.59  4453.2  283.79  4509.1  285.89  4630.2  283.14
  4701.1  284.56  4743.4  281.72  4786.4  275.49  4893.1  264.85  4977.7  261.03
  4992.1  254.96  4996.9  254.93  4999.6  254.43  5002.9  254.93  5006.4  256.03
  5010.3   260.5  5045.4  261.21  5121.6  260.53  5413.8  260.74  5847.9  278.76
  5932.8  285.57  5989.4  293.27  6017.6  293.76  6031.8  297.16  6130.8  303.04
  6385.3  327.63  6540.9  331.11  6611.6  337.98  6682.3  349.81  6710.6  352.02
#Mann= 7 ,-1 , 0
  4232.5     .16       0  4353.6     .05       0  4996.9     .03       0
  5002.9     .05       0  5045.4     .07       0  5121.6     .05       0
  5413.8     .16       0
Bank Sta=4977.7,5010.3
XS Rating Curve= 0 ,0
Exp/Cntr=0.3,0.1

Type RM Length L Ch R = 1 ,24125   ,478,478,478
BEGIN DESCRIPTION:
UNT 199 IN UKCR 46.0
END DESCRIPTION:
XS GIS Cut Line= 3
      3704449.63     10498660.23      3704249.61     10498160.19
      3705449.58     10497060.22
#Sta/Elev= 30
  4451.9  290.51  4667.4  273.05  4939.1  259.38  4968.9  259.67  4975.7  253.82
    4981  260.03  4984.8  253.46  4987.5  252.96  4990.8  253.46  5018.5  259.76
  5084.5  258.71  5481.3  257.49  5606.2  260.59  5762.2  270.11  5790.5  269.57
  5896.6  282.69  5939.1  284.99  5960.1  290.19  5988.5  290.58  6108.7  301.93
  6151.3  299.27  6243.1  299.18  6264.7  289.78  6278.9  297.91    6314  300.43
  6328.2  305.19  6526.2  329.28  6561.9  336.07  6611.3   338.6  6618.3  342.06
#Mann= 6 ,-1 , 0
  4451.9     .05       0  4939.1     .12       0  4984.8     .07       0
  4990.8     .12       0  5084.5     .05       0  5481.3     .16       0
Bank Sta=4981,5018.5
XS Rating Curve= 0 ,0
Exp/Cntr=0.3,0.1

Type RM Length L Ch R = 1 ,23647   ,461,461,461
BEGIN DESCRIPTION:
UNT 199 IN UKCR 45.0
END DESCRIPTION:
XS GIS Cut Line= 3
      3704549.62     10498760.16      3704649.61     10498260.19
      3705849.59     10497060.21
#Sta/Elev= 30
  4501.7  294.19  4603.6  287.98  4685.2  276.55  4746.4  272.84  4807.6  266.03
    4851  266.31    4879  268.58  4919.8  257.72    4981  258.62  4998.4  252.74
  5001.1  252.24  5004.4  252.74  5025.7  258.47  5028.8  258.38  5223.7  255.96
  5367.6  258.96  5478.3  262.09  5619.7  272.24  5798.6  281.64  5860.1  285.47
  6072.2   304.5  6142.9   313.2  6340.9  332.44  6411.6   351.4  6524.8  373.52
  6553.1  383.37  6609.6   392.9  6637.9  400.01  6652.1   406.2  6708.6  414.93
#Mann= 7 ,-1 , 0
  4501.7     .05       0    4851     .12       0  4998.4     .07       0
  5004.4     .12       0  5028.8     .16       0  5367.6     .05       0
  5798.6     .16       0
Bank Sta=4981,5025.7
XS Rating Curve= 0 ,0
Exp/Cntr=0.3,0.1

Type RM Length L Ch R = 1 ,23186   ,473,473,473
BEGIN DESCRIPTION:
UNT 199 IN UKCR 44.0
END DESCRIPTION:
XS GIS Cut Line= 3
      3704849.62     10498810.16      3705049.61     10498310.19
      3705849.61     10497110.19
#Sta/Elev= 30
  4453.8  286.39  4654.4  266.04  4786.3  256.25  4964.7  256.24  4982.9   256.8
  4996.8  251.57  4999.5  251.07  5002.8  251.57  5005.8  254.91  5014.8  256.94
  5076.8  255.71  5137.2  256.43  5191.7  256.13  5381.4  263.22  5569.2  280.21
  5605.2  285.47  5633.8  284.01  5648.8  290.42  5704.3  297.08  5835.1  315.05
  5937.2  319.67  6159.6  342.36  6240.7  356.43  6326.3  387.18  6348.9  390.49
  6354.9  393.34  6362.4  392.82  6384.9  403.17    6412  410.44  6434.5  411.89
#Mann= 8 ,-1 , 0
  4453.8     .05       0  4964.7     .16       0  4996.8     .07       0
  5002.8     .16       0  5076.8     .05       0  5137.2     .16       0
  5191.7     .05       0  5704.3     .16       0
Bank Sta=4982.9,5014.8
XS Rating Curve= 0 ,0
Exp/Cntr=0.3,0.1

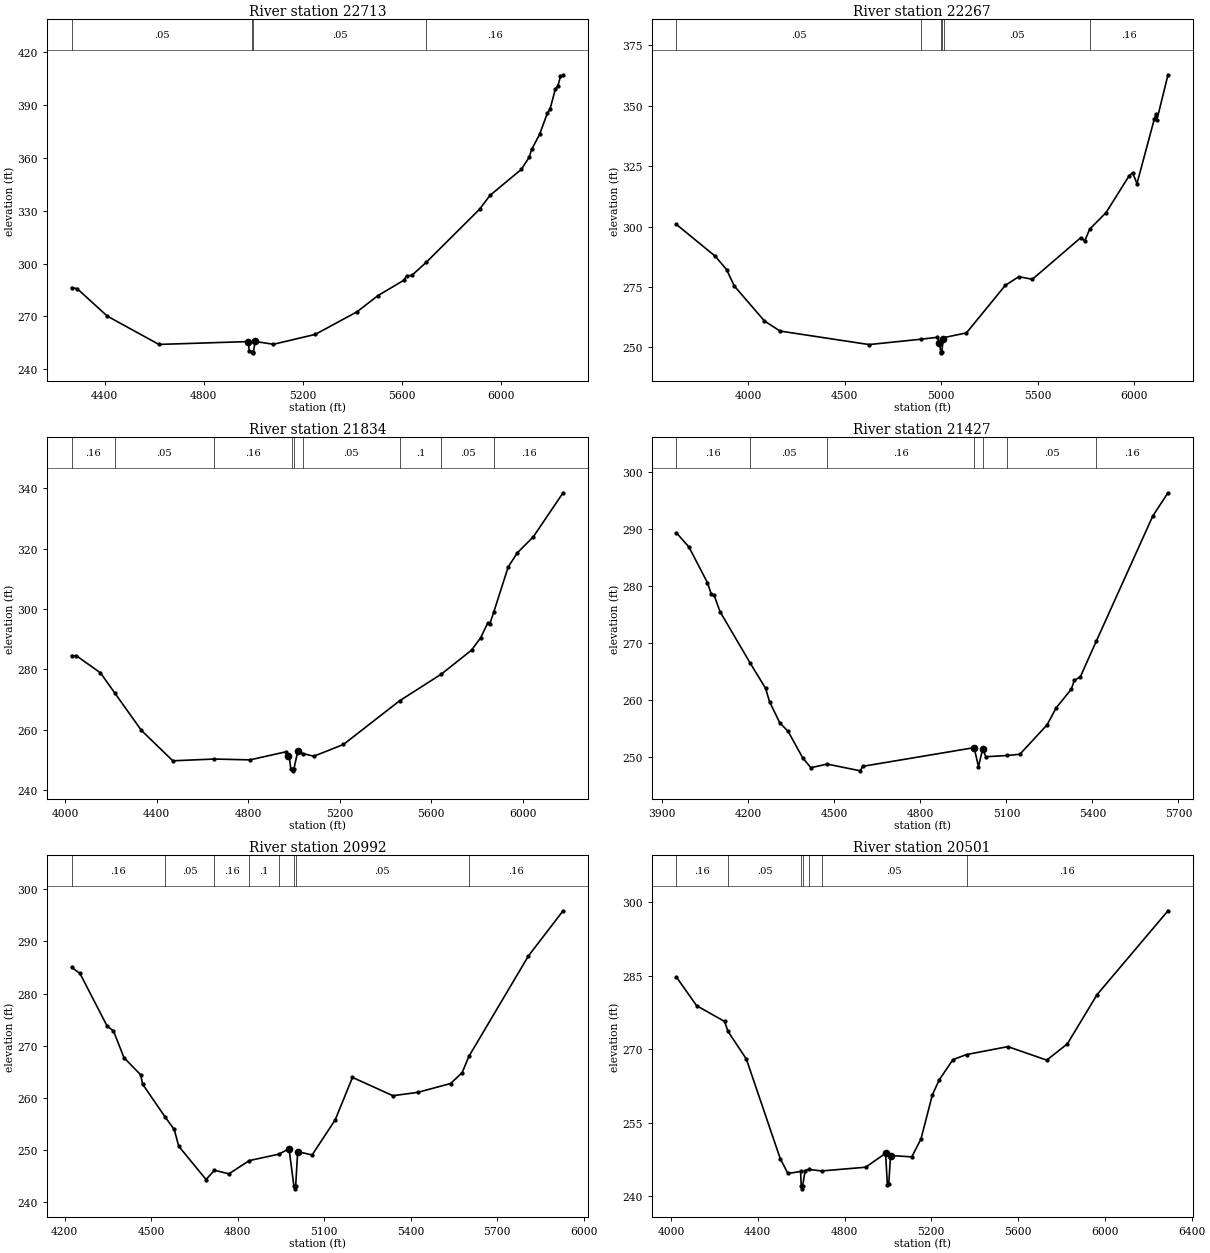
Type RM Length L Ch R = 1 ,22713   ,446,446,446
BEGIN DESCRIPTION:
UNT 199 IN UKCR 43.0
END DESCRIPTION:
XS GIS Cut Line= 3
      3704899.63     10498810.17      3705499.61     10498410.19
      3705899.61     10497210.18
#Sta/Elev= 30
  4266.7  286.32  4289.2  285.72  4410.9  270.12  4619.7  254.01  4980.3  255.63
  4984.8  250.51  4995.3  249.73  4998.1  249.23  5001.3  249.73  5008.9  255.69
  5082.6   254.1  5251.3  259.71    5420  272.54  5504.3  281.73  5609.7  290.53
  5620.2  292.97  5641.3  293.23  5700.3  300.75  5915.4  330.88  5957.5  338.75
    6084  353.51  6115.7  360.43  6126.2  365.01  6157.8  373.42  6189.4  385.57
    6200  387.79  6221.1  398.98  6231.6  400.93  6242.2  406.35  6252.7   407.3
#Mann= 4 ,-1 , 0
  4266.7     .05       0  4995.3     .03       0  5001.3     .05       0
  5700.3     .16       0
Bank Sta=4980.3,5008.9
XS Rating Curve= 0 ,0
Exp/Cntr=0.3,0.1

Type RM Length L Ch R = 1 ,22267   ,433,433,433
BEGIN DESCRIPTION:
UNT 199 IN UKCR 42.0
END DESCRIPTION:
XS GIS Cut Line= 3
      3705299.62     10499760.16      3705899.61     10498560.19
      3705999.61     10497360.15
#Sta/Elev= 30
  3629.4  300.87  3830.6  287.71  3889.3  282.18  3928.4  275.46    4085  260.95
    4166  256.76  4627.2  251.17  4894.2  253.38    4981  254.18  4991.1  251.86
  4998.1  248.25  5000.9  247.75  5004.1  248.25 5010.46  253.29    5015  254.06
  5131.6  256.02  5332.3  275.65  5402.5  279.27  5472.7  278.18  5723.6  295.41
  5743.7  294.05  5769.7  298.95  5854.1  305.73  5974.5  321.06    5992  322.25
  6014.6  317.78  6104.9  344.64  6112.4  346.55  6117.5  344.06  6175.2  362.81
#Mann= 6 ,-1 , 0
  3629.4     .05       0  4894.2     .16       0  4998.1     .07       0
  5004.1     .16       0    5015     .05       0  5769.7     .16       0
Bank Sta=4991.1,5010.46
XS Rating Curve= 0 ,0
Exp/Cntr=0.3,0.1

Type RM Length L Ch R = 1 ,21834   ,407,407,407
BEGIN DESCRIPTION:
UNT 199 IN UKCR 41.0
END DESCRIPTION:
XS GIS Cut Line= 3
      3705999.62     10499560.17      3706299.61     10498660.19
      3706299.61     10497460.15
#Sta/Elev= 30
    4028  284.51  4049.1  284.48  4154.5   278.8  4216.1  272.21  4333.7  259.69
  4470.7  249.64  4650.8  250.22    4808  249.95  4966.1  252.64    4974  251.08
  4979.2  251.08  4986.7  246.94  4993.7  246.81  4996.4  246.31  4999.7  246.81
  5016.7  252.75  5040.1  252.03  5086.7  251.15  5216.7  255.06  5462.2  269.55
  5644.9  278.41  5776.7  286.35  5816.7  290.48  5846.7  295.22  5856.7  295.11
  5873.9  299.01  5936.7  313.92  5976.7  318.61  6046.7  323.94  6176.7  338.53
#Mann= 9 ,-1 , 0
    4028     .16       0  4216.1     .05       0  4650.8     .16       0
  4993.7     .07       0  4999.7     .16       0  5040.1     .05       0
  5462.2      .1       0  5644.9     .05       0  5873.9     .16       0
Bank Sta=4974,5016.7
XS Rating Curve= 0 ,0
Exp/Cntr=0.3,0.1

Type RM Length L Ch R = 1 ,21427   ,435,435,435
BEGIN DESCRIPTION:
UNT 199 IN UKCR 40.0
END DESCRIPTION:
XS GIS Cut Line= 3
      3706099.59     10499610.21      3706699.61     10498710.19
      3706899.59     10498110.23
#Sta/Elev= 30
  3949.3  289.37  3992.9  286.87  4057.5  280.59    4071  278.53    4080  278.47
  4101.1  275.52  4206.7  266.43  4260.3     262  4273.8  259.67  4309.9  255.91
  4338.4  254.47  4389.5  249.79    4418  248.05  4474.7  248.69  4590.6   247.5
  4598.3  248.29  4987.4  251.58  5002.4  248.25  5017.5  251.38    5028  249.98
  5102.7   250.2  5146.9  250.42  5241.8  255.59  5273.4  258.58  5326.1  261.85
  5336.7   263.4  5357.8  264.05  5412.9  270.26  5610.7  292.36  5663.4  296.42
#Mann= 7 ,-1 , 0
  3949.3     .16       0  4206.7     .05       0  4474.7     .16       0
  4987.4     .07       0  5017.5     .16       0  5102.7     .05       0
  5412.9     .16       0
Bank Sta=4987.4,5017.5
XS Rating Curve= 0 ,0
Exp/Cntr=0.3,0.1

Type RM Length L Ch R = 1 ,20992   ,491,491,491
BEGIN DESCRIPTION:
UNT 199 IN UKCR 39.0
END DESCRIPTION:
XS GIS Cut Line= 3
      3706549.61     10499710.19      3706919.96     10499104.16
      3706949.61     10498110.23
#Sta/Elev= 30
  4224.1  285.05  4253.1  283.88    4348  273.71  4369.3  272.87    4406  267.69
  4464.1   264.4  4470.2  262.65  4548.7  256.32  4580.2  253.93  4595.7  250.72
  4690.5  244.33  4719.6   246.1  4769.9  245.42  4840.5  247.96    4943  249.19
  4978.3  250.24  4995.3  243.04  4998.1  242.54  5001.3  243.04  5008.3  249.68
  5058.4  249.04  5138.4  255.77  5198.4  263.92  5338.5  260.41  5424.6  261.05
  5538.6  262.75  5578.6  264.82    5602  267.95  5808.7  287.24  5928.7  295.89
#Mann= 8 ,-1 , 0
  4224.1     .16       0  4548.7     .05       0  4719.6     .16       0
  4840.5      .1       0    4943     .05       0  4995.3     .03       0
  5001.3     .05       0    5602     .16       0
Bank Sta=4978.3,5008.3
XS Rating Curve= 0 ,0
Exp/Cntr=0.3,0.1

Type RM Length L Ch R = 1 ,20501   ,367,367,367
BEGIN DESCRIPTION:
UNT 199 IN UKCR 38.0
END DESCRIPTION:
XS GIS Cut Line= 3
      3706599.59      10499710.2      3707399.61     10499110.19
      3706999.62     10497910.22
#Sta/Elev= 30
  4025.7  284.75  4118.4  278.93  4247.6   275.7  4262.8   273.7  4347.6  268.05
  4503.8  247.73  4539.3  244.69  4597.6   245.1  4600.8  242.06  4603.6  241.56
  4606.8  242.06  4618.4  245.29  4635.1  245.53  4694.2  245.21  4897.6  245.97
  4989.3  248.81  4997.6  242.35  5003.8  242.52  5012.2  248.36    5110  248.08
  5152.2   251.7  5204.9  260.74  5236.5  263.79  5299.8  267.92  5362.4  268.95
  5552.8  270.57    5732  267.81  5826.8  271.13  5963.9  281.18  6290.6  298.28
#Mann= 7 ,-1 , 0
  4025.7     .16       0  4262.8     .05       0  4600.8     .03       0
  4606.8     .05       0  4635.1     .16       0  4694.2     .05       0
  5362.4     .16       0
Bank Sta=4989.3,5012.2
XS Rating Curve= 0 ,0
Exp/Cntr=0.3,0.1

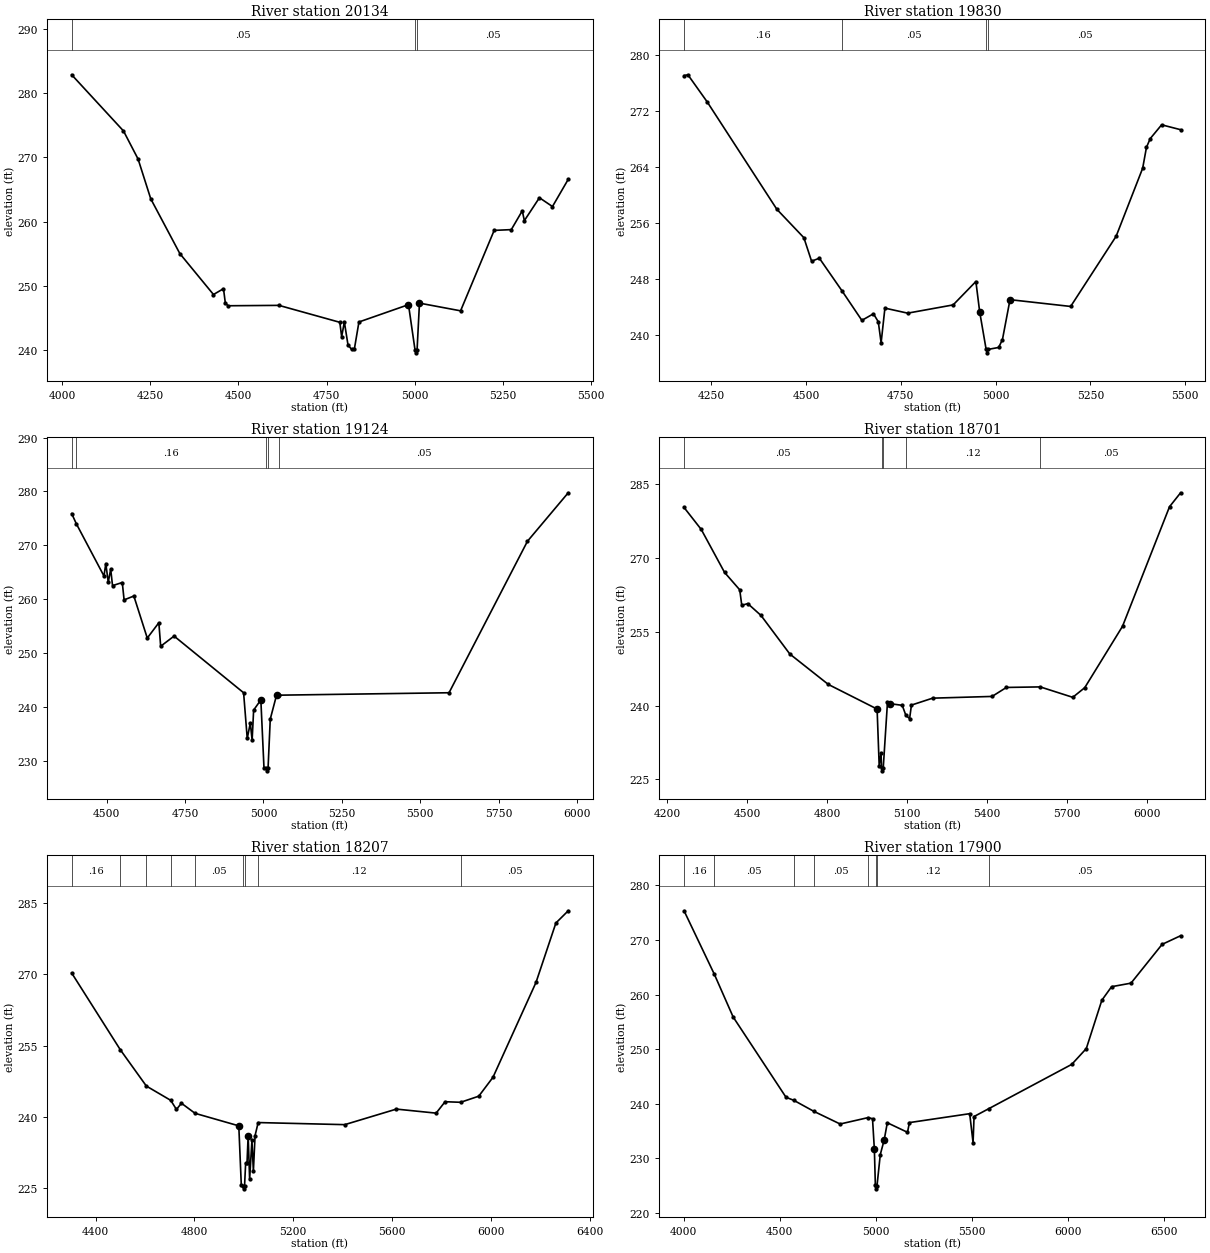
Type RM Length L Ch R = 1 ,20134   ,304,304,304
BEGIN DESCRIPTION:
UNT 199 IN UKCR 37.0
END DESCRIPTION:
XS GIS Cut Line= 3
      3706749.56      10499660.2      3707549.61     10499460.19
      3707849.63     10498960.16
#Sta/Elev= 30
  4027.4  282.88  4174.3  274.12  4215.6  269.75  4251.6  263.54  4334.1     255
  4429.4  248.62  4457.8  249.53    4463  247.31  4470.7  246.87    4615  246.93
  4787.6  244.29  4792.8  242.05  4800.5  244.34  4810.8  240.76  4821.1  240.06
  4828.9  240.14  4841.8  244.34  4982.3  247.04  5000.7  240.03  5003.4  239.53
  5006.7  240.03  5013.4  247.28    5130  246.08  5225.2  258.62  5273.8  258.74
  5304.9  261.67  5310.8  260.14  5353.5  263.71  5390.5  262.34  5435.2  266.58
#Mann= 3 ,-1 , 0
  4027.4     .05       0  5000.7     .03       0  5006.7     .05       0
Bank Sta=4982.3,5013.4
XS Rating Curve= 0 ,0
Exp/Cntr=0.3,0.1

Type RM Length L Ch R = 1 ,19830   ,706,706,706
BEGIN DESCRIPTION:
UNT 199 IN UKCR 36.0
END DESCRIPTION:
XS GIS Cut Line= 3
      3707999.61     10500160.19      3707899.61     10499660.19
      3707899.61      10498860.2
#Sta/Elev= 30
  4178.2  277.08  4188.4   277.2  4239.4  273.31    4423  257.95  4494.3  253.88
  4514.7  250.51  4535.1  250.95  4594.8  246.28  4647.3  242.05  4677.9  242.99
  4690.6  241.85  4698.1  238.84  4708.1   243.8  4768.1  243.08  4888.1  244.26
  4948.1  247.61  4958.1  243.27  4975.1   237.9  4977.9   237.4  4981.1   237.9
  5008.1  238.17  5018.1  239.28  5038.1  245.01  5198.1  244.04  5318.1  254.09
  5388.1  263.83  5398.1  266.82  5408.1  268.07  5438.1  270.04  5488.1  269.34
#Mann= 4 ,-1 , 0
  4178.2     .16       0  4594.8     .05       0  4975.1     .03       0
  4981.1     .05       0
Bank Sta=4958.1,5038.1
XS Rating Curve= 0 ,0
Exp/Cntr=0.3,0.1

Type RM Length L Ch R = 1 ,19124   ,423,423,423
BEGIN DESCRIPTION:
UNT 199 IN UKCR 35.0
END DESCRIPTION:
XS GIS Cut Line= 3
      3708049.63     10500160.16      3708349.61     10499660.19
      3708349.61     10498660.15
#Sta/Elev= 30
  4388.8   275.9  4403.5  274.02  4491.8   264.3  4497.6  266.62  4505.4  263.15
  4513.2  265.57    4519  262.52  4550.1   263.1  4555.9  259.87    4587  260.59
  4629.8  252.78  4666.7  255.63  4672.5  251.26  4715.3  253.15  4936.9  242.63
  4948.5  234.15  4958.3  236.99  4964.1  233.82  4968.9  239.41  4991.9   241.3
  5001.9  228.67  5008.9  228.63  5011.6  228.13  5014.9  228.63  5021.9  237.74
  5041.9  242.17  5050.6  242.18  5591.9  242.63  5841.9  270.76  5971.9  279.76
#Mann= 5 ,-1 , 0
  4388.8     .05       0  4403.5     .16       0  5008.9     .07       0
  5014.9     .16       0  5050.6     .05       0
Bank Sta=4991.9,5041.9
XS Rating Curve= 0 ,0
Exp/Cntr=0.3,0.1

Type RM Length L Ch R = 1 ,18701   ,494,494,494
BEGIN DESCRIPTION:
UNT 199 IN UKCR 34.0
END DESCRIPTION:
XS GIS Cut Line= 3
       3708299.6      10500360.2      3708699.61     10499760.19
      3708399.61     10498660.19
#Sta/Elev= 30
  4264.2  280.31  4328.8  275.83    4416   267.1    4473  263.55  4480.6   260.4
  4503.1  260.75  4552.7  258.34  4660.8  250.49  4805.1   244.3  4987.9  239.29
  4995.7  227.78  5002.6  230.32  5004.8  227.22  5007.5  226.72  5010.8  227.22
  5026.8  240.68  5037.2  240.38  5082.1  240.05  5095.6  238.03  5109.7  237.34
  5116.6   240.1  5196.1  241.51  5418.9  241.86  5472.5  243.69  5599.4   243.8
  5721.3  241.68  5766.2  243.64  5907.8  256.13    6084  280.46  6125.5   283.3
#Mann= 5 ,-1 , 0
  4264.2     .05       0  5004.8     .03       0  5010.8     .05       0
  5095.6     .12       0  5599.4     .05       0
Bank Sta=4987.9,5037.2
XS Rating Curve= 0 ,0
Exp/Cntr=0.3,0.1

Type RM Length L Ch R = 1 ,18207   ,307,307,307
BEGIN DESCRIPTION:
UNT 199 IN UKCR 33.0
END DESCRIPTION:
XS GIS Cut Line= 3
      3709049.61     10500460.19      3709149.61     10499760.19
      3708449.58     10498660.15
#Sta/Elev= 30
  4302.8  270.28  4499.5  254.17  4605.3  246.52  4703.9  243.52  4727.1  241.61
  4747.3  242.91  4802.5  240.79  4979.6  238.16  4989.7  225.76  4996.8  225.42
  4999.6  224.92  5002.8  225.42  5007.4  230.36  5012.9  230.36  5017.5  236.12
  5023.5  226.93  5032.8   235.1  5038.7  228.65  5045.5  236.11    5058  238.85
  5408.7  238.41  5617.8  241.68  5778.7  240.83  5815.1  243.23    5878  243.11
  5951.4  244.39    6009  248.36  6183.4  268.32  6263.8  280.79  6313.8  283.36
#Mann= 9 ,-1 , 0
  4302.8     .16       0  4499.5     .05       0  4605.3     .16       0
  4703.9     .08       0  4802.5     .05       0  4996.8     .03       0
  5002.8     .05       0    5058     .12       0    5878     .05       0
Bank Sta=4979.6,5017.5
XS Rating Curve= 0 ,0
Exp/Cntr=0.3,0.1

Type RM Length L Ch R = 1 ,17900   ,765,765,765
BEGIN DESCRIPTION:
UNT 199 IN UKCR 32.0
END DESCRIPTION:
XS GIS Cut Line= 3
       3709149.6     10500610.22      3709437.32     10499809.45
      3709166.06     10498095.07
#Sta/Elev= 30
    4002  275.33  4159.8  263.71  4257.9  255.88  4533.3  241.18  4573.6  240.63
  4676.5  238.64  4815.1  236.29  4960.7  237.46  4983.8  237.26  4993.5  231.63
  4998.6  225.13    5001  224.92  5003.8  224.42    5007  224.92  5024.3   230.7
  5044.5  233.36  5060.9  236.52    5166  234.77  5176.1  236.55    5490  238.18
  5507.6  232.87  5512.7  237.66  5590.7  239.12  6021.7  247.21  6097.4   250.1
  6178.4  258.95  6229.1  261.43  6330.3  262.08  6492.3  269.18  6588.6  270.76
#Mann= 8 ,-1 , 0
    4002     .16       0  4159.8     .05       0  4573.6     .08       0
  4676.5     .05       0  4960.7     .12       0    5001     .07       0
    5007     .12       0  5590.7     .05       0
Bank Sta=4993.5,5044.5
XS Rating Curve= 0 ,0
Exp/Cntr=0.3,0.1