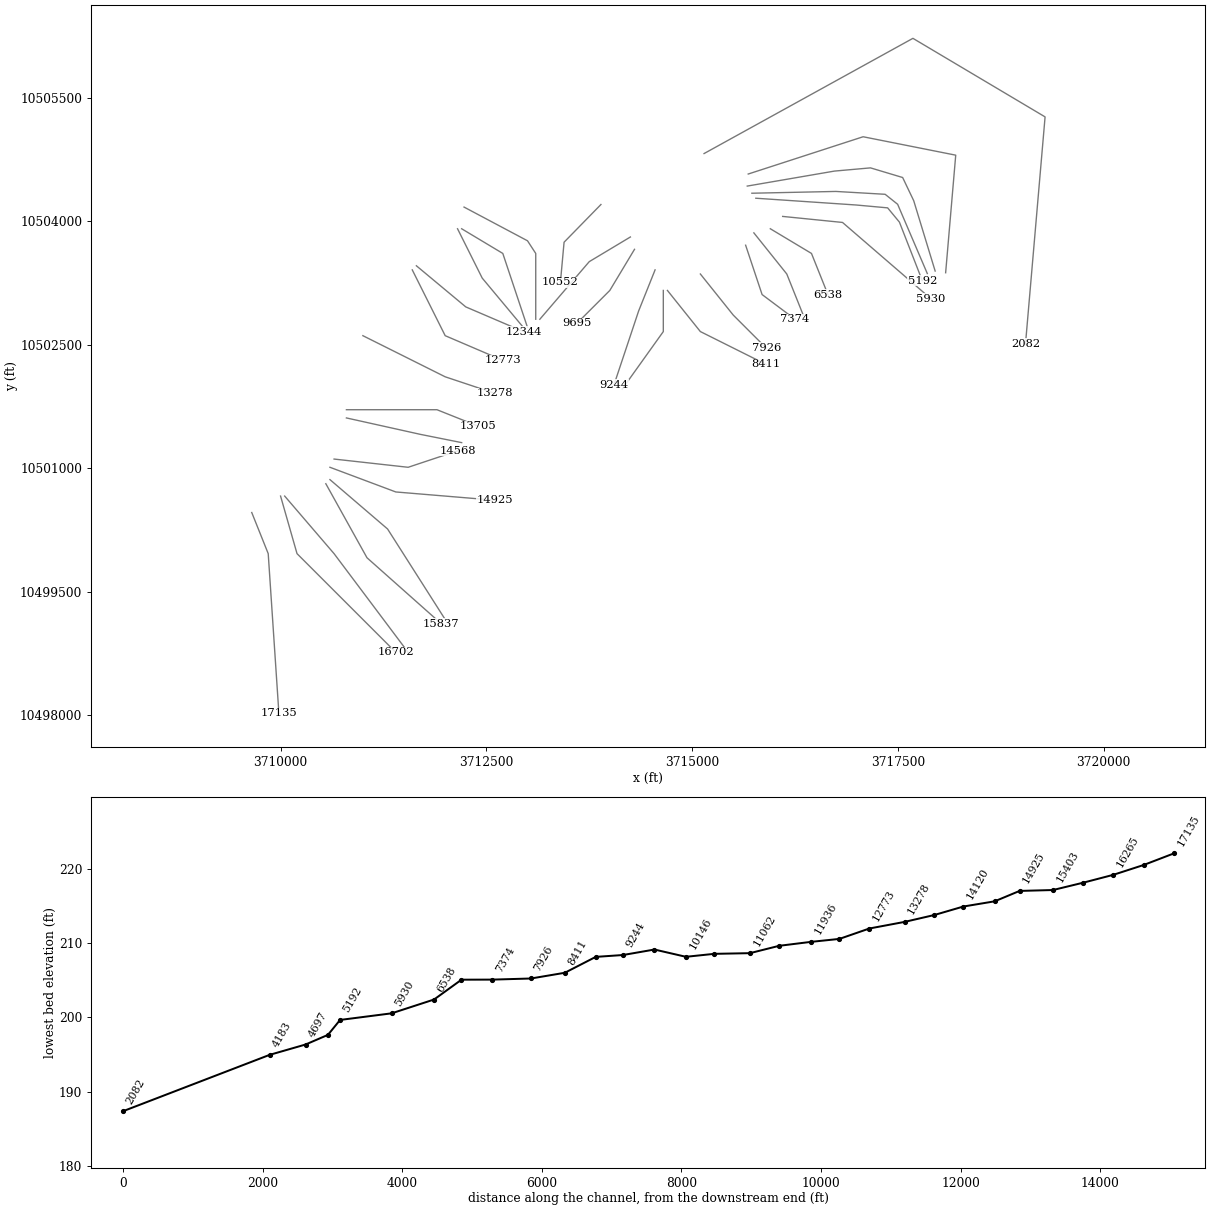
HEC-RAS study UNT 199 IN UKCR.prj: UNT 199 IN UKCR Base Level Engineering

--- UNT 199 IN UKCR.g01 (geometry) --- (continued)

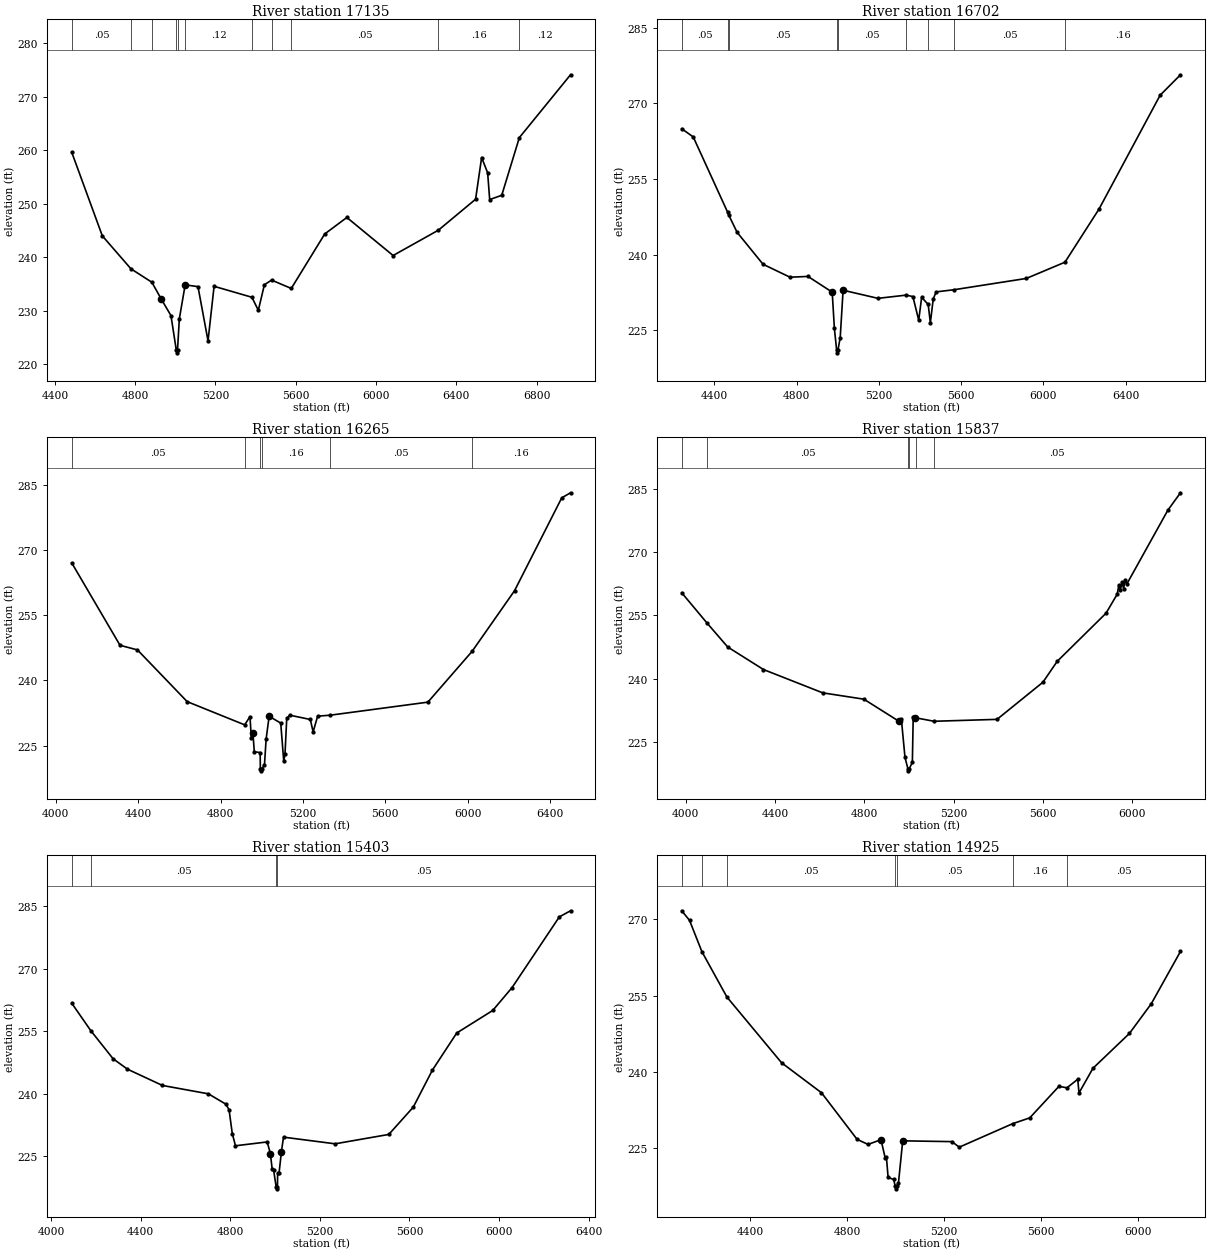
Type RM Length L Ch R = 1 ,17135   ,433,433,433
BEGIN DESCRIPTION:
UNT 199 IN UKCR 31.0
END DESCRIPTION:
XS GIS Cut Line= 3
       3709649.6      10500460.2      3709849.61     10499960.19
      3709979.37     10498018.25
#Sta/Elev= 30
  4484.4  259.58  4636.5  243.97  4779.2   237.8  4883.3  235.29    4930  232.15
  4978.5  229.05  5005.1  222.58  5007.9  222.08  5011.1  222.58  5020.2  228.43
  5049.2   234.8  5113.1  234.47  5163.2  224.32  5193.3  234.53  5381.7  232.48
  5413.8  230.04  5443.9  234.82  5479.8  235.69  5577.9  234.13  5744.5  244.32
  5854.8  247.41  6085.3  240.29  6310.8  245.03  6496.2  250.82  6526.3  258.63
  6556.3  255.76  6566.4  250.76  6626.5  251.56  6714.2  262.35  6969.2  274.11
#Mann= 11 ,-1 , 0
  4484.4     .05       0  4779.2     .08       0  4883.3     .05       0
  5005.1     .03       0  5011.1     .05       0  5049.2     .12       0
  5381.7     .05       0  5479.8     .08       0  5577.9     .05       0
  6310.8     .16       0  6714.2     .12       0
Bank Sta=4930,5049.2
XS Rating Curve= 0 ,0
Exp/Cntr=0.3,0.1

Type RM Length L Ch R = 1 ,16702   ,437,437,437
BEGIN DESCRIPTION:
UNT 199 IN UKCR 30.0
END DESCRIPTION:
XS GIS Cut Line= 3
       3709999.6     10500660.23      3710199.61     10499960.19
       3711399.6      10498760.2
#Sta/Elev= 30
  4241.6  264.97  4297.5  263.35  4465.3  248.36    4469  247.95  4510.7  244.43
  4636.9  238.09  4768.2  235.52  4855.3  235.68  4973.2  232.56  4983.8  225.37
  4994.9  221.02  4997.7  220.52  5000.9  221.02  5012.1  223.52  5026.2  232.94
  5195.9  231.33  5332.8  231.97  5365.6  231.68  5393.9  226.99  5408.1  231.53
  5439.9  230.12  5450.5  226.49  5464.6  231.24  5478.8  232.61  5567.4  233.05
  5917.2  235.28    6105   238.5  6270.7  249.05  6567.7  271.62  6666.7  275.68
#Mann= 9 ,-1 , 0
  4241.6     .05       0  4465.3     .08       0    4469     .05       0
  4994.9     .03       0  5000.9     .05       0  5332.8     .12       0
  5439.9     .16       0  5567.4     .05       0    6105     .16       0
Bank Sta=4973.2,5026.2
XS Rating Curve= 0 ,0
Exp/Cntr=0.3,0.1

Type RM Length L Ch R = 1 ,16265   ,428,428,428
BEGIN DESCRIPTION:
UNT 199 IN UKCR 29.0
END DESCRIPTION:
XS GIS Cut Line= 3
       3710049.6      10500660.2      3710649.61     10499960.19
      3711549.63     10498760.16
#Sta/Elev= 30
  4077.8  267.06  4312.1   248.1  4396.7  247.04  4638.1  235.13  4917.4  229.78
  4943.2  231.68  4949.8  226.68  4957.5  227.92  4964.1  223.59  4992.6  223.39
  4993.5  219.69  4996.2  219.19  4999.5  219.69  5013.3  220.42  5021.6  226.53
  5036.2  231.76  5092.5  230.18  5107.1   221.4  5113.3  223.12  5121.6  231.25
  5136.2  232.01  5236.2  231.02  5249.8  228.15  5271.6  231.78  5331.9     232
  5807.1  235.01    6022  246.72  6227.9  260.67  6457.1  282.06  6499.8  283.23
#Mann= 6 ,-1 , 0
  4077.8     .05       0  4917.4     .16       0  4993.5     .07       0
  4999.5     .16       0  5331.9     .05       0    6022     .16       0
Bank Sta=4957.5,5036.2
XS Rating Curve= 0 ,0
Exp/Cntr=0.3,0.1

Type RM Length L Ch R = 1 ,15837   ,434,434,434
BEGIN DESCRIPTION:
UNT 199 IN UKCR 28.0
END DESCRIPTION:
XS GIS Cut Line= 3
      3710549.59     10500810.22      3711049.61     10499910.19
      3711949.64     10499110.16
#Sta/Elev= 30
  3982.6  260.38  4097.4   253.1  4188.6  247.51  4348.7  242.17  4614.1  236.64
  4798.3  235.14    4955  229.91  4966.4  230.32  4982.5  221.33  4995.5  218.64
  4998.2  218.14  5001.5  218.64  5015.5  220.15  5019.3  230.86    5026  230.61
  5031.2  230.71  5112.5   229.9  5394.8  230.35  5600.5  239.17    5664   244.1
  5883.1  255.54  5933.3  260.07    5940  262.18  5947.5  261.05  5954.2   262.9
  5961.7  261.36  5968.4  263.43  5975.5   262.4  6159.9  279.97  6216.4   284.1
#Mann= 6 ,-1 , 0
  3982.6     .16       0  4097.4     .05       0  4995.5     .03       0
  5001.5     .05       0  5031.2     .16       0  5112.5     .05       0
Bank Sta=4955,5026
XS Rating Curve= 0 ,0
Exp/Cntr=0.3,0.1

Type RM Length L Ch R = 1 ,15403   ,478,478,478
BEGIN DESCRIPTION:
UNT 199 IN UKCR 27.0
END DESCRIPTION:
XS GIS Cut Line= 3
      3710599.57     10500860.22      3711299.61     10500260.19
      3711999.59     10499160.22
#Sta/Elev= 30
  4092.9  261.66  4177.6   255.1  4277.3  248.35  4341.5  245.85  4497.4  241.95
  4702.6  239.94  4780.6  237.46  4794.8  236.11  4809.1  230.42  4823.4  227.48
    4965   228.4  4979.2  225.59  4986.9  222.01  4993.5  221.72  5004.8  217.65
  5007.5  217.15  5010.8  217.65  5011.6  220.92  5017.9  220.92  5028.4  226.06
  5037.8  229.55    5268  227.95  5507.7   230.2  5616.9  236.75  5702.4  245.64
  5810.8  254.53  5971.6  259.94    6058  265.44  6268.8  282.39  6318.7  283.85
#Mann= 4 ,-1 , 0
  4092.9     .16       0  4177.6     .05       0  5004.8     .03       0
  5010.8     .05       0
Bank Sta=4979.2,5028.4
XS Rating Curve= 0 ,0
Exp/Cntr=0.3,0.1

Type RM Length L Ch R = 1 ,14925   ,357,357,357
BEGIN DESCRIPTION:
UNT 199 IN UKCR 26.0
END DESCRIPTION:
XS GIS Cut Line= 3
      3710599.57      10501010.2      3711399.61     10500710.19
      3712599.61     10500610.19
#Sta/Elev= 30
  4118.3  271.64  4150.4  269.76  4201.5  263.61  4304.6  254.71  4530.4  241.79
  4695.1   235.9  4841.9  226.76  4887.3  225.75  4940.7  226.69  4957.6  223.18
    4963  223.35  4970.1  219.27  4992.8  218.87  4999.8  217.53  5002.6  217.03
  5005.8  217.53  5012.9  218.22  5030.4  226.46  5233.6   226.3  5263.7  225.21
  5483.9  229.82  5554.8  230.97  5675.2  237.16  5708.2  236.87  5752.9  238.55
    5758  235.86  5815.7  240.71  5966.2  247.55  6056.5  253.39  6176.9  263.65
#Mann= 7 ,-1 , 0
  4118.3     .05       0  4201.5     .16       0  4304.6     .05       0
  4999.8     .03       0  5005.8     .05       0  5483.9     .16       0
  5708.2     .05       0
Bank Sta=4940.7,5030.4
XS Rating Curve= 0 ,0
Exp/Cntr=0.3,0.1

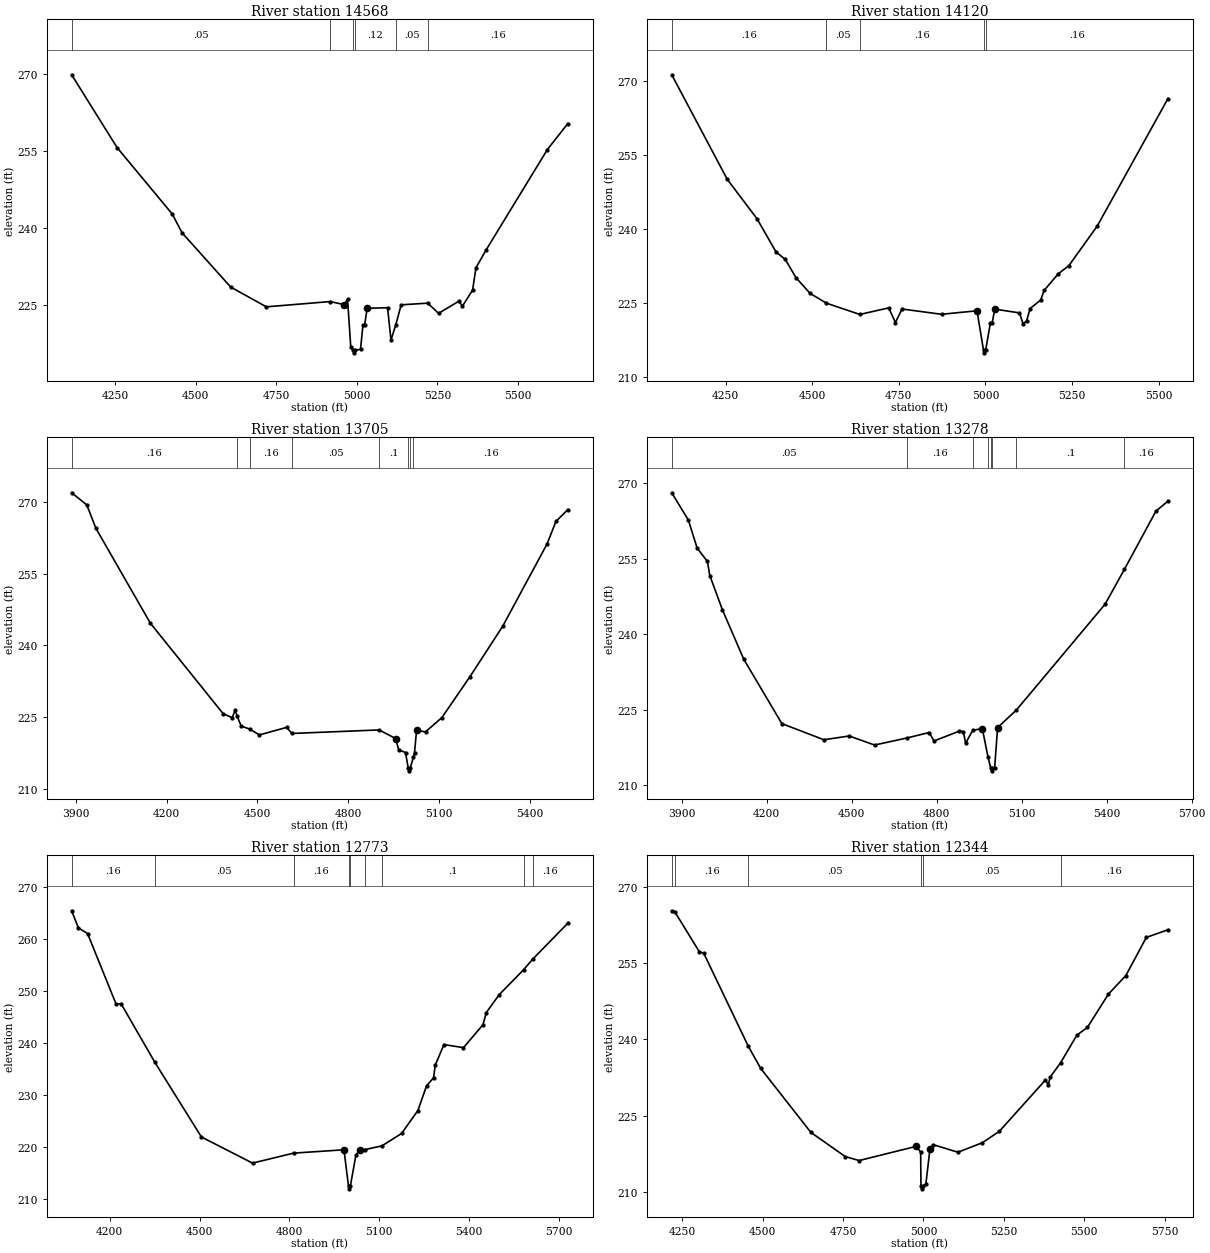
Type RM Length L Ch R = 1 ,14568   ,448,448,448
BEGIN DESCRIPTION:
UNT 199 IN UKCR 25.0
END DESCRIPTION:
XS GIS Cut Line= 3
      3710649.66     10501110.18      3711549.61     10501010.19
      3712149.57     10501210.17
#Sta/Elev= 30
    4116  269.79  4256.8  255.61  4427.9  242.66    4458  239.03    4609  228.44
  4719.6  224.59  4917.7  225.62  4961.1  225.01  4971.2  226.08  4981.2  216.77
  4988.3  216.13  4991.1  215.63  4994.3  216.13  5011.4  216.31    5019  221.04
  5024.1  221.04    5032  224.32  5095.3  224.41  5105.8  218.12  5120.3  220.98
  5137.4  224.98  5219.8  225.31  5253.4  223.33  5316.6  225.69  5327.2  224.71
  5358.8  227.84  5369.3  232.21    5401   235.7  5590.7  255.23  5653.9  260.28
#Mann= 6 ,-1 , 0
    4116     .05       0  4917.7     .12       0  4988.3     .07       0
  4994.3     .12       0  5120.3     .05       0  5219.8     .16       0
Bank Sta=4961.1,5032
XS Rating Curve= 0 ,0
Exp/Cntr=0.3,0.1

Type RM Length L Ch R = 1 ,14120   ,415,415,415
BEGIN DESCRIPTION:
UNT 199 IN UKCR 24.0
END DESCRIPTION:
XS GIS Cut Line= 3
       3710799.6     10501610.19      3711699.61     10501410.19
      3712199.64     10501310.18
#Sta/Elev= 30
  4094.7  271.33  4254.8  250.13  4340.6  242.14  4395.6   235.4  4422.5  233.87
  4453.2  230.18  4494.2  226.97  4541.2     225  4637.4  222.72  4720.9  224.05
  4740.1  221.08  4759.3  223.82  4873.3  222.75  4975.7  223.46  4994.5  215.43
  4997.2  214.93  5000.5  215.43  5014.1   220.9  5019.2   220.9  5026.9   223.8
  5098.3  223.03  5108.4  220.86  5118.6  221.34  5128.8  223.91  5159.4  225.64
  5169.6  227.61  5210.4  230.97    5241  232.63  5322.6  240.64  5526.6  266.48
#Mann= 5 ,-1 , 0
  4094.7     .16       0  4541.2     .05       0  4637.4     .16       0
  4994.5     .07       0  5000.5     .16       0
Bank Sta=4975.7,5026.9
XS Rating Curve= 0 ,0
Exp/Cntr=0.3,0.1

Type RM Length L Ch R = 1 ,13705   ,427,427,427
BEGIN DESCRIPTION:
UNT 199 IN UKCR 23.0
END DESCRIPTION:
XS GIS Cut Line= 3
      3710799.65     10501710.19      3711899.61     10501710.19
      3712399.63     10501510.18
#Sta/Elev= 30
  3886.4   271.9  3936.4  269.37  3966.4  264.48  4146.4  244.64  4386.4  225.76
  4416.4  224.89  4426.4  226.46  4432.8  225.25  4446.4  223.14  4474.4  222.52
  4506.4   221.3  4596.4  222.87  4613.8   221.6    4902  222.34  4956.4  220.54
  4966.4   218.2    4989  217.61  4998.2  214.29  5000.9  213.79  5004.2  214.29
  5015.1  216.65  5018.7  217.54  5025.4  222.23    5055  221.94  5108.9   224.9
  5201.8  233.47  5309.5  243.96  5456.2  261.17  5485.8  265.92  5524.9  268.38
#Mann= 8 ,-1 , 0
  3886.4     .16       0  4432.8     .05       0  4474.4     .16       0
  4613.8     .05       0    4902      .1       0  4998.2     .07       0
  5004.2      .1       0  5015.1     .16       0
Bank Sta=4956.4,5025.4
XS Rating Curve= 0 ,0
Exp/Cntr=0.3,0.1

Type RM Length L Ch R = 1 ,13278   ,505,505,505
BEGIN DESCRIPTION:
UNT 199 IN UKCR 22.0
END DESCRIPTION:
XS GIS Cut Line= 3
      3710999.59      10502610.2      3711999.61     10502110.19
       3712599.6     10501910.19
#Sta/Elev= 30
  3865.6  268.15  3924.3  262.71  3955.1  257.15  3991.4  254.49  3999.8   251.7
  4044.5  244.85    4120  235.01  4254.1  222.25  4402.3  219.04  4491.7  219.79
  4581.2  217.99  4694.1  219.38    4774  220.48  4790.8   218.8  4880.2  220.75
  4894.2  220.65  4902.6  218.33  4927.1   220.9  4961.3  221.27  4981.3  215.65
  4991.2  213.36  4993.9  212.86  4997.2  213.36  5004.7   213.4  5015.3  221.46
  5081.6  224.95  5394.7  246.01  5462.5  252.91  5573.9   264.5  5616.1  266.48
#Mann= 8 ,-1 , 0
  3865.6     .05       0  4694.1     .16       0  4927.1      .1       0
  4981.3     .05       0  4991.2     .03       0  4997.2     .05       0
  5081.6      .1       0  5462.5     .16       0
Bank Sta=4961.3,5015.3
XS Rating Curve= 0 ,0
Exp/Cntr=0.3,0.1

Type RM Length L Ch R = 1 ,12773   ,429,429,429
BEGIN DESCRIPTION:
UNT 199 IN UKCR 21.0
END DESCRIPTION:
XS GIS Cut Line= 3
      3711599.61      10503410.2      3711999.61     10502610.19
       3712699.6     10502310.19
#Sta/Elev= 30
  4073.2  265.38  4095.6  262.09  4126.3  261.01  4221.3  247.48  4238.1  247.53
  4350.6   236.3  4506.4  221.93  4676.9  216.91  4813.8  218.83  4982.1  219.47
  4997.3  212.47    5000  211.97  5003.3  212.47    5022  218.44  5034.7  219.51
  5053.3  219.52  5109.1  220.23  5174.3   222.6  5228.7  226.99  5257.8  231.75
  5281.3  233.31  5286.8  235.72  5315.8  239.68  5381.1  239.09  5446.3  243.51
  5457.2  245.84  5500.7  249.29  5581.6  254.05  5611.5  256.05  5729.2  262.99
#Mann= 9 ,-1 , 0
  4073.2     .16       0  4350.6     .05       0  4813.8     .16       0
  4997.3     .07       0  5003.3     .16       0  5053.3     .05       0
  5109.1      .1       0  5581.6     .05       0  5611.5     .16       0
Bank Sta=4982.1,5034.7
XS Rating Curve= 0 ,0
Exp/Cntr=0.3,0.1

Type RM Length L Ch R = 1 ,12344   ,408,408,408
BEGIN DESCRIPTION:
UNT 199 IN UKCR 20.0
END DESCRIPTION:
XS GIS Cut Line= 3
      3711649.62     10503460.18      3712249.61     10502960.19
      3712949.61     10502660.19
#Sta/Elev= 30
  4217.5  265.33  4226.5  265.18  4302.8   257.3  4317.1  256.95  4455.3  238.67
  4494.1  234.28  4650.3  221.67  4757.1  216.92    4800  216.14    4977  218.93
  4991.4  217.83  4992.3  211.07    4995  210.57  4998.3  211.07  5007.6  211.51
  5020.3  218.43  5031.2  219.25  5107.3  217.78  5183.5  219.66  5236.1   221.9
  5379.3     232  5388.4  231.04  5393.8  232.55  5426.4  235.39  5477.2  240.84
  5509.9  242.36  5575.1  248.91  5629.5  252.58    5693  260.08  5760.1  261.59
#Mann= 6 ,-1 , 0
  4217.5     .05       0  4226.5     .16       0  4455.3     .05       0
  4992.3     .03       0  4998.3     .05       0  5426.4     .16       0
Bank Sta=4977,5020.3
XS Rating Curve= 0 ,0
Exp/Cntr=0.3,0.1

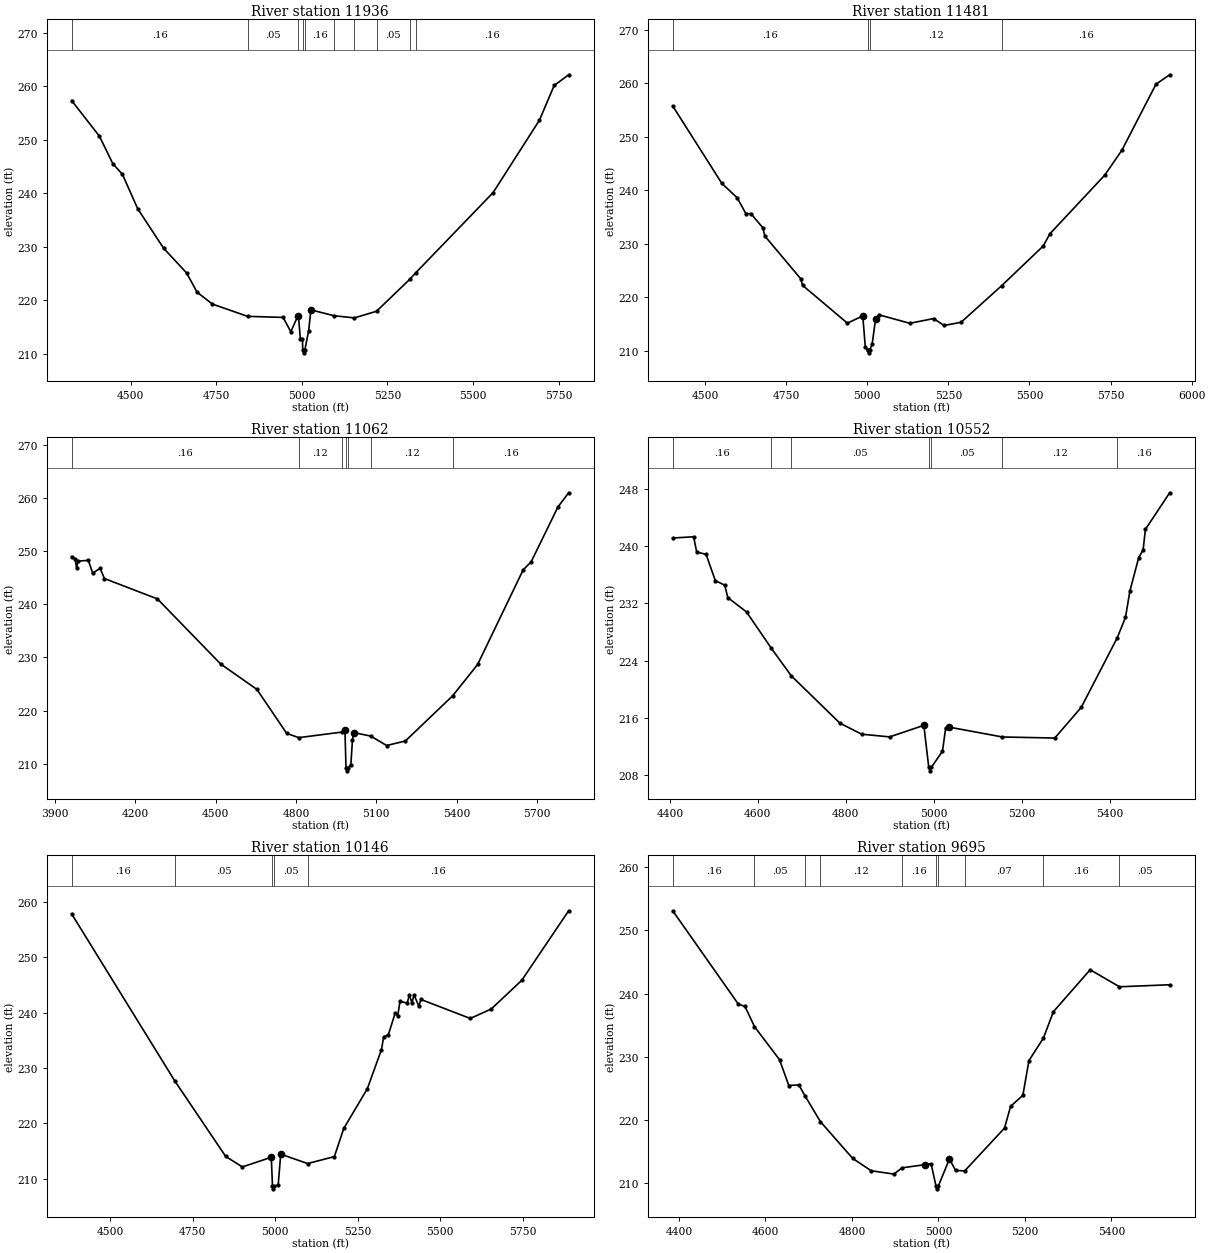
Type RM Length L Ch R = 1 ,11936   ,455,455,455
BEGIN DESCRIPTION:
UNT 199 IN UKCR 19.0
END DESCRIPTION:
XS GIS Cut Line= 3
      3712149.61     10503910.18      3712449.61     10503310.19
      3712949.58     10502710.22
#Sta/Elev= 30
  4327.7   257.3  4408.8  250.64  4447.9  245.51  4475.8  243.54  4520.6  237.09
    4596  229.73  4663.1  225.12  4693.9  221.51  4738.6  219.29  4841.3  216.99
  4945.4  216.79  4967.8  214.11  4988.4  217.06  4990.1  217.01  4995.7   212.8
  5001.8   212.8  5002.7  210.67  5005.4  210.17  5008.7  210.67    5020  214.33
  5026.5   218.2  5094.4   217.1  5153.6   216.7  5218.2  217.94  5315.6  223.93
  5332.1  225.08  5558.9  240.12  5694.3  253.66  5737.2  260.13  5779.5  262.13
#Mann= 10 ,-1 , 0
  4327.7     .16       0  4841.3     .05       0  4988.4     .16       0
  5002.7     .07       0  5008.7     .16       0  5094.4     .05       0
  5153.6     .16       0  5218.2     .05       0  5315.6     .12       0
  5332.1     .16       0
Bank Sta=4990.1,5026.5
XS Rating Curve= 0 ,0
Exp/Cntr=0.3,0.1

Type RM Length L Ch R = 1 ,11481   ,419,419,419
BEGIN DESCRIPTION:
UNT 199 IN UKCR 18.0
END DESCRIPTION:
XS GIS Cut Line= 3
      3712199.58     10503910.21      3712699.61     10503610.19
       3712999.6      10502710.2
#Sta/Elev= 30
  4400.4  255.78    4552  241.29  4598.7  238.65  4625.9  235.67  4641.5  235.65
  4678.4     233  4684.2  231.48    4795  223.48  4800.8  222.25  4938.8  215.19
  4986.2  216.54  4994.1  210.69  5001.5  210.15  5001.6  210.14  5004.4  209.64
  5007.6  210.14  5015.2  211.29  5025.7  215.98  5036.2  216.75  5131.1  215.16
  5204.9  216.05  5236.5  214.75  5289.2  215.35  5414.5   222.2  5542.2  229.59
  5563.3  231.91  5731.9  242.84  5784.6  247.48  5890.1  259.85  5932.2  261.61
#Mann= 5 ,-1 , 0
  4400.4     .16       0  5001.5     .12       0  5001.6     .07       0
  5007.6     .12       0  5414.5     .16       0
Bank Sta=4986.2,5025.7
XS Rating Curve= 0 ,0
Exp/Cntr=0.3,0.1

Type RM Length L Ch R = 1 ,11062   ,510,510,510
BEGIN DESCRIPTION:
UNT 199 IN UKCR 17.0
END DESCRIPTION:
XS GIS Cut Line= 4
      3712228.71     10504173.76      3712999.51     10503764.05
      3713099.61     10503610.19      3713099.61     10502810.17
#Sta/Elev= 30
  3962.2  248.98  3974.5  248.61  3980.3  246.87    3986  248.14  4024.3  248.27
  4040.6  245.88  4068.2  246.77  4084.6  244.85  4282.4  241.02  4518.5  228.77
    4654  223.99  4765.2  215.71  4810.5   214.9  4972.3  215.95  4982.9  216.35
    4987  209.15  4989.8  208.65    4993  209.15  5005.1  209.82  5011.1  214.54
  5015.7  215.85  5079.6  215.19  5138.7  213.42  5208.7  214.27  5385.4  222.78
  5478.7  228.68  5648.7  246.48  5678.7  248.01  5778.7  258.33  5818.7     261
#Mann= 7 ,-1 , 0
  3962.2     .16       0  4810.5     .12       0  4972.3     .16       0
    4987     .07       0    4993     .16       0  5079.6     .12       0
  5385.4     .16       0
Bank Sta=4982.9,5015.7
XS Rating Curve= 0 ,0
Exp/Cntr=0.3,0.1

Type RM Length L Ch R = 1 ,10552   ,406,406,406
BEGIN DESCRIPTION:
UNT 199 IN UKCR 16.0
END DESCRIPTION:
XS GIS Cut Line= 3
      3713891.87     10504205.02      3713443.95     10503746.69
      3713399.61     10503260.16
#Sta/Elev= 30
  4406.5  241.15    4454  241.32    4461  239.19  4482.3  238.86  4503.4  235.18
  4524.7  234.55  4531.7  232.81  4574.2   230.8  4630.1  225.76    4676  221.86
  4786.3  215.24  4835.8  213.69  4899.5  213.31  4977.2  214.93  4988.4  209.06
  4991.1  208.56  4994.4  209.06  5019.6  211.31  5026.8  214.55  5033.8  214.69
  5155.6   213.3  5274.8  213.15    5335  217.45  5416.8  227.19  5435.5  230.04
  5445.5  233.72  5465.6  238.42  5475.6  239.47  5480.7  242.35  5535.9  247.48
#Mann= 7 ,-1 , 0
  4406.5     .16       0  4630.1     .12       0    4676     .05       0
  4988.4     .03       0  4994.4     .05       0  5155.6     .12       0
  5416.8     .16       0
Bank Sta=4977.2,5033.8
XS Rating Curve= 0 ,0
Exp/Cntr=0.3,0.1

Type RM Length L Ch R = 1 ,10146   ,451,451,451
BEGIN DESCRIPTION:
UNT 199 IN UKCR 15.0
END DESCRIPTION:
XS GIS Cut Line= 3
      3714249.63      10503810.2      3713749.61     10503510.19
      3713149.59     10502810.17
#Sta/Elev= 30
  4383.5  257.86  4695.1  227.73    4850  214.01  4900.5  212.12    4988  213.87
  4991.6  208.66  4994.4  208.16  4997.6  208.66  5008.9  208.87  5016.6  214.43
  5098.1  212.73    5179  213.99  5207.5  219.08  5278.9  226.27  5321.7  233.34
  5328.3  235.65  5342.5  236.01  5363.4  239.99  5371.1  239.49  5377.7  242.04
  5399.6  241.76  5406.2   243.2  5413.9  241.81  5420.5  243.22  5434.7   241.2
  5441.3   242.4  5590.6  238.97  5654.2  240.68  5746.4  245.85  5888.6  258.44
#Mann= 5 ,-1 , 0
  4383.5     .16       0  4695.1     .05       0  4991.6     .03       0
  4997.6     .05       0  5098.1     .16       0
Bank Sta=4988,5016.6
XS Rating Curve= 0 ,0
Exp/Cntr=0.3,0.1

Type RM Length L Ch R = 1 ,9695    ,451,451,451
BEGIN DESCRIPTION:
UNT 199 IN UKCR 14.0
END DESCRIPTION:
XS GIS Cut Line= 3
      3714299.62     10503660.21      3713999.61     10503160.19
      3713599.62     10502760.19
#Sta/Elev= 30
  4385.8  253.08  4537.4  238.34    4553  237.96  4574.8  234.77  4632.7  229.55
  4654.1  225.47  4677.4  225.56  4691.9  223.79  4727.3  219.75  4801.8  213.95
  4844.5     212    4897  211.47  4915.9  212.46  4968.9  212.96  4983.1  213.12
  4994.2  209.64    4997  209.14  5000.2  209.64  5025.5  213.87  5039.6  212.05
  5060.7  211.97  5152.8  218.74  5166.9  222.18  5195.2  223.92  5209.3  229.41
  5242.5  232.93  5265.9  237.14  5350.8  243.76  5418.6  241.07  5534.6  241.39
#Mann= 10 ,-1 , 0
  4385.8     .16       0  4574.8     .05       0  4691.9     .07       0
  4727.3     .12       0  4915.9     .16       0  4994.2     .07       0
  5000.2     .16       0  5060.7     .07       0  5242.5     .16       0
  5418.6     .05       0
Bank Sta=4968.9,5025.5
XS Rating Curve= 0 ,0
Exp/Cntr=0.3,0.1

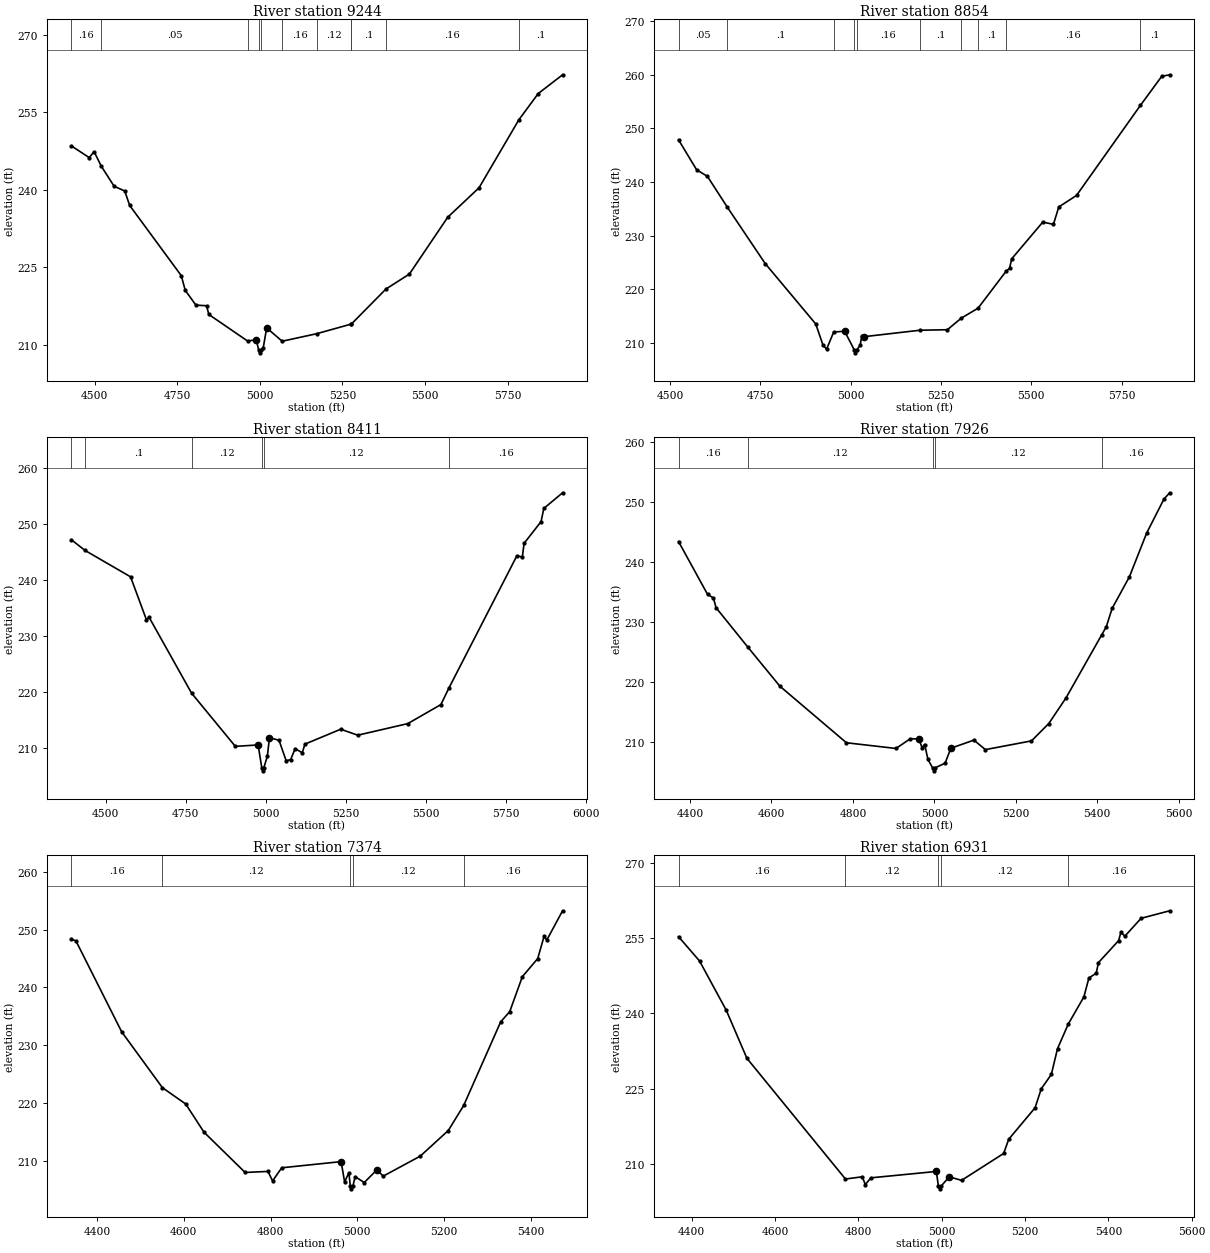
Type RM Length L Ch R = 1 ,9244    ,390,390,390
BEGIN DESCRIPTION:
UNT 199 IN UKCR 13.0
END DESCRIPTION:
XS GIS Cut Line= 3
      3714549.62     10503410.23      3714349.61     10502910.19
      3714049.62     10502010.23
#Sta/Elev= 30
  4429.3  248.51  4483.2  246.24    4498   247.4  4519.9  244.56  4558.6   240.7
  4590.9  239.76  4605.7  236.97  4761.9  223.37    4774  220.51  4806.3  217.65
  4838.6  217.53  4845.3  215.84  4962.5   210.7  4988.9  210.92  4996.5   208.9
  4999.2   208.4  5002.5   208.9    5010  209.33  5020.6  213.24  5067.4  210.65
  5172.1  212.11  5276.9  213.98  5277.3     214  5381.7  220.77  5452.7  223.67
  5568.7  234.68  5663.6   240.4  5784.2  253.58  5842.8  258.66  5916.5   262.3
#Mann= 11 ,-1 , 0
  4429.3     .16       0  4519.9     .05       0  4962.5     .16       0
  4996.5     .07       0  5002.5     .16       0  5067.4     .16       0
  5172.1     .12       0  5276.9     .16       0  5277.3      .1       0
  5381.7     .16       0  5784.2      .1       0
Bank Sta=4988.9,5020.6
XS Rating Curve= 0 ,0
Exp/Cntr=0.3,0.1

Type RM Length L Ch R = 1 ,8854    ,443,443,443
BEGIN DESCRIPTION:
UNT 199 IN UKCR 12.0
END DESCRIPTION:
XS GIS Cut Line= 3
      3714649.61     10503160.15      3714649.61     10502660.19
      3714149.61     10501960.19
#Sta/Elev= 30
  4523.2  247.85  4573.2  242.28  4603.2  241.04  4658.5  235.28  4763.2  224.79
  4903.2  213.53  4923.2  209.59  4933.2  208.84  4952.9  212.03  4983.2  212.18
  5010.2  208.65  5012.9  208.15  5016.2  208.65  5026.2  209.57  5030.5  211.29
  5036.7  211.16  5191.2  212.36  5267.7  212.46  5306.3  214.62  5352.6  216.47
  5430.3  223.36  5439.8   223.9  5445.9  225.68  5531.9  232.52  5561.4   232.1
  5576.2  235.34  5625.3  237.49  5802.3  254.28  5861.3  259.69  5883.4  259.98
#Mann= 10 ,-1 , 0
  4523.2     .05       0  4658.5      .1       0  4952.9     .16       0
  5010.2     .07       0  5016.2     .16       0  5191.2      .1       0
  5306.3     .16       0  5352.6      .1       0  5430.3     .16       0
  5802.3      .1       0
Bank Sta=4983.2,5036.7
XS Rating Curve= 0 ,0
Exp/Cntr=0.3,0.1

Type RM Length L Ch R = 1 ,8411    ,485,485,485
BEGIN DESCRIPTION:
UNT 199 IN UKCR 11.0
END DESCRIPTION:
XS GIS Cut Line= 3
      3714699.63     10503160.16      3715099.61     10502660.19
      3715899.61     10502260.19
#Sta/Elev= 30
  4392.5  247.25  4435.3  245.34  4577.3  240.64    4627  232.96    4635  233.44
  4767.9  219.88  4904.7  210.38  4975.9  210.63  4987.4  206.51  4990.1  206.01
  4993.4  206.51  5004.8  208.61  5011.2  211.91  5041.2  211.47  5063.5  207.81
  5077.5  208.01  5091.5  209.97  5113.8  209.24  5122.2  210.78    5234  213.44
  5287.1  212.37  5443.6  214.44  5547.1  217.84  5571.7  220.75  5784.6  244.41
  5801.4  244.17    5807  246.62  5860.1   250.5  5868.5  252.84  5927.2  255.64
#Mann= 6 ,-1 , 0
  4392.5     .05       0  4435.3      .1       0  4767.9     .12       0
  4987.4     .07       0  4993.4     .12       0  5571.7     .16       0
Bank Sta=4975.9,5011.2
XS Rating Curve= 0 ,0
Exp/Cntr=0.3,0.1

Type RM Length L Ch R = 1 ,7926    ,552,552,552
BEGIN DESCRIPTION:
UNT 199 IN UKCR 10.0
END DESCRIPTION:
XS GIS Cut Line= 3
       3715099.6      10503360.2      3715499.61     10502860.19
       3715899.6     10502460.19
#Sta/Elev= 30
  4371.8  243.37    4443  234.59  4457.5  233.99  4463.9  232.37  4542.2  225.79
  4620.7  219.31    4784  209.91  4905.7  208.96  4940.9  210.58  4961.7  210.54
  4969.7  209.11  4976.1  209.62  4984.1  207.15  4995.5  205.74  4998.3  205.24
  5001.5  205.74  5026.3  206.51  5040.4     209    5097  210.35  5125.3  208.77
  5238.4  210.22  5280.8   213.1  5323.2  217.37  5410.4  227.81  5422.2  229.22
  5436.4  232.25  5478.8   237.5  5521.2  244.78  5563.7  250.44  5577.8  251.48
#Mann= 5 ,-1 , 0
  4371.8     .16       0  4542.2     .12       0  4995.5     .07       0
  5001.5     .12       0  5410.4     .16       0
Bank Sta=4961.7,5040.4
XS Rating Curve= 0 ,0
Exp/Cntr=0.3,0.1

Type RM Length L Ch R = 1 ,7374    ,443,443,443
BEGIN DESCRIPTION:
UNT 199 IN UKCR 9.0
END DESCRIPTION:
XS GIS Cut Line= 3
      3715649.61     10503710.17      3715849.61     10503110.19
      3716249.58     10502810.21
#Sta/Elev= 30
  4340.8  248.37  4351.3  248.07  4456.7  232.31  4550.6  222.63  4604.3   219.8
  4646.5  214.91  4741.3  207.93    4794  208.11  4804.6  206.46  4825.7  208.74
  4962.7  209.81  4970.6  206.29  4980.5  207.88  4983.8  205.59  4986.5  205.09
  4989.8  205.59  4995.1   207.2  5015.9  206.18  5045.1  208.38  5059.7  207.29
  5145.1  210.76  5209.7   215.2  5245.2  219.54  5330.5  234.04  5351.4  235.82
  5380.5  241.88  5415.9  245.01  5430.5  248.86  5436.8  248.22  5473.2   253.3
#Mann= 5 ,-1 , 0
  4340.8     .16       0  4550.6     .12       0  4983.8     .07       0
  4989.8     .12       0  5245.2     .16       0
Bank Sta=4962.7,5045.1
XS Rating Curve= 0 ,0
Exp/Cntr=0.3,0.1

Type RM Length L Ch R = 1 ,6931    ,393,393,393
BEGIN DESCRIPTION:
UNT 199 IN UKCR 8.0
END DESCRIPTION:
XS GIS Cut Line= 3
      3715749.63     10503860.16      3716149.61     10503360.19
      3716349.61     10502860.18
#Sta/Elev= 30
  4368.5  255.25  4418.9  250.41  4482.9  240.63  4532.5  231.06  4769.1  207.03
  4809.5  207.48  4816.7  205.93  4830.3  207.27  4987.2  208.54  4992.2  205.58
  4994.9  205.08  4998.2  205.58  5018.2  207.46  5047.8  206.77  5148.8  212.12
  5160.9  214.94  5224.2  221.21    5239  224.98  5263.2  227.84    5278  232.96
  5303.7  237.84  5341.3  243.27  5353.4  247.03  5370.9  247.98  5376.3  250.09
  5424.8  254.47  5430.2  256.16  5439.6  255.34  5478.6   258.9  5547.3   260.4
#Mann= 5 ,-1 , 0
  4368.5     .16       0  4769.1     .12       0  4992.2     .07       0
  4998.2     .12       0  5303.7     .16       0
Bank Sta=4987.2,5018.2
XS Rating Curve= 0 ,0
Exp/Cntr=0.3,0.1

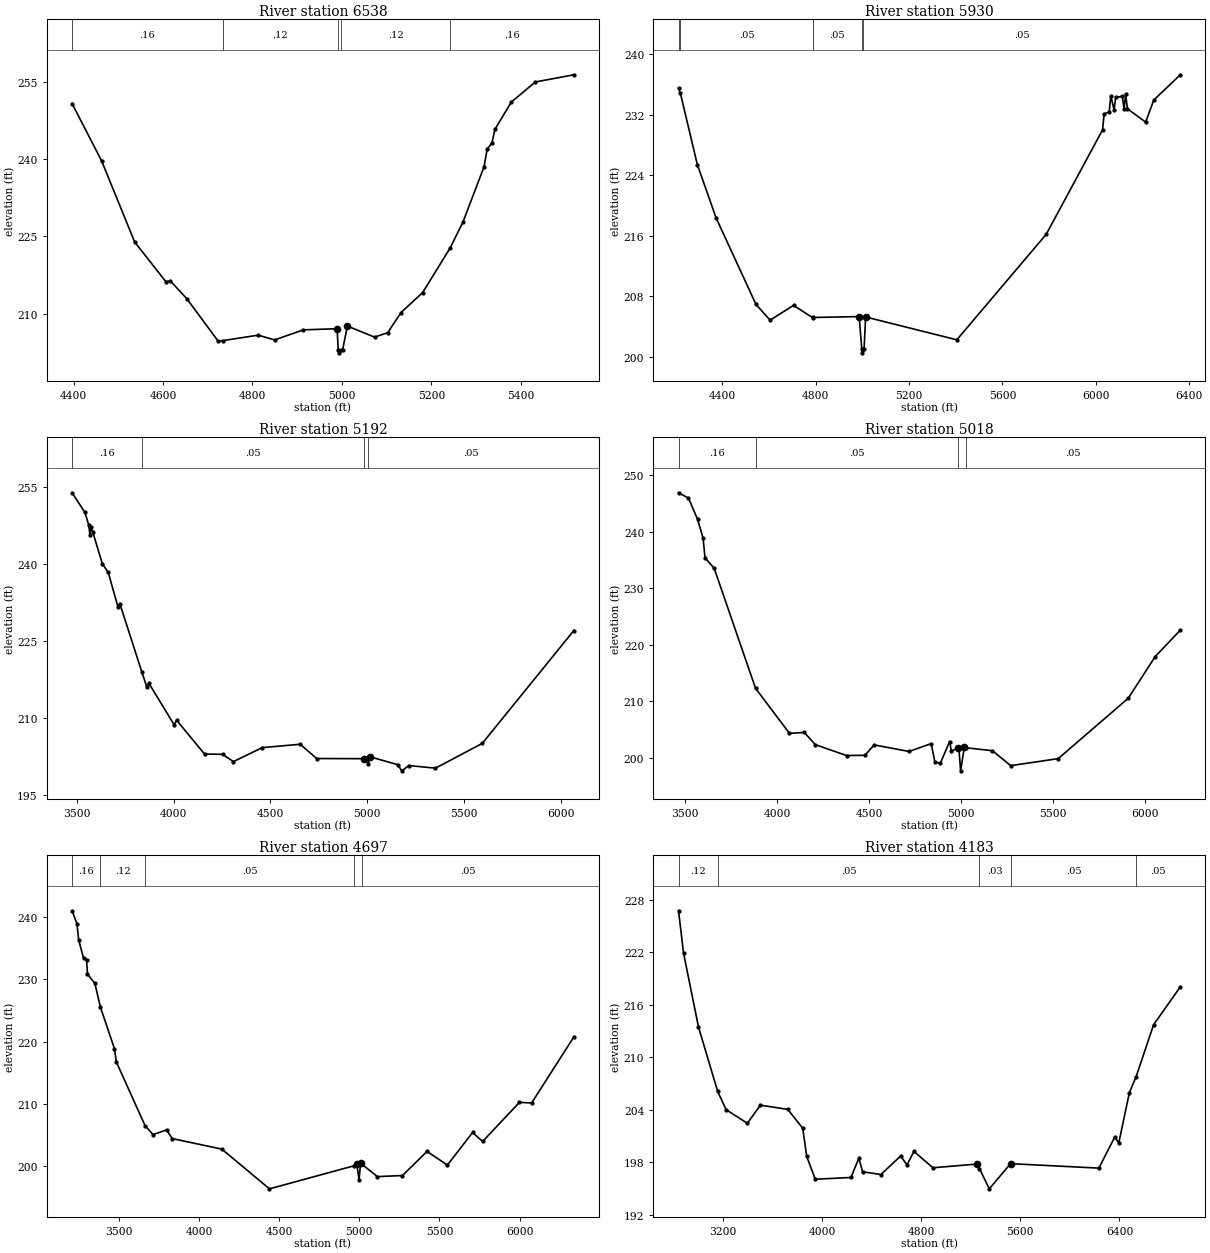
Type RM Length L Ch R = 1 ,6538    ,608,608,608
BEGIN DESCRIPTION:
UNT 199 IN UKCR 7.0
END DESCRIPTION:
XS GIS Cut Line= 3
      3715949.64     10503910.17      3716449.61     10503610.19
      3716649.62     10503110.16
#Sta/Elev= 30
  4396.8  250.78  4462.8  239.66  4536.7  223.92  4606.7  216.19  4616.4  216.38
  4653.3  212.91  4723.3  204.69  4733.1  204.77  4812.7  205.84  4849.6  204.92
  4913.8  206.87  4989.3  207.09  4991.7  202.91  4994.4  202.41  4997.7  202.91
  5001.4  202.94  5012.2  207.61  5072.8  205.46  5102.4  206.32    5132  210.23
  5180.5  214.11    5242  222.78  5270.7  227.82  5317.8  238.55  5324.5  241.88
  5335.3  243.15    5342  245.77  5378.4  251.05  5432.2  254.96  5518.4  256.36
#Mann= 5 ,-1 , 0
  4396.8     .16       0  4733.1     .12       0  4991.7     .07       0
  4997.7     .12       0    5242     .16       0
Bank Sta=4989.3,5012.2
XS Rating Curve= 0 ,0
Exp/Cntr=0.3,0.1

Type RM Length L Ch R = 1 ,5930    ,738,738,738
BEGIN DESCRIPTION:
UNT 199 IN UKCR 6.0
END DESCRIPTION:
XS GIS Cut Line= 3
       3716099.6     10504060.19      3716826.64     10503986.97
      3717899.59      10503060.2
#Sta/Elev= 30
    4213  235.51  4221.2  234.81  4293.4  225.42  4373.8  218.38  4544.7  206.94
    4605  204.87  4705.5  206.82  4786.8   205.2  4788.1  205.22  4986.5  205.34
  4997.5  201.05  5000.2  200.55  5003.5  201.05  5007.4  201.06    5014  205.29
  5404.5  202.27  5787.3  216.21  6028.6  230.01  6035.2  232.11  6057.1  232.38
  6063.7  234.49    6078  232.63  6084.6  234.29  6113.1  234.42  6120.7  232.76
  6127.3  234.69    6135   232.8  6212.9  231.02    6248  233.95  6361.5  237.28
#Mann= 6 ,-1 , 0
    4213     .16       0  4221.2     .05       0  4786.8     .12       0
  4788.1     .05       0  4997.5     .03       0  5003.5     .05       0
Bank Sta=4986.5,5014
XS Rating Curve= 0 ,0
Exp/Cntr=0.3,0.1

Type RM Length L Ch R = 1 ,5192    ,174,174,174
BEGIN DESCRIPTION:
Mapping XS d910268f
END DESCRIPTION:
XS GIS Cut Line= 5
      3715773.35     10504281.48      3716992.96     10504199.02
       3717374.9     10504164.29      3717518.13     10503990.68
      3717795.27     10503280.52
#Sta/Elev= 30
  3474.8  253.87  3541.2  250.04  3561.3  247.54  3567.2  245.63  3572.2  247.13
  3581.3   246.3  3631.4  239.99  3661.5  238.38  3711.4  231.69  3721.6  232.26
    3835  218.97  3860.7  216.04    3872  216.72  4002.3  208.64    4015  209.53
  4159.3  202.94  4252.8  202.88  4308.6  201.46  4457.9  204.19  4653.7  204.84
  4739.2  202.06    4985  202.03  5005.1  201.08  5015.1  202.39  5158.1  200.86
  5178.6  199.66  5215.4  200.69  5352.9  200.18  5594.7  205.01  6068.1  227.02
#Mann= 4 ,-1 , 0
  3474.8     .16       0    3835     .05       0    4985     .03       0
  5005.1     .05       0
Bank Sta=4985,5015.1
XS Rating Curve= 0 ,0
Exp/Cntr=0.3,0.1

Type RM Length L Ch R = 1 ,5018    ,321,321,321
BEGIN DESCRIPTION:
Mapping XS 571abb67
END DESCRIPTION:
XS GIS Cut Line= 5
       3715725.6     10504342.25      3716745.56     10504363.95
      3717344.52     10504329.22      3717496.43      10504207.7
      3717856.66     10503365.72
#Sta/Elev= 30
  3463.9  246.89  3517.9  245.95  3567.9  242.16  3597.6  238.84  3607.9  235.39
    3658   233.5    3883  212.26  4067.7  204.28  4148.1  204.45  4208.1  202.29
  4378.1  200.36  4478.1   200.4  4528.2  202.24  4718.5  201.08  4838.7  202.47
  4858.8   199.2  4888.8  199.01  4938.9  202.84  4948.9  201.13  4982.5   201.7
    4989  201.86  4998.8  197.65    5019  201.82  5029.1  201.73  5172.2  201.21
  5271.4  198.57  5529.8  199.81  5910.9   210.5  6057.8  217.89  6194.4  222.56
#Mann= 4 ,-1 , 0
  3463.9     .16       0    3883     .05       0  4982.5     .03       0
  5029.1     .05       0
Bank Sta=4982.5,5019
XS Rating Curve= 0 ,0
Exp/Cntr=0.3,0.1

Type RM Length L Ch R = 1 ,4697    ,514,514,514
BEGIN DESCRIPTION:
UNT 199 IN UKCR 5.0
END DESCRIPTION:
XS GIS Cut Line= 6
      3715669.22     10504429.06       3716728.2     10504611.34
      3717166.57     10504650.41      3717557.19     10504533.22
      3717691.74      10504251.1      3717952.17     10503396.03
#Sta/Elev= 30
    3209  241.01  3239.8  238.92  3250.1  236.34  3280.4  233.42  3299.9  233.08
  3304.9  230.84  3351.5  229.34    3385  225.59  3473.2  218.86  3484.7  216.76
    3664   206.5  3714.2  205.06  3797.9  205.81    3834  204.42  4142.9  202.73
  4439.8  196.35    4967  200.05    4984   200.4  4998.3  197.82  5008.7  200.53
  5017.1  200.28  5113.1  198.31  5269.1  198.49  5422.4  202.36  5549.5  200.17
  5706.3   205.4  5769.1  203.96  5998.4  210.24  6074.6  210.14  6337.9  220.75
#Mann= 5 ,-1 , 0
    3209     .16       0    3385     .12       0    3664     .05       0
    4967     .03       0  5017.1     .05       0
Bank Sta=4984,5008.7
XS Rating Curve= 0 ,0
Exp/Cntr=0.3,0.1

Type RM Length L Ch R = 1 ,4183    ,2101,2101,2101
BEGIN DESCRIPTION:
UNT 199 IN UKCR 4.0
END DESCRIPTION:
XS GIS Cut Line= 4
      3715681.22      10504575.7      3717077.04     10505028.82
      3718202.04     10504804.87      3718079.55     10503375.41
#Sta/Elev= 30
    2842  226.77  2882.4  221.93  3002.8  213.49  3157.9   206.1  3226.5  204.01
  3397.5  202.46  3502.7  204.53  3723.5  204.05  3844.3  201.89  3876.3  198.67
  3945.5  196.06  4233.2  196.26  4297.1  198.46  4327.8  196.91  4475.3   196.6
  4634.4  198.72  4685.5  197.69  4741.7  199.24    4895  197.37  5247.6  197.79
  5270.6  197.28  5349.5  194.96  5521.5  197.84  6234.1  197.33  6361.6  200.88
  6394.7  200.22  6480.3  205.97  6535.2  207.81  6675.7  213.73  6891.3  218.07
#Mann= 5 ,-1 , 0
    2842     .12       0  3157.9     .05       0  5270.6     .03       0
  5521.5     .05       0  6535.2     .05       0
Bank Sta=5247.6,5521.5
XS Rating Curve= 0 ,0
Exp/Cntr=0.3,0.1

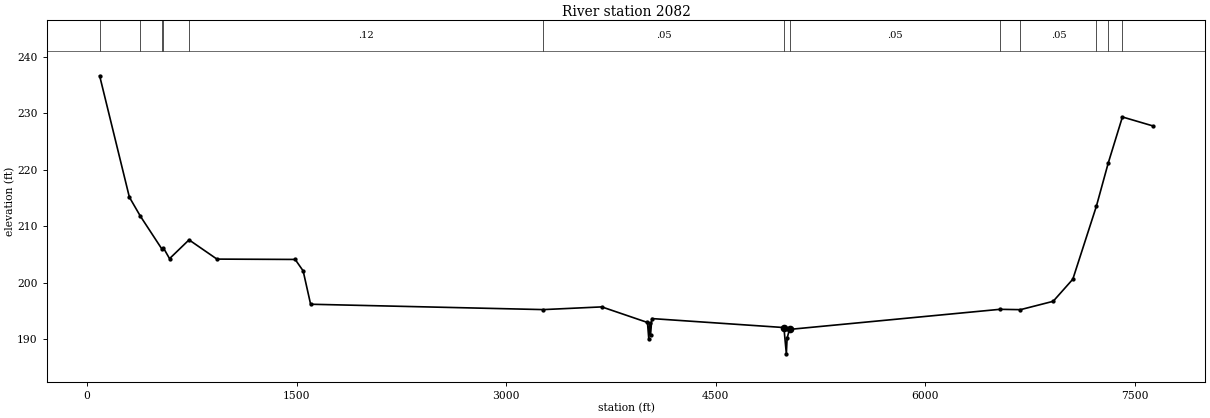
Type RM Length L Ch R = 1 ,2082    ,0,0,0
BEGIN DESCRIPTION:
UNT 199 IN UKCR 1.0
END DESCRIPTION:
XS GIS Cut Line= 4
      3715144.55     10504824.43      3717681.96     10506225.35
      3719287.58     10505270.25      3719049.61     10502510.16
#Sta/Elev= 30
    90.3  236.65   303.1  215.14   381.8  211.77   534.1  206.01   546.6  206.16
   590.7  204.24   730.1  207.57   929.9  204.16  1489.7   204.1  1546.8  202.07
  1600.2  196.16  3265.5  195.21  3684.1  195.69    4011  192.93  4020.8  189.93
  4026.6  192.77  4033.2  190.75  4042.2  193.62  4987.5  192.03    5005  187.37
  5010.3  190.15  5027.7   191.7  6533.1  195.26  6680.7   195.2  6914.6  196.68
  7055.2   200.6  7223.8  213.53  7308.7  221.19  7410.1  229.35  7627.3  227.77
#Mann= 13 ,-1 , 0
    90.3     .05       0   381.8     .16       0   534.1     .05       0
   546.6     .16       0   730.1     .12       0  3265.5     .05       0
  4987.5     .03       0  5027.7     .05       0  6533.1     .07       0
  6680.7     .05       0  7223.8     .07       0  7308.7     .05       0
  7410.1     .12       0
Bank Sta=4987.5,5027.7
XS Rating Curve= 0 ,0
Exp/Cntr=0.3,0.1

Chan Stop Cuts=-1
Use User Specified Reach Order=0
Composite Channel Slope=5