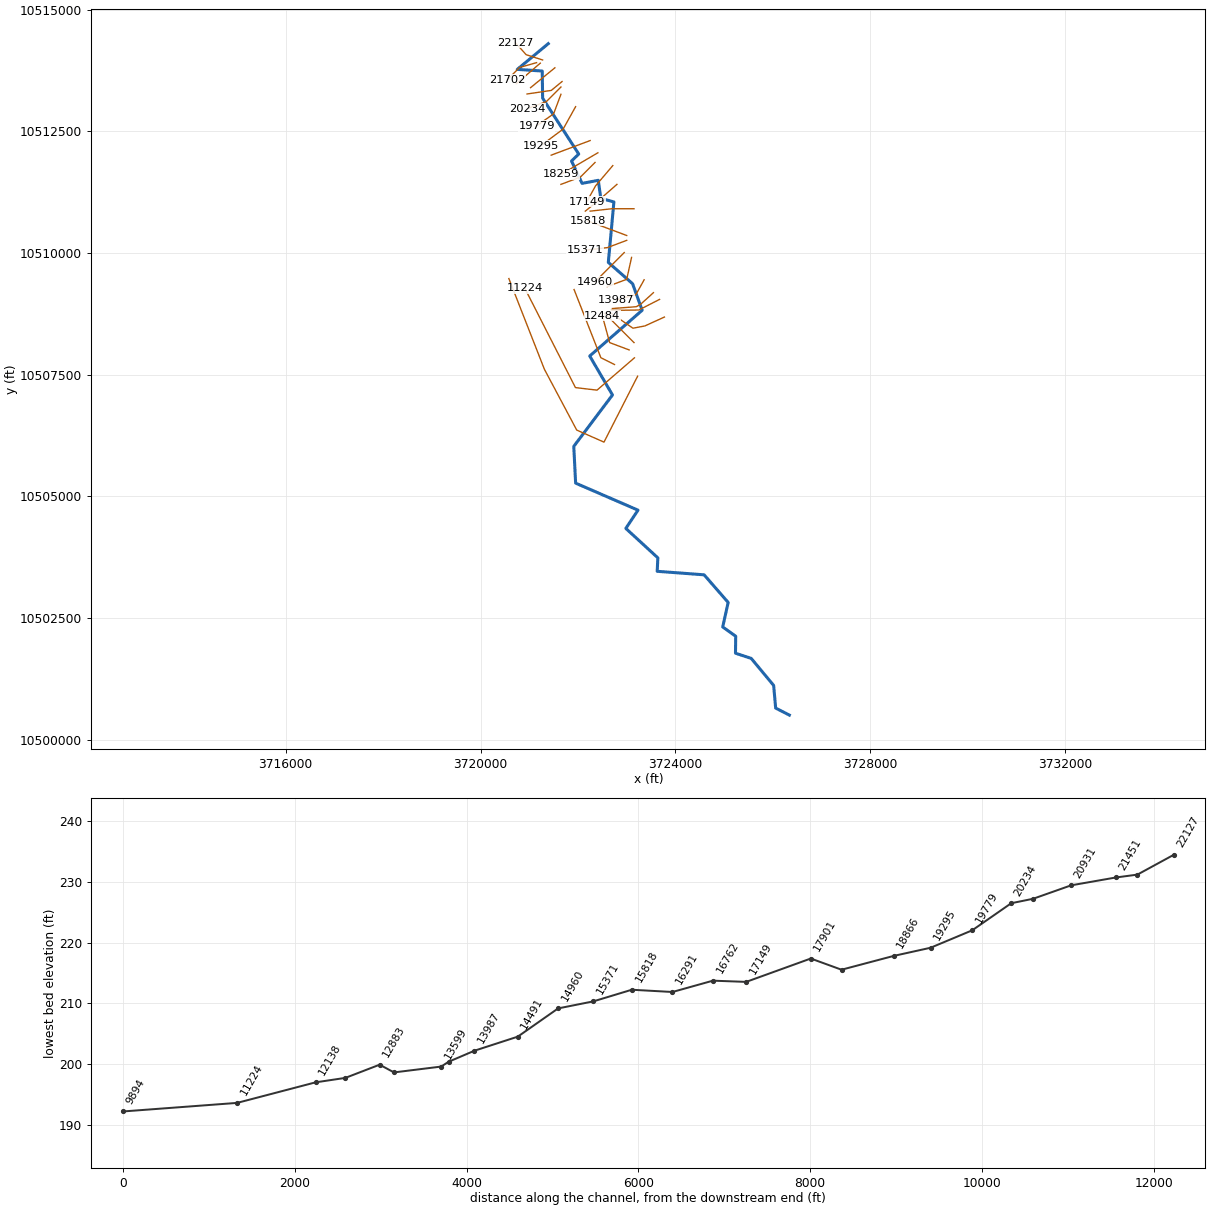
--- UNT 205 IN UKCR.prj (project) ---

Proj Title=UNT 205 IN UKCR Base Level Engineering
Current Plan=p01
Default Exp/Contr=0.3,0.1
English Units
Geom File=g01
Flow File=f01
Plan File=p01
BEGIN DESCRIPTION:
UNT 205 IN UKCR
END DESCRIPTION:

--- UNT 205 IN UKCR.p01 (plan) ---

Plan Title=Multiple Run
Short Identifier=Multiple
Geom File=g01
Flow File=f01
Subcritical Flow
K Sum by GR= 0
Std Step Tol= 0.01
Critical Tol= 0.01
Num of Std Step Trials= 20
Max Error Tol= 0.3
Flow Tol Ratio= 0.001
Split Flow NTrial= 30
Split Flow Tol= 0.02
Split Flow Ratio= 0.02
Log Output Level= 0
Friction Slope Method= 1
Unsteady Friction Slope Method= 2
Unsteady Bridges Friction Slope Method= 1
Parabolic Critical Depth
Global Vel Dist=  1 , 1 , 1
Global Log Level= 0
CheckData=True
Encroach Param= -1, 0, 0, 0
BEGIN DESCRIPTION:
Multiple Run
END DESCRIPTION:

--- UNT 205 IN UKCR.f01 (steady flow) ---

Flow Title=Multiple
Number of Profiles=7
Profile Names=10-year,25-year,50-year,1pct_min,100-year,1pct_plu,500-year
River Rch & RM= UNT 205 IN UKCR,Reach-1,22127
     345     445     523     451     610     825     835
River Rch & RM= UNT 205 IN UKCR,Reach-1,20931
     648     866    1043     921    1245    1684    1783
River Rch & RM= UNT 205 IN UKCR,Reach-1,13687
     705     940    1131     996    1347    1822    1921
Boundary for River Rch & Prof#=UNT 205 IN UKCR,Reach-1,1
Up Type=0
Dn Type=3
Dn Slope=0.005
Boundary for River Rch & Prof#=UNT 205 IN UKCR,Reach-1,2
Up Type=0
Dn Type=3
Dn Slope=0.005
Boundary for River Rch & Prof#=UNT 205 IN UKCR,Reach-1,3
Up Type=0
Dn Type=3
Dn Slope=0.005
Boundary for River Rch & Prof#=UNT 205 IN UKCR,Reach-1,4
Up Type=0
Dn Type=3
Dn Slope=0.005
Boundary for River Rch & Prof#=UNT 205 IN UKCR,Reach-1,5
Up Type=0
Dn Type=3
Dn Slope=0.005
Boundary for River Rch & Prof#=UNT 205 IN UKCR,Reach-1,6
Up Type=0
Dn Type=3
Dn Slope=0.005
Boundary for River Rch & Prof#=UNT 205 IN UKCR,Reach-1,7
Up Type=0
Dn Type=3
Dn Slope=0.005

--- UNT 205 IN UKCR.g01 (geometry) ---

Geom Title=Existing Conditions

River Reach=UNT 205 IN UKCR,Reach-1
Reach XY= 30
      3721389.50     10514300.00      3720753.25     10513772.00
      3721266.00     10513738.00      3721273.50     10513181.00
      3722014.75     10512033.00      3721866.75     10511890.00
      3722083.75     10511431.00      3722416.00     10511493.00
      3722467.25     10511124.00      3722736.75     10511049.00
      3722622.25     10509807.00      3723120.25     10509369.00
      3723317.25     10508824.00      3722240.50     10507885.00
      3722707.62     10507084.74      3721913.00     10506029.00
      3721951.25     10505274.00      3723231.50     10504719.00
      3722981.50     10504344.00      3723639.25     10503739.00
      3723625.50     10503463.00      3724588.75     10503391.00
      3725082.25     10502824.00      3724970.50     10502320.00
      3725237.25     10502129.00      3725232.75     10501781.00
      3725556.00     10501674.00      3726016.25     10501119.00
      3726057.25     10500654.00      3726338.50     10500510.00

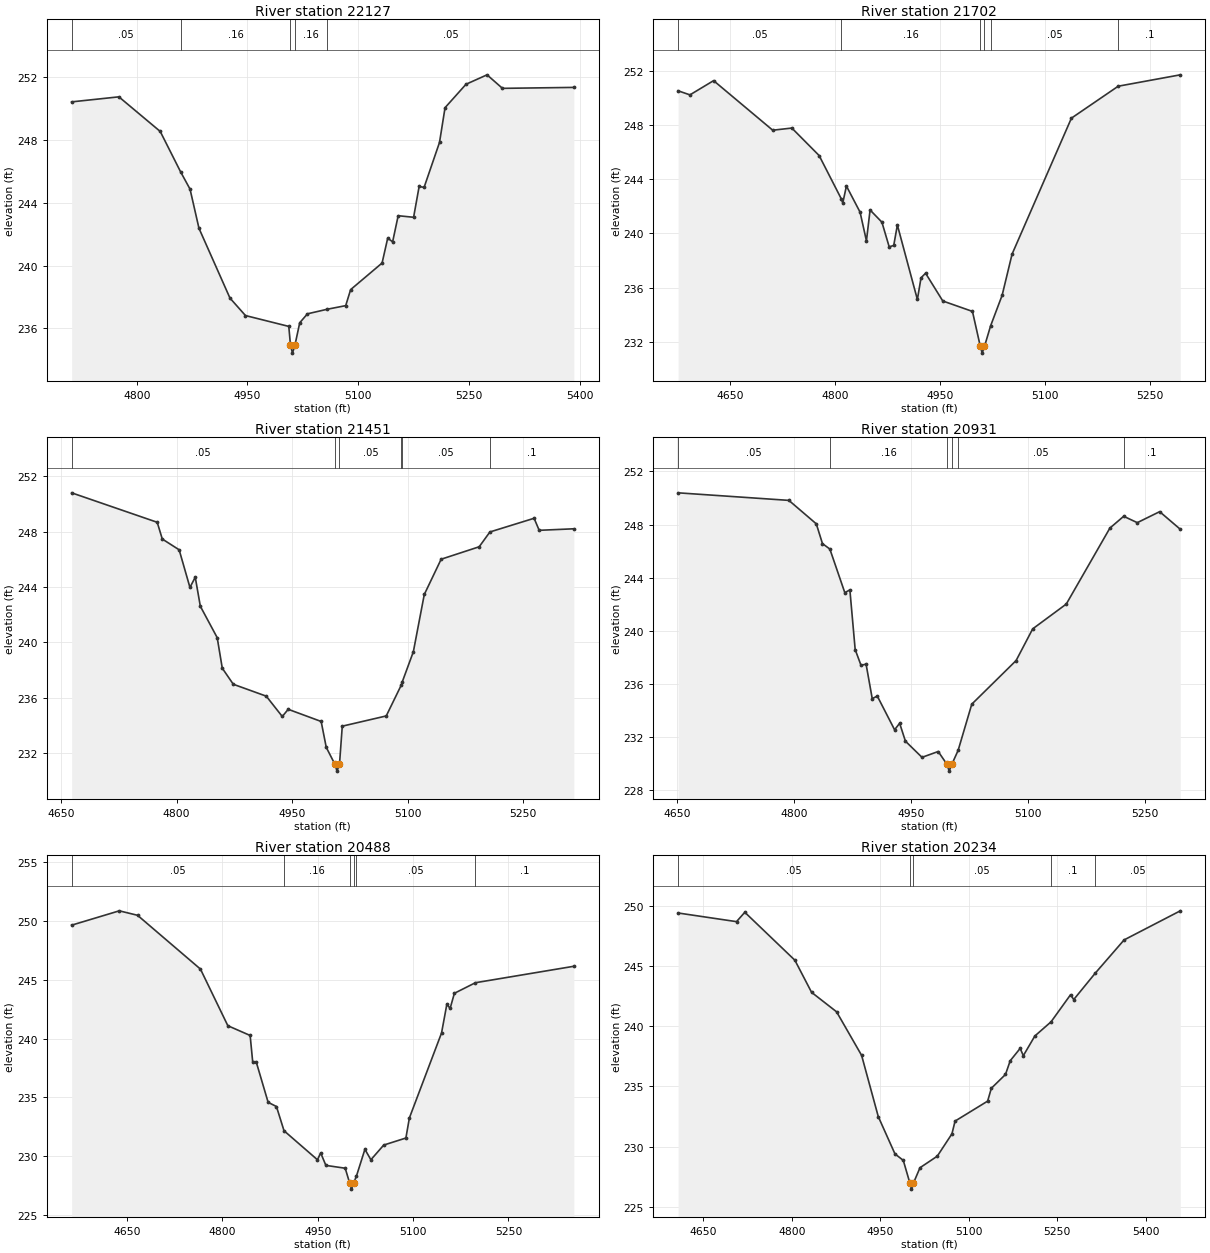
Type RM Length L Ch R = 1,22127,425,425,425
BEGIN DESCRIPTION:
UNT 205 IN UKCR 25.0
END DESCRIPTION:
XS GIS Cut Line= 3
      3721273.85     10513965.08      3720935.26     10514073.60
      3720718.91     10514315.92
#Sta/Elev= 30
  4711.8  250.41  4775.8  250.73  4831.8  248.53  4859.3  245.97  4872.2  244.86
  4884.3  242.37  4926.3  237.93  4947.3  236.82  5006.0  236.13  5008.3  234.93
  5011.0  234.43  5014.3  234.93  5020.8  236.36  5031.3  236.93  5058.0  237.22
  5083.1  237.45  5089.8  238.47  5132.4  240.16  5140.0  241.74  5146.7  241.51
  5154.2  243.17  5175.1  243.07  5182.6  245.03  5189.3  244.97  5210.2  247.83
  5217.7  250.04  5246.1  251.53  5274.6  252.13  5295.5  251.27  5392.2  251.33
#Mann=5,-1,0
  4711.8    0.05       0  4859.3    0.16       0  5008.3    0.07       0
  5014.3    0.16       0  5058.0    0.05       0
Bank Sta=5008.3,5014.3
Exp/Cntr=0.3,0.1

Type RM Length L Ch R = 1,21702,251,251,251
BEGIN DESCRIPTION:
UNT 205 IN UKCR 24.0
END DESCRIPTION:
XS GIS Cut Line= 3
      3721149.65     10513910.20      3720799.61     10513810.19
      3720549.61     10513560.19
#Sta/Elev= 30
  4575.4  250.53  4592.3  250.23  4626.1  251.28  4710.6  247.62  4737.9  247.78
  4776.9  245.75  4808.5  242.56  4810.7  242.25  4815.9  243.50  4835.4  241.57
  4844.5  239.45  4849.7  241.73  4866.6  240.83  4877.0  239.01  4883.5  239.11
  4888.7  240.62  4917.3  235.12  4922.5  236.72  4929.0  237.06  4953.6  235.01
  4996.0  234.24  5007.2  231.66  5009.9  231.16  5013.2  231.66  5021.9  233.17
  5038.4  235.43  5052.6  238.47  5137.4  248.51  5204.3  250.87  5293.0  251.71
#Mann=6,-1,0
  4575.4    0.05       0  4808.5    0.16       0  5007.2    0.07       0
  5013.2    0.16       0  5021.9    0.05       0  5204.3     0.1       0
Bank Sta=5007.2,5013.2
Exp/Cntr=0.3,0.1

Type RM Length L Ch R = 1,21451,520,520,520
BEGIN DESCRIPTION:
UNT 205 IN UKCR 23.0
END DESCRIPTION:
XS GIS Cut Line= 2
      3721226.07     10513900.00      3720731.57     10513474.91
#Sta/Elev= 30
  4663.8  250.81  4774.9  248.68  4781.5  247.47  4803.4  246.69  4817.4  243.97
  4824.3  244.71  4830.9  242.61  4852.8  240.34  4859.4  238.13  4873.7  236.97
  4916.5  236.11  4937.3  234.64  4945.0  235.16  4987.8  234.28  4994.4  232.41
  5005.6  231.19  5008.4  230.69  5011.6  231.19  5015.2  233.94  5072.3  234.68
  5092.0  236.93  5092.9  237.11  5107.5  239.32  5121.7  243.46  5143.6  246.01
  5193.0  246.91  5206.9  247.98  5264.3  248.97  5270.9  248.10  5315.9  248.21
#Mann=6,-1,0
  4663.8    0.05       0  5005.6    0.03       0  5011.6    0.05       0
  5092.0    0.16       0  5092.9    0.05       0  5206.9     0.1       0
Bank Sta=5005.6,5011.6
Exp/Cntr=0.3,0.1

Type RM Length L Ch R = 1,20931,443,443,443
BEGIN DESCRIPTION:
UNT 205 IN UKCR 22.0
END DESCRIPTION:
XS GIS Cut Line= 2
      3721525.57     10513804.53      3721026.41     10513396.52
#Sta/Elev= 30
  4651.1  250.39  4793.3  249.82  4828.5  248.05  4836.4  246.56  4845.9  246.15
  4865.1  242.86  4871.6  243.07  4878.4  238.57  4885.9  237.38  4892.4  237.47
  4900.3  234.87  4906.8  235.06  4929.0  232.52  4935.5  233.01  4942.9  231.66
  4964.2  230.44  4985.0  230.88  4996.4  229.90  4999.1  229.40  5002.4  229.90
  5010.6  230.97  5028.1  234.45  5085.0  237.74  5106.3  240.13  5149.4  242.00
  5205.4  247.73  5223.1  248.62  5240.6  248.14  5269.3  248.97  5295.8  247.64
#Mann=6,-1,0
  4651.1    0.05       0  4845.9    0.16       0  4996.4    0.07       0
  5002.4    0.16       0  5010.6    0.05       0  5223.1     0.1       0
Bank Sta=4996.4,5002.4
Exp/Cntr=0.3,0.1

Type RM Length L Ch R = 1,20488,254,254,254
BEGIN DESCRIPTION:
Mapping XS 3f3c3857
END DESCRIPTION:
XS GIS Cut Line= 3
      3721673.12     10513522.40      3721451.76     10513340.10
      3720953.64     10513266.46
#Sta/Elev= 30
  4562.7  249.66  4637.7  250.88  4666.4  250.50  4765.4  245.92  4808.5  241.10
  4843.6  240.27  4847.6  238.03  4853.1  238.03  4871.9  234.58  4885.0  234.22
  4896.9  232.16  4949.5  229.69  4954.6  230.27  4962.8  229.21  4993.2  228.97
  5000.3  227.69  5003.0  227.19  5006.3  227.69  5010.7  228.27  5024.2  230.58
  5033.6  229.69  5053.8  230.94  5088.7  231.54  5094.2  233.25  5144.8  240.48
  5153.2  242.94  5158.3  242.57  5165.0  243.86  5198.1  244.76  5353.0  246.16
#Mann=6,-1,0
  4562.7    0.05       0  4896.9    0.16       0  5000.3    0.07       0
  5006.3    0.16       0  5010.7    0.05       0  5198.1     0.1       0
Bank Sta=5000.3,5006.3
Exp/Cntr=0.3,0.1

Type RM Length L Ch R = 1,20234,455,455,455
BEGIN DESCRIPTION:
UNT 205 IN UKCR 21.0
END DESCRIPTION:
XS GIS Cut Line= 3
      3721649.60     10513410.18      3721349.61     10513110.19
      3720949.57     10512960.17
#Sta/Elev= 30
  4607.2  249.43  4706.2  248.71  4720.3  249.49  4805.2  245.50  4833.5  242.83
  4875.9  241.21  4918.3  237.59  4946.6  232.49  4974.9  229.39  4989.0  228.85
  5000.2  226.96  5002.9  226.46  5006.2  226.96  5017.3  228.24  5046.6  229.20
  5071.5  231.06  5076.8  232.12  5132.0  233.78  5138.3  234.85  5162.3  236.00
  5170.3  237.14  5187.2  238.17  5192.5  237.56  5212.1  239.20  5239.6  240.38
  5272.6  242.63  5278.0  242.23  5314.4  244.42  5363.4  247.19  5458.7  249.61
#Mann=5,-1,0
  4607.2    0.05       0  5000.2    0.03       0  5006.2    0.05       0
  5239.6     0.1       0  5314.4    0.05       0
Bank Sta=5000.2,5006.2
Exp/Cntr=0.3,0.1

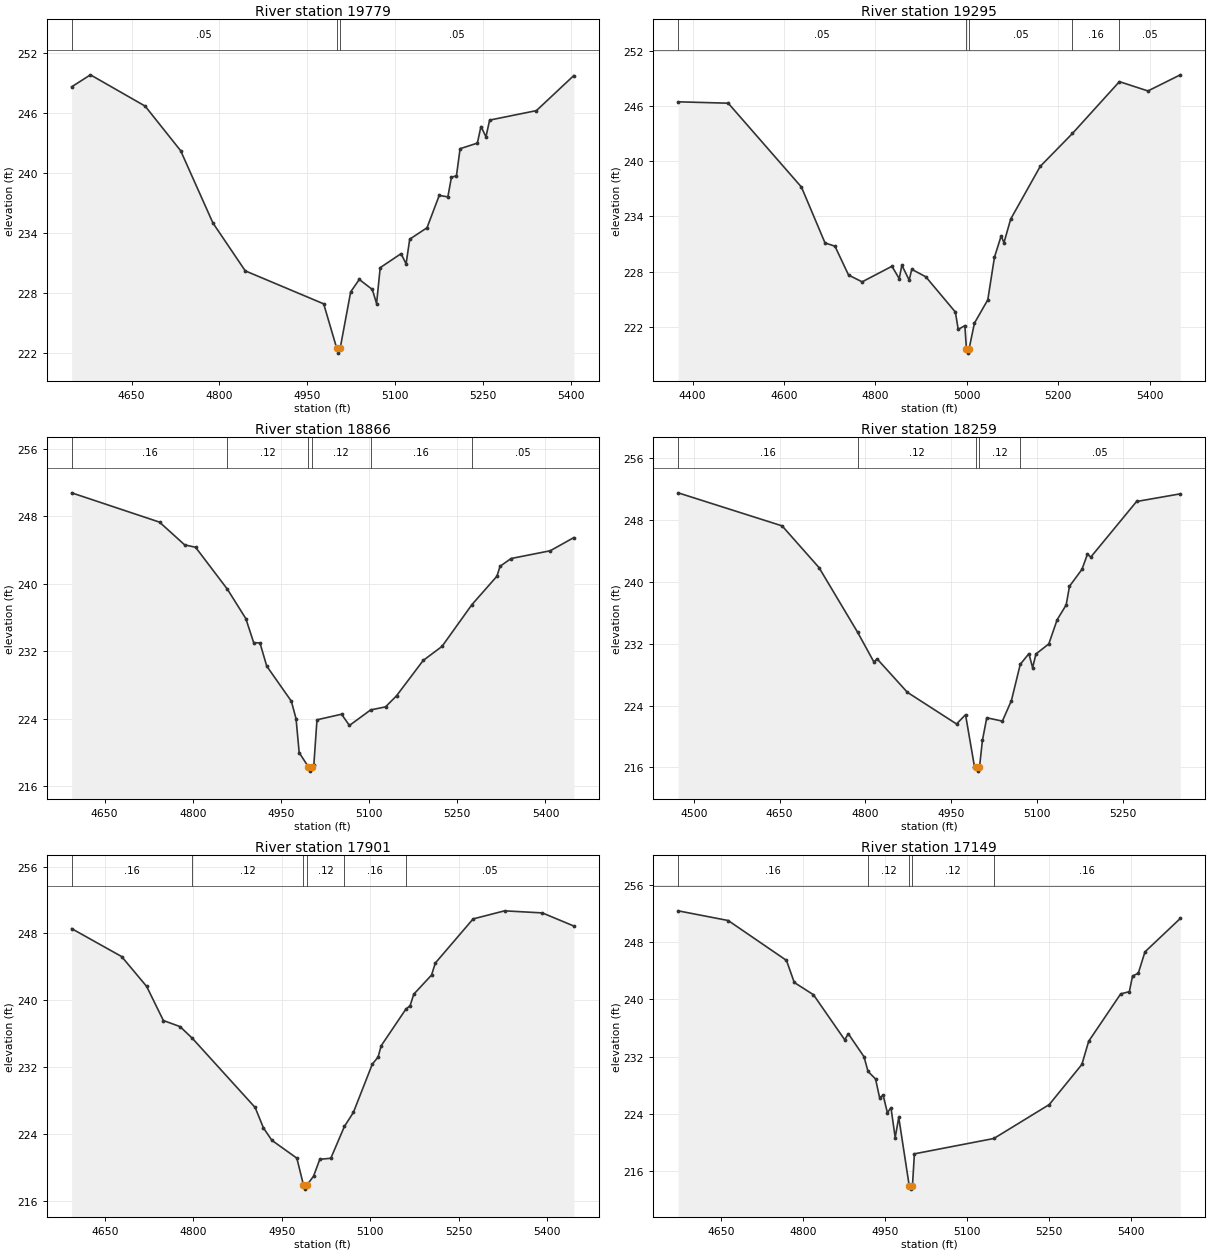
Type RM Length L Ch R = 1,19779,484,484,484
BEGIN DESCRIPTION:
UNT 205 IN UKCR 20.0
END DESCRIPTION:
XS GIS Cut Line= 3
      3721649.62     10513260.23      3721499.61     10512860.19
      3721149.58     10512610.16
#Sta/Elev= 30
  4547.6  248.64  4579.7  249.84  4673.1  246.71  4733.7  242.25  4788.8  235.02
  4844.0  230.23  4977.9  226.93  5000.1  222.50  5002.9  222.00  5006.1  222.50
  5024.0  228.13  5038.7  229.37  5060.9  228.37  5068.2  226.96  5074.4  230.55
  5110.0  231.95  5118.6  230.93  5124.8  233.40  5154.3  234.54  5175.2  237.78
  5189.9  237.63  5196.0  239.59  5204.6  239.75  5210.8  242.45  5240.3  243.01
  5246.4  244.67  5255.0  243.64  5261.2  245.31  5341.1  246.26  5405.0  249.77
#Mann=3,-1,0
  4547.6    0.05       0  5000.1    0.03       0  5006.1    0.05       0
Bank Sta=5000.1,5006.1
Exp/Cntr=0.3,0.1

Type RM Length L Ch R = 1,19295,429,429,429
BEGIN DESCRIPTION:
UNT 205 IN UKCR 19.0
END DESCRIPTION:
XS GIS Cut Line= 3
      3721950.90     10513005.92      3721694.81     10512545.83
      3721236.23     10512204.05
#Sta/Elev= 30
  4368.4  246.43  4478.0  246.28  4638.2  237.17  4689.7  231.11  4711.5  230.75
  4741.2  227.62  4770.9  226.88  4836.1  228.57  4852.1  227.23  4857.8  228.69
  4873.8  227.07  4879.5  228.24  4910.2  227.43  4974.9  223.60  4981.1  221.71
  4995.7  222.13  4999.0  219.64  5001.7  219.14  5005.0  219.64  5016.6  222.40
  5045.8  224.93  5060.4  229.56  5075.0  231.86  5081.2  231.13  5095.8  233.69
  5160.5  239.42  5230.9  242.99  5333.7  248.62  5396.1  247.61  5466.9  249.36
#Mann=5,-1,0
  4368.4    0.05       0  4999.0    0.03       0  5005.0    0.05       0
  5230.9    0.16       0  5333.7    0.05       0
Bank Sta=4999,5005
Exp/Cntr=0.3,0.1

Type RM Length L Ch R = 1,18866,607,607,607
BEGIN DESCRIPTION:
UNT 205 IN UKCR 18.0
END DESCRIPTION:
XS GIS Cut Line= 3
      3722249.58     10512310.18      3721849.61     10512160.19
      3721449.58     10512010.18
#Sta/Elev= 30
  4593.9  250.76  4743.4  247.29  4786.1  244.60  4804.8  244.31  4858.9  239.34
  4890.2  235.87  4903.6  233.02  4914.3  232.98  4925.8  230.24  4967.7  226.08
  4975.7  224.00  4981.0  219.99  4996.7  218.30  4999.5  217.80  5002.7  218.30
  5005.9  218.49  5011.3  223.88  5053.1  224.54  5066.5  223.21  5102.6  225.05
  5127.9  225.41  5146.6  226.72  5192.0  230.91  5224.0  232.57  5274.9  237.52
  5317.4  240.88  5322.8  242.06  5341.5  242.98  5408.2  243.90  5448.3  245.46
#Mann=6,-1,0
  4593.9    0.16       0  4858.9    0.12       0  4996.7    0.07       0
  5002.7    0.12       0  5102.6    0.16       0  5274.9    0.05       0
Bank Sta=4996.7,5002.7
Exp/Cntr=0.3,0.1

Type RM Length L Ch R = 1,18259,358,358,358
BEGIN DESCRIPTION:
UNT 205 IN UKCR 17.0
END DESCRIPTION:
XS GIS Cut Line= 2
      3722408.04     10512059.12      3721651.50     10511614.92
#Sta/Elev= 30
  4472.7  251.47  4654.4  247.20  4718.8  241.82  4786.4  233.45  4814.6  229.64
  4820.4  230.02  4873.2  225.71  4959.1  221.62  4974.8  222.82  4990.4  216.12
  4993.2  216.03  4996.0  215.53  4999.2  216.03  5004.3  219.50  5011.9  222.42
  5039.2  221.99  5054.9  224.63  5070.4  229.32  5085.5  230.70  5092.0  228.89
  5097.8  230.66  5120.3  231.96  5134.9  235.09  5150.6  236.99  5156.4  239.40
  5178.3  241.60  5187.8  243.56  5193.6  243.17  5273.6  250.35  5350.0  251.34
#Mann=5,-1,0
  4472.7    0.16       0  4786.4    0.12       0  4993.2    0.07       0
  4999.2    0.12       0  5070.4    0.05       0
Bank Sta=4993.2,4999.2
Exp/Cntr=0.3,0.1

Type RM Length L Ch R = 1,17901,752,752,752
BEGIN DESCRIPTION:
UNT 205 IN UKCR 16.0
END DESCRIPTION:
XS GIS Cut Line= 3
      3722349.59     10511860.17      3722049.61     10511560.19
      3721649.64     10511410.20
#Sta/Elev= 30
  4593.7  248.58  4678.5  245.23  4720.9  241.65  4749.2  237.57  4777.5  236.84
  4798.2  235.45  4904.8  227.15  4918.9  224.70  4933.1  223.22  4975.5  221.08
  4986.7  217.87  4989.4  217.37  4992.7  217.87  5003.8  218.92  5014.4  220.94
  5033.1  221.07  5056.2  224.89  5071.3  226.55  5103.4  232.34  5113.2  233.19
  5118.5  234.55  5160.3  238.93  5167.5  239.35  5173.7  240.72  5203.9  243.02
  5210.2  244.45  5274.3  249.74  5327.7  250.71  5391.7  250.46  5445.1  248.89
#Mann=6,-1,0
  4593.7    0.16       0  4798.2    0.12       0  4986.7    0.07       0
  4992.7    0.12       0  5056.2    0.16       0  5160.3    0.05       0
Bank Sta=4986.7,4992.7
Exp/Cntr=0.3,0.1

Type RM Length L Ch R = 1,17149,387,387,387
BEGIN DESCRIPTION:
UNT 205 IN UKCR 15.0
END DESCRIPTION:
XS GIS Cut Line= 3
      3722713.63     10511795.26      3722359.45     10511378.58
      3722179.71     10511053.65
#Sta/Elev= 30
  4571.9  252.33  4663.4  250.98  4770.0  245.42  4784.3  242.34  4819.4  240.63
  4876.5  234.35  4883.1  235.19  4911.7  232.00  4919.2  229.93  4932.9  228.89
  4940.2  226.30  4946.8  226.62  4954.5  224.19  4961.1  224.88  4968.8  220.72
  4975.3  223.53  4994.4  214.03  4997.1  213.53  5000.4  214.03  5003.9  218.45
  5149.2  220.59  5250.5  225.32  5310.1  230.91  5322.6  234.15  5381.1  240.75
  5396.9  241.06  5402.8  243.25  5413.2  243.62  5425.5  246.61  5490.1  251.27
#Mann=5,-1,0
  4571.9    0.16       0  4919.2    0.12       0  4994.4    0.07       0
  5000.4    0.12       0  5149.2    0.16       0
Bank Sta=4994.4,5000.4
Exp/Cntr=0.3,0.1

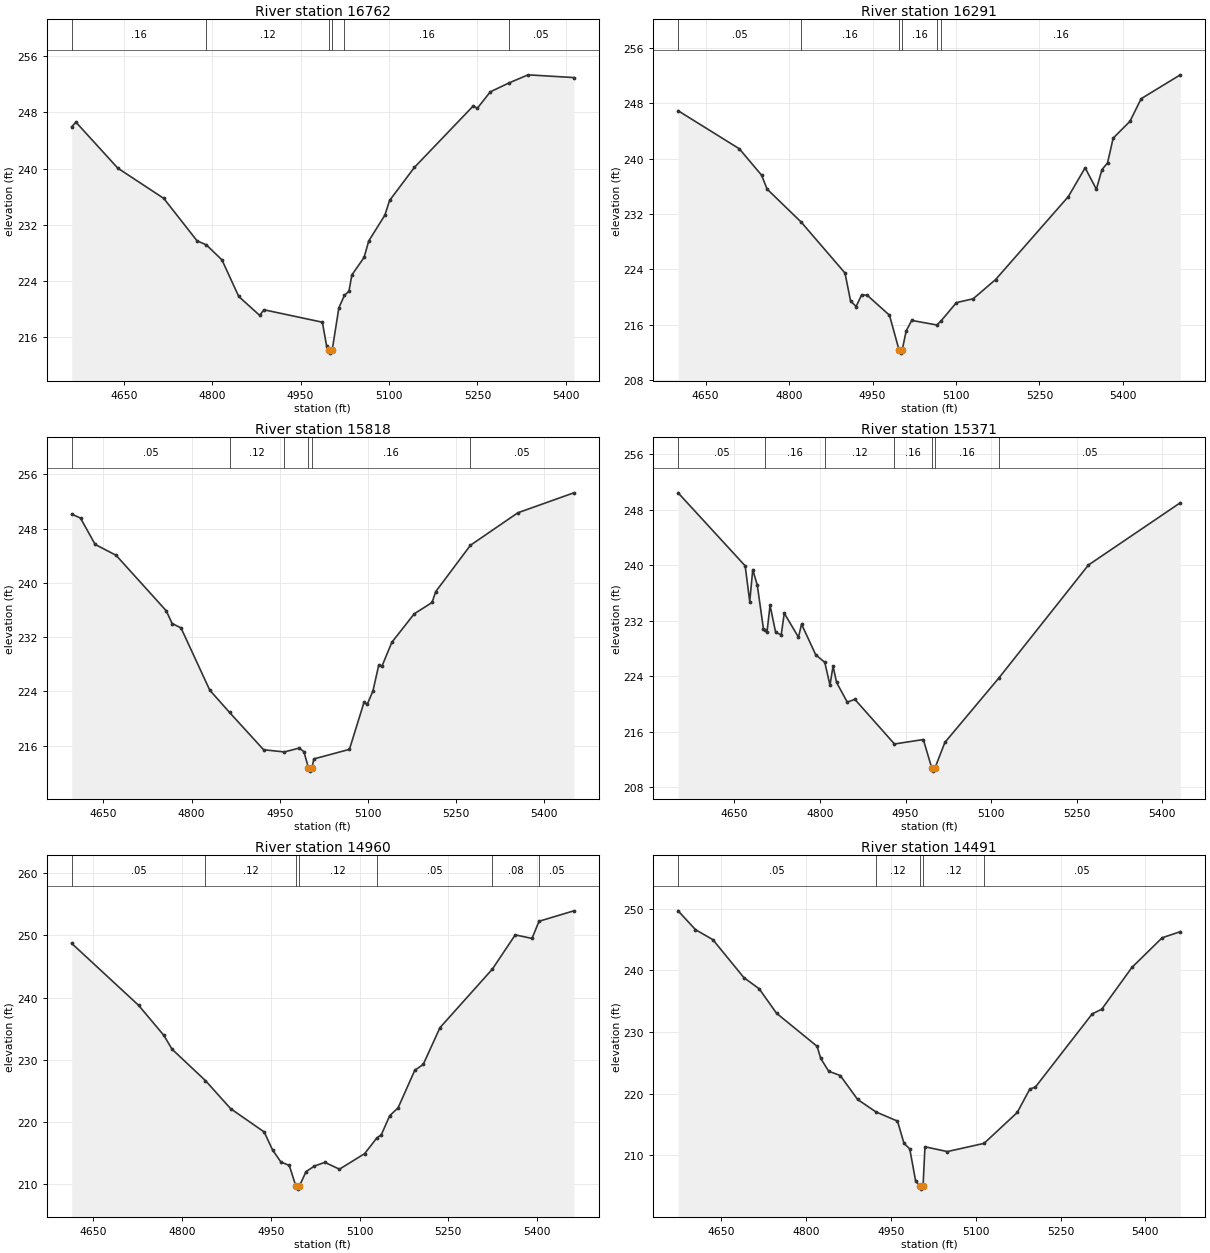
Type RM Length L Ch R = 1,16762,471,471,471
BEGIN DESCRIPTION:
UNT 205 IN UKCR 14.0
END DESCRIPTION:
XS GIS Cut Line= 3
      3722799.64     10511410.21      3722445.68     10511100.51
      3722149.57     10510860.16
#Sta/Elev= 30
  4561.7  245.92  4568.9  246.60  4640.0  240.05  4717.9  235.75  4774.3  229.72
  4790.2  229.13  4816.6  227.00  4845.1  221.79  4880.6  219.10  4887.8  219.90
  4986.9  218.13  4994.1  214.76  4997.7  214.23  5000.5  213.73  5003.7  214.23
  5014.9  220.18  5024.4  221.96  5032.0  222.53  5036.9  224.85  5057.7  227.36
  5065.6  229.70  5092.9  233.36  5100.9  235.45  5142.9  240.15  5243.1  248.93
  5249.5  248.55  5271.7  250.91  5303.0  252.16  5335.8  253.33  5413.4  252.94
#Mann=6,-1,0
  4561.7    0.16       0  4790.2    0.12       0  4997.7    0.07       0
  5003.7    0.12       0  5024.4    0.16       0  5303.0    0.05       0
Bank Sta=4997.7,5003.7
Exp/Cntr=0.3,0.1

Type RM Length L Ch R = 1,16291,473,473,473
BEGIN DESCRIPTION:
UNT 205 IN UKCR 13.0
END DESCRIPTION:
XS GIS Cut Line= 3
      3723149.63     10510910.19      3722699.61     10510910.19
      3722249.60     10510860.19
#Sta/Elev= 30
  4600.5  246.91  4710.5  241.41  4750.5  237.60  4760.5  235.58  4822.0  230.79
  4900.5  223.45  4910.5  219.42  4920.5  218.61  4930.5  220.31  4940.5  220.23
  4980.5  217.35  4997.5  212.37  5000.3  211.87  5003.5  212.37  5010.5  215.09
  5020.5  216.60  5065.5  215.94  5073.1  216.52  5100.8  219.17  5131.0  219.73
  5171.3  222.51  5302.1  234.51  5332.2  238.66  5352.4  235.56  5362.4  238.39
  5372.5  239.37  5382.6  242.95  5412.7  245.37  5432.9  248.65  5503.3  252.10
#Mann=6,-1,0
  4600.5    0.05       0  4822.0    0.16       0  4997.5    0.07       0
  5003.5    0.16       0  5065.5    0.12       0  5073.1    0.16       0
Bank Sta=4997.5,5003.5
Exp/Cntr=0.3,0.1

Type RM Length L Ch R = 1,15818,447,447,447
BEGIN DESCRIPTION:
UNT 205 IN UKCR 12.0
END DESCRIPTION:
XS GIS Cut Line= 3
      3722999.61     10510360.19      3722599.61     10510510.19
      3722199.61     10510660.19
#Sta/Elev= 30
  4596.0  250.15  4611.1  249.55  4636.0  245.67  4671.6  244.07  4757.1  235.87
  4766.9  234.01  4782.0  233.37  4831.0  224.18  4864.7  220.89  4922.6  215.39
  4958.0  215.07  4983.1  215.64  4991.2  215.11  4998.8  212.74  5001.6  212.24
  5004.8  212.74  5008.1  214.04  5068.6  215.45  5093.5  222.41  5098.8  222.07
  5108.6  224.06  5118.4  227.85  5123.8  227.69  5140.7  231.23  5178.9  235.44
  5209.2  237.11  5215.4  238.71  5274.5  245.55  5355.2  250.34  5450.4  253.28
#Mann=6,-1,0
  4596.0    0.05       0  4864.7    0.12       0  4958.0    0.16       0
  4998.8    0.07       0  5004.8    0.16       0  5274.5    0.05       0
Bank Sta=4998.8,5004.8
Exp/Cntr=0.3,0.1

Type RM Length L Ch R = 1,15371,411,411,411
BEGIN DESCRIPTION:
UNT 205 IN UKCR 11.0
END DESCRIPTION:
XS GIS Cut Line= 3
      3722999.62     10510260.19      3722599.61     10510110.19
      3722149.59     10510060.19
#Sta/Elev= 30
  4551.5  250.42  4669.0  239.90  4677.0  234.75  4682.3  239.36  4690.3  237.09
  4701.0  230.82  4704.4  230.59  4707.3  230.40  4712.6  234.21  4722.4  230.32
  4732.2  229.97  4737.5  233.08  4762.4  229.62  4767.8  231.50  4792.7  227.08
  4808.5  226.00  4817.6  222.71  4823.0  225.46  4829.2  223.10  4847.9  220.27
  4861.2  220.67  4930.6  214.24  4981.2  214.88  4995.8  210.83  4998.6  210.33
  5001.8  210.83  5019.0  214.47  5113.9  223.78  5270.5  240.02  5431.5  248.99
#Mann=7,-1,0
  4551.5    0.05       0  4704.4    0.16       0  4808.5    0.12       0
  4930.6    0.16       0  4995.8    0.07       0  5001.8    0.16       0
  5113.9    0.05       0
Bank Sta=4995.8,5001.8
Exp/Cntr=0.3,0.1

Type RM Length L Ch R = 1,14960,469,469,469
BEGIN DESCRIPTION:
UNT 205 IN UKCR 10.0
END DESCRIPTION:
XS GIS Cut Line= 3
      3722949.61     10510010.19      3722649.61     10509710.19
      3722349.63     10509410.21
#Sta/Elev= 30
  4613.6  248.72  4726.7  238.75  4769.2  233.93  4783.3  231.68  4839.7  226.63
  4882.3  222.11  4938.9  218.37  4953.0  215.49  4967.1  213.54  4981.3  212.98
  4992.4  209.67  4995.2  209.17  4998.4  209.67  5009.6  211.98  5023.7  212.88
  5041.4  213.48  5066.1  212.38  5108.6  214.88  5128.9  217.36  5136.9  217.94
  5151.0  220.99  5165.1  222.24  5193.4  228.30  5207.6  229.23  5235.9  235.15
  5324.5  244.58  5363.1  250.08  5391.4  249.51  5403.3  252.27  5462.1  253.95
#Mann=7,-1,0
  4613.6    0.05       0  4839.7    0.12       0  4992.4    0.07       0
  4998.4    0.12       0  5128.9    0.05       0  5324.5    0.08       0
  5403.3    0.05       0
Bank Sta=4992.4,4998.4
Exp/Cntr=0.3,0.1

Type RM Length L Ch R = 1,14491,504,504,504
BEGIN DESCRIPTION:
UNT 205 IN UKCR 9.0
END DESCRIPTION:
XS GIS Cut Line= 3
      3723099.61     10509910.17      3722999.61     10509460.19
      3722599.57     10509310.17
#Sta/Elev= 30
  4573.6  249.66  4604.3  246.61  4635.0  244.99  4690.1  238.81  4717.0  237.02
  4747.7  233.05  4819.4  227.69  4825.8  225.74  4839.9  223.65  4860.4  222.95
  4891.1  219.07  4923.5  217.05  4961.6  215.56  4973.1  211.96  4983.3  211.05
  4993.6  205.90  5000.8  205.03  5003.6  204.53  5006.8  205.03  5010.2  211.40
  5049.7  210.62  5114.7  211.95  5173.4  216.96  5195.6  220.76  5205.4  221.07
  5306.0  232.95  5322.9  233.71  5376.3  240.49  5429.7  245.29  5461.8  246.28
#Mann=5,-1,0
  4573.6    0.05       0  4923.5    0.12       0  5000.8    0.07       0
  5006.8    0.12       0  5114.7    0.05       0
Bank Sta=5000.8,5006.8
Exp/Cntr=0.3,0.1

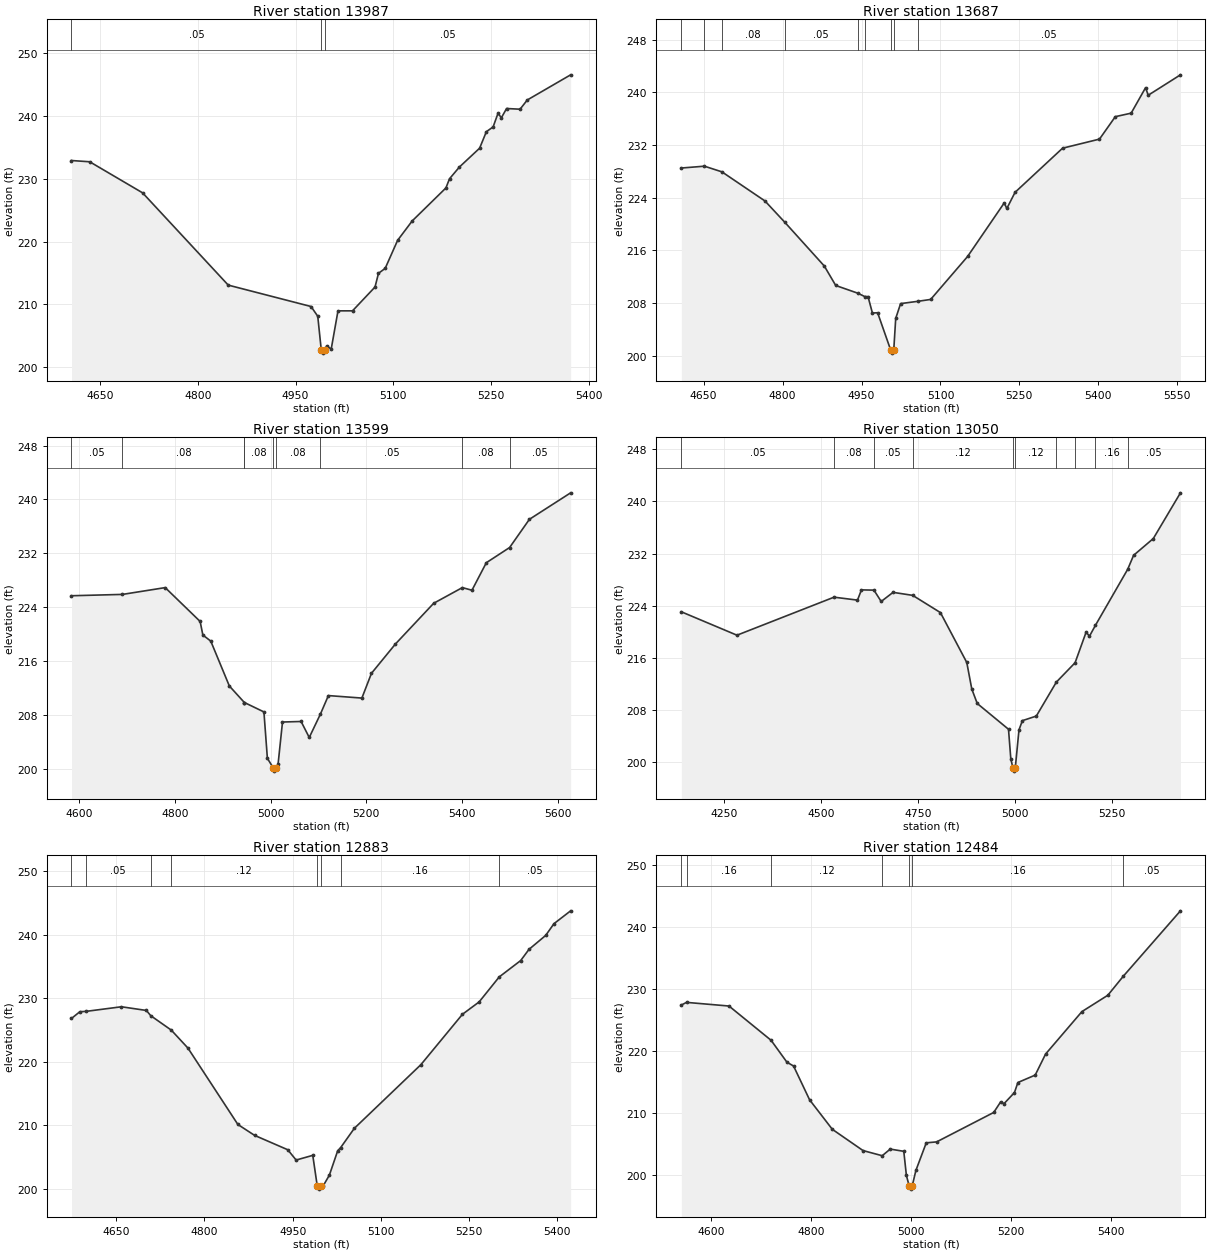
Type RM Length L Ch R = 1,13987,300,300,300
BEGIN DESCRIPTION:
UNT 205 IN UKCR 8.0
END DESCRIPTION:
XS GIS Cut Line= 3
      3723357.59     10509450.70      3723188.30     10509145.98
      3722784.65     10509036.60
#Sta/Elev= 30
  4605.7  232.92  4633.7  232.72  4714.9  227.77  4846.5  213.06  4973.7  209.65
  4984.0  208.10  4989.4  202.72  4992.1  202.22  4995.4  202.72  4997.5  203.35
  5004.7  202.88  5015.1  208.96  5037.4  208.96  5072.0  212.76  5077.3  214.94
  5087.6  215.73  5106.7  220.20  5129.1  223.29  5180.9  228.55  5186.4  230.01
  5201.6  231.88  5232.7  234.89  5243.0  237.51  5253.4  238.28  5260.9  240.44
  5266.1  239.74  5274.1  241.21  5294.8  241.10  5305.9  242.57  5372.5  246.58
#Mann=3,-1,0
  4605.7    0.05       0  4989.4    0.03       0  4995.4    0.05       0
Bank Sta=4989.4,4995.4
Exp/Cntr=0.3,0.1

Type RM Length L Ch R = 1,13687,88,88,88
BEGIN DESCRIPTION:
Mapping XS 69b0f7c8
END DESCRIPTION:
XS GIS Cut Line= 4
      3723548.11     10509185.90      3723285.52     10508947.19
      3723196.55     10508897.28      3722706.12     10508860.39
#Sta/Elev= 30
  4607.5  228.51  4651.4  228.79  4684.7  227.93  4766.5  223.51  4803.8  220.31
  4879.3  213.63  4901.0  210.68  4942.9  209.51  4956.1  209.00  4962.4  208.98
  4970.7  206.50  4980.6  206.54  5005.3  200.91  5008.1  200.41  5011.3  200.91
  5015.0  205.68  5024.3  207.93  5056.6  208.27  5081.4  208.56  5151.6  215.08
  5221.2  223.21  5226.2  222.37  5241.8  224.82  5332.1  231.52  5402.3  232.90
  5432.4  236.31  5462.5  236.84  5489.9  240.71  5494.9  239.56  5556.2  242.66
#Mann=9,-1,0
  4607.5    0.08       0  4651.4    0.05       0  4684.7    0.08       0
  4803.8    0.05       0  4942.9    0.16       0  4956.1    0.08       0
  5005.3    0.07       0  5011.3    0.08       0  5056.6    0.05       0
Bank Sta=5005.3,5011.3
Exp/Cntr=0.3,0.1

Type RM Length L Ch R = 1,13599,549,549,549
BEGIN DESCRIPTION:
UNT 205 IN UKCR 7.0
END DESCRIPTION:
XS GIS Cut Line= 3
      3723673.97     10509047.56      3723248.63     10508830.00
      3722683.44     10508821.34
#Sta/Elev= 30
  4584.0  225.68  4690.5  225.88  4779.8  226.89  4852.8  221.86  4858.5  219.84
  4875.0  218.94  4913.8  212.27  4945.2  209.81  4945.3  209.81  4986.1  208.41
  4993.3  201.52  5005.3  200.11  5008.0  199.61  5011.3  200.11  5015.7  200.67
  5024.9  206.91  5063.8  206.99  5080.8  204.61  5104.2  208.10  5120.8  210.84
  5190.8  210.47  5210.8  214.15  5260.8  218.50  5340.8  224.56  5400.7  226.89
  5420.8  226.50  5450.8  230.59  5499.5  232.85  5540.8  237.04  5627.0  240.98
#Mann=9,-1,0
  4584.0    0.05       0  4690.5    0.08       0  4945.2    0.12       0
  4945.3    0.08       0  5005.3    0.07       0  5011.3    0.08       0
  5104.2    0.05       0  5400.7    0.08       0  5499.5    0.05       0
Bank Sta=5005.3,5011.3
Exp/Cntr=0.3,0.1

Type RM Length L Ch R = 1,13050,167,167,167
BEGIN DESCRIPTION:
Mapping XS 9acb5d2b
END DESCRIPTION:
XS GIS Cut Line= 4
      3723774.21     10508685.03      3723373.20     10508502.75
      3723128.41     10508455.87      3722636.23     10508794.41
#Sta/Elev= 30
  4139.7  223.08  4283.2  219.49  4533.5  225.32  4594.0  224.87  4604.2  226.44
  4636.4  226.40  4655.1  224.66  4685.7  226.06  4736.3  225.60  4807.8  222.96
  4875.8  215.31  4888.7  211.24  4902.8  209.02  4983.4  205.07  4989.4  200.49
  4994.9  199.15  4997.6  198.65  5000.9  199.15  5010.4  204.97  5019.2  206.39
  5055.1  207.09  5106.8  212.30  5155.1  215.27  5183.6  219.97  5192.1  219.33
  5207.6  221.01  5290.7  229.59  5306.0  231.74  5356.8  234.31  5426.8  241.32
#Mann=10,-1,0
  4139.7    0.05       0  4533.5    0.08       0  4636.4    0.05       0
  4736.3    0.12       0  4994.9    0.07       0  5000.9    0.12       0
  5106.8    0.16       0  5155.1    0.12       0  5207.6    0.16       0
  5290.7    0.05       0
Bank Sta=4994.9,5000.9
Exp/Cntr=0.3,0.1

Type RM Length L Ch R = 1,12883,399,399,399
BEGIN DESCRIPTION:
UNT 205 IN UKCR 6.0
END DESCRIPTION:
XS GIS Cut Line= 3
      3723149.63     10508160.17      3722849.61     10508460.19
      3722549.58     10508760.22
#Sta/Elev= 30
  4573.9  226.80  4588.1  227.86  4598.2  227.91  4658.8  228.64  4701.2  228.06
  4708.7  227.23  4743.6  224.96  4771.9  222.13  4856.8  210.10  4885.1  208.39
  4941.6  206.12  4955.8  204.50  4984.1  205.24  4991.7  200.42  4994.4  199.92
  4997.7  200.42  5001.7  200.42  5012.3  202.12  5026.5  205.97  5031.5  206.46
  5054.8  209.50  5167.9  219.52  5238.6  227.46  5266.9  229.40  5301.1  233.34
  5337.6  235.92  5351.7  237.68  5380.0  239.87  5394.2  241.73  5422.5  243.75
#Mann=8,-1,0
  4573.9    0.08       0  4598.2    0.05       0  4708.7    0.16       0
  4743.6    0.12       0  4991.7    0.07       0  4997.7    0.12       0
  5031.5    0.16       0  5301.1    0.05       0
Bank Sta=4991.7,4997.7
Exp/Cntr=0.3,0.1

Type RM Length L Ch R = 1,12484,346,346,346
BEGIN DESCRIPTION:
UNT 205 IN UKCR 5.0
END DESCRIPTION:
XS GIS Cut Line= 3
      3723049.63     10508010.18      3722649.61     10508160.19
      3722499.61     10508710.18
#Sta/Elev= 30
  4540.7  227.45  4551.1  227.88  4636.0  227.29  4720.1  221.76  4751.7  218.23
  4765.0  217.61  4797.0  212.16  4842.4  207.40  4903.8  203.97  4942.1  203.14
  4958.1  204.21  4985.2  203.85  4990.4  199.97  4996.0  198.25  4998.8  197.75
  5002.0  198.25  5009.4  200.77  5030.1  205.22  5050.8  205.37  5164.9  210.12
  5178.7  211.82  5185.6  211.55  5206.3  213.33  5213.2  214.95  5247.8  216.15
  5268.5  219.54  5341.1  226.39  5392.9  229.03  5423.9  232.11  5538.0  242.65
#Mann=7,-1,0
  4540.7    0.05       0  4551.1    0.16       0  4720.1    0.12       0
  4942.1    0.16       0  4996.0    0.07       0  5002.0    0.16       0
  5423.9    0.05       0
Bank Sta=4996,5002
Exp/Cntr=0.3,0.1

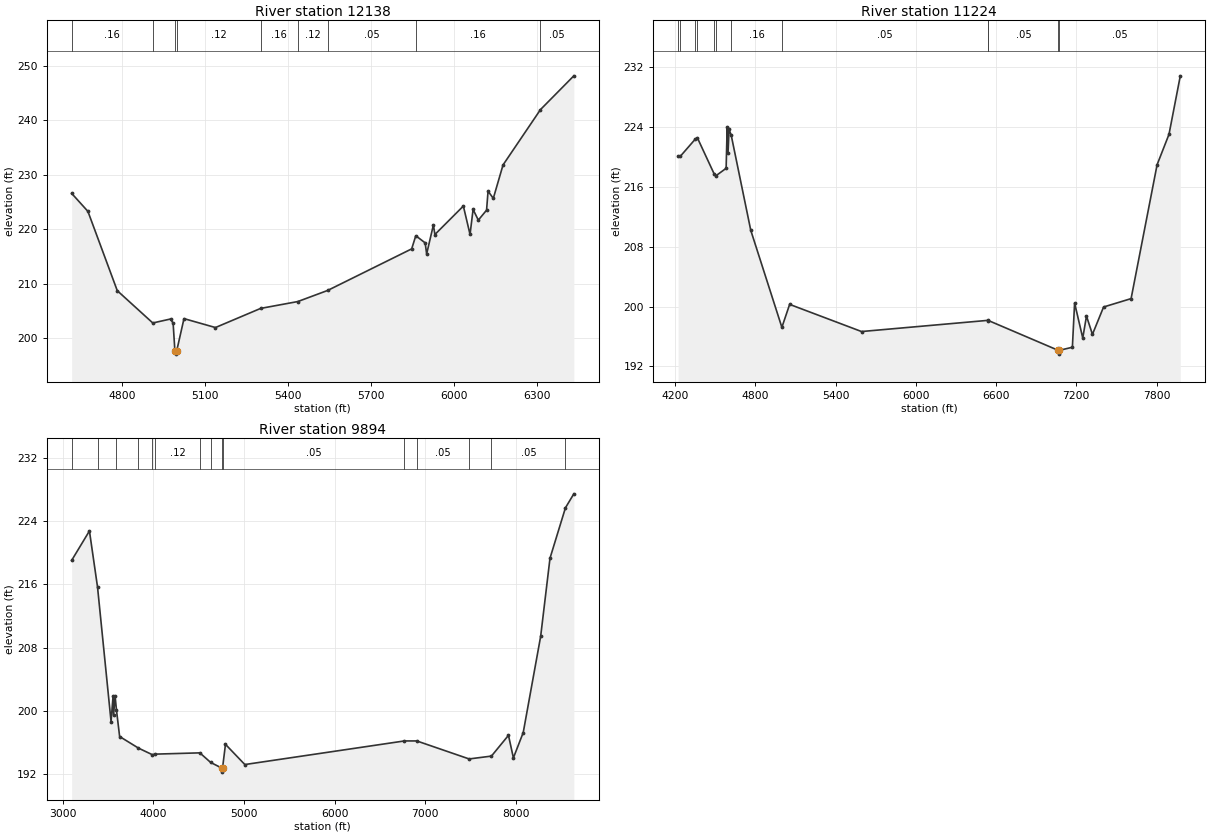
Type RM Length L Ch R = 1,12138,914,914,914
BEGIN DESCRIPTION:
UNT 205 IN UKCR 4.0
END DESCRIPTION:
XS GIS Cut Line= 3
      3722749.62     10507710.19      3722469.40     10507849.77
      3721919.41     10509249.76
#Sta/Elev= 30
  4617.1  226.59  4675.9  223.28  4782.2  208.69  4910.7  202.75  4974.8  203.48
  4984.3  202.71  4990.8  197.52  4993.6  197.02  4996.8  197.52  5023.6  203.55
  5137.4  201.91  5301.0  205.43  5435.4  206.69  5543.3  208.73  5847.5  216.38
  5862.4  218.80  5896.3  217.48  5901.7  215.45  5926.1  220.78  5931.5  219.02
  6034.5  224.26  6058.7  219.03  6069.7  223.63  6088.7  221.67  6118.5  223.50
  6123.9  227.00  6142.9  225.67  6178.1  231.82  6313.6  242.00  6434.3  248.21
#Mann=9,-1,0
  4617.1    0.16       0  4910.7    0.12       0  4990.8    0.07       0
  4996.8    0.12       0  5301.0    0.16       0  5435.4    0.12       0
  5543.3    0.05       0  5862.4    0.16       0  6313.6    0.05       0
Bank Sta=4990.8,4996.8
Exp/Cntr=0.3,0.1

Type RM Length L Ch R = 1,11224,1330,1330,1330
BEGIN DESCRIPTION:
UNT 205 IN UKCR 3.0
END DESCRIPTION:
XS GIS Cut Line= 4
      3723158.65     10507847.92      3722390.39     10507183.82
      3721947.68     10507235.91      3720906.02     10509280.15
#Sta/Elev= 30
  4221.9  220.12  4239.2  220.10  4348.3  222.34  4365.6  222.57  4492.1  217.70
  4505.4  217.49  4581.0  218.48  4588.6  223.96  4595.2  220.57  4602.9  223.67
  4618.6  222.93  4765.2  210.19  4997.9  197.22  5055.9  200.29  5593.5  196.66
  6542.4  198.16  6542.6  198.13  7065.4  194.14  7068.2  193.64  7071.4  194.14
  7170.4  194.56  7187.0  200.47  7248.0  195.79  7275.9  198.73  7320.4  196.28
  7403.7  199.94  7609.5  201.06  7804.0  218.96  7892.9  223.02  7977.5  230.84
#Mann=12,-1,0
  4221.9    0.05       0  4239.2     0.1       0  4348.3    0.05       0
  4365.6     0.1       0  4492.1    0.16       0  4505.4    0.08       0
  4618.6    0.16       0  4997.9    0.05       0  6542.4    0.16       0
  6542.6    0.05       0  7065.4    0.03       0  7071.4    0.05       0
Bank Sta=7065.4,7071.4
Exp/Cntr=0.3,0.1

Type RM Length L Ch R = 1,9894,0,0,0
BEGIN DESCRIPTION:
UNT 205 IN UKCR 2.0
END DESCRIPTION:
XS GIS Cut Line= 5
      3723223.70     10507470.25      3722533.61     10506116.12
      3721973.72     10506363.51      3721309.66     10507613.51
      3720580.55     10509475.34
#Sta/Elev= 30
  3096.7  219.04  3293.1  222.77  3382.5  215.67  3532.0  198.63  3554.3  201.88
  3559.9  199.46  3576.5  201.88  3591.2  200.15  3626.6  196.74  3834.9  195.27
  3987.5  194.44  4022.1  194.51  4512.6  194.67  4631.8  193.46  4757.1  192.73
  4759.9  192.23  4763.1  192.73  4795.8  195.75  5009.6  193.19  6773.1  196.18
  6908.4  196.18  7486.8  193.90  7733.5  194.26  7921.7  196.89  7975.9  194.03
  8084.5  197.24  8277.1  209.42  8380.3  219.32  8550.9  225.70  8643.6  227.47
#Mann=15,-1,0
  3096.7    0.05       0  3382.5    0.16       0  3591.2    0.12       0
  3834.9    0.16       0  3987.5    0.05       0  4022.1    0.12       0
  4512.6    0.16       0  4631.8    0.05       0  4757.1    0.03       0
  4763.1    0.05       0  6773.1    0.16       0  6908.4    0.05       0
  7486.8    0.07       0  7733.5    0.05       0  8550.9    0.16       0
Bank Sta=4757.1,4763.1
Exp/Cntr=0.3,0.1

Chan Stop Cuts=-1