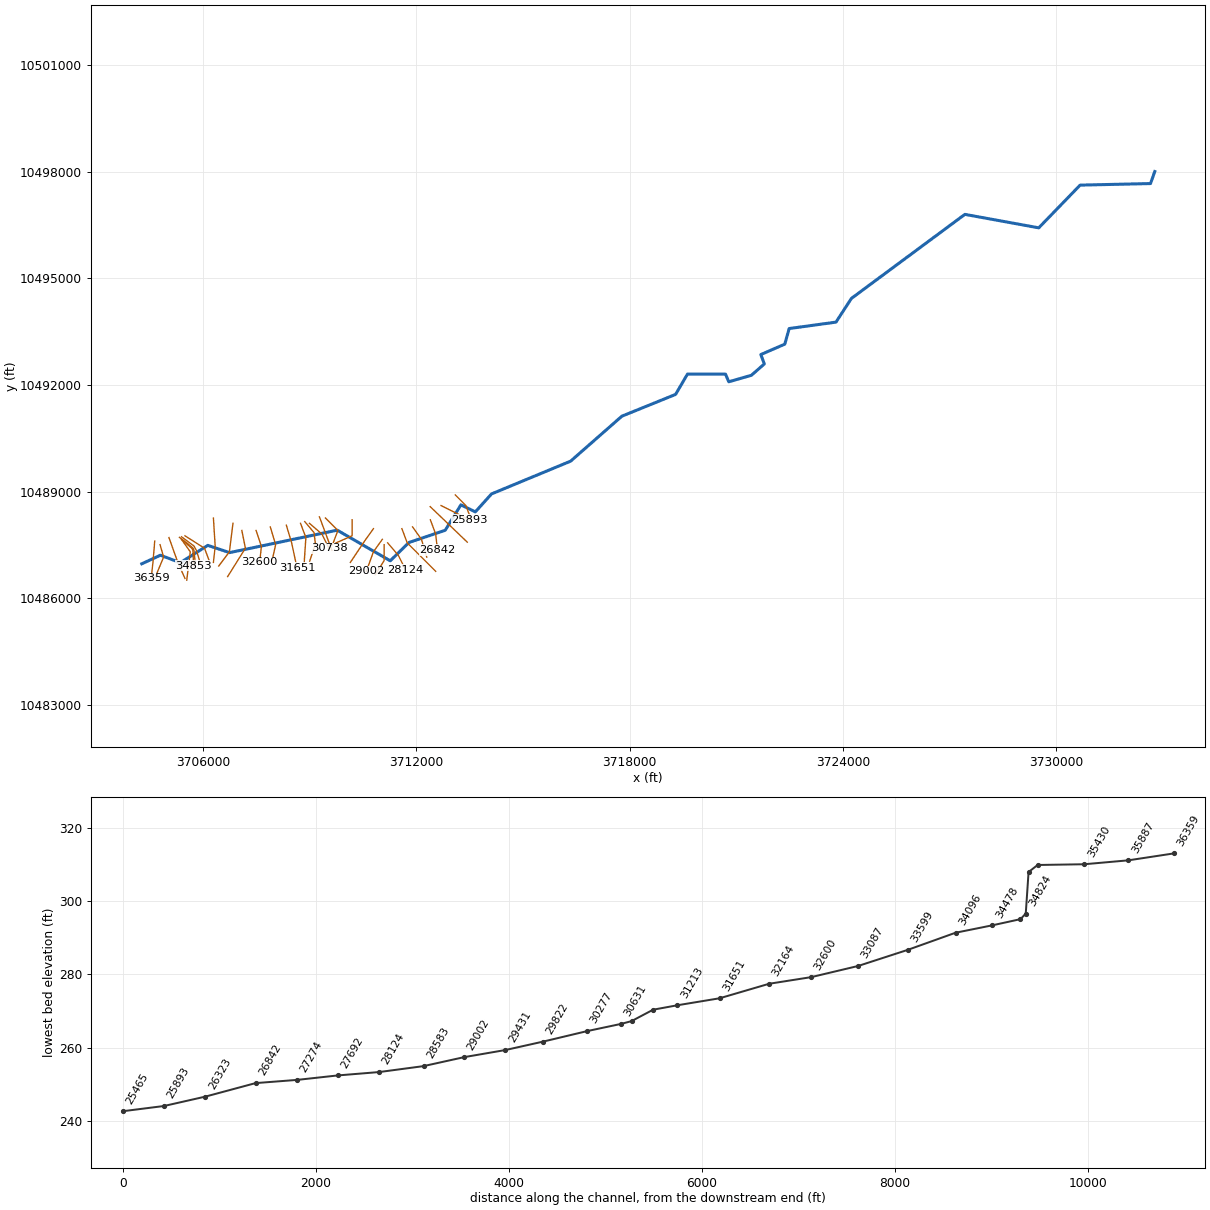
--- UNT 206 IN UKCR.prj (project) ---

Proj Title=UNT 206 IN UKCR Base Level Engineering
Current Plan=p01
Default Exp/Contr=0.3,0.1
English Units
Geom File=g01
Flow File=f01
Plan File=p01
Y Axis Title=Elevation
X Axis Title(PF)=Main Channel Distance
X Axis Title(XS)=Station
BEGIN DESCRIPTION:
UNT 206 IN UKCR
END DESCRIPTION:
DSS Export Rating Curves= 0
DSS Export Rating Curve Sorted= 0
DSS Export Volume Flow Curves= 0
DXF OffsetX= 0
DXF OffsetY= 0
DXF ScaleX= 1
DXF ScaleY= 10

--- UNT 206 IN UKCR.p01 (plan) ---

Plan Title=Multiple Run
Short Identifier=Multiple
Geom File=g01
Flow File=f01
Subcritical Flow
K Sum by GR= 0
Std Step Tol= 0.01
Critical Tol= 0.01
Num of Std Step Trials= 20
Max Error Tol= 0.3
Flow Tol Ratio= 0.001
Split Flow NTrial= 30
Split Flow Tol= 0.02
Split Flow Ratio= 0.02
Log Output Level= 0
Friction Slope Method= 1
Unsteady Friction Slope Method= 2
Unsteady Bridges Friction Slope Method= 1
Parabolic Critical Depth
Global Vel Dist=  1 , 1 , 1
Global Log Level= 0
CheckData=True
Encroach Param= -1, 0, 0, 0
BEGIN DESCRIPTION:
Multiple Run
END DESCRIPTION:

--- UNT 206 IN UKCR.f01 (steady flow) ---

Flow Title=Multiple
Program Version=4.10
Number of Profiles= 7
Profile Names=10-year,25-year,50-year,1pct_min,100-year,1pct_plu,500-year
River Rch & RM=UNT 206 IN UKCR,Reach-1         ,36359
     504     655     773     527     894    1260    1186
River Rch & RM=UNT 206 IN UKCR,Reach-1         ,34947
     784    1019    1200     819    1388    1957    1841
River Rch & RM=UNT 206 IN UKCR,Reach-1         ,31651
    1019    1324    1559    1064    1803    2543    2391
River Rch & RM=UNT 206 IN UKCR,Reach-1         ,25893
    1258    1634    1923    1313    2225    3137    2950
River Rch & RM=UNT 206 IN UKCR,Reach-1         ,16869
    1558    2023    2381    1625    2754    3884    3650
River Rch & RM=UNT 206 IN UKCR,Reach-1         ,13550
    1958    2542    2989    2041    3459    4877    4582
Boundary for River Rch & Prof#=UNT 206 IN UKCR,Reach-1         , 1
Up Type= 0
Dn Type= 3
Dn Slope=0.002
Boundary for River Rch & Prof#=UNT 206 IN UKCR,Reach-1         , 2
Up Type= 0
Dn Type= 3
Dn Slope=0.002
Boundary for River Rch & Prof#=UNT 206 IN UKCR,Reach-1         , 3
Up Type= 0
Dn Type= 3
Dn Slope=0.002
Boundary for River Rch & Prof#=UNT 206 IN UKCR,Reach-1         , 4
Up Type= 0
Dn Type= 3
Dn Slope=0.002
Boundary for River Rch & Prof#=UNT 206 IN UKCR,Reach-1         , 5
Up Type= 0
Dn Type= 3
Dn Slope=0.002
Boundary for River Rch & Prof#=UNT 206 IN UKCR,Reach-1         , 6
Up Type= 0
Dn Type= 3
Dn Slope=0.002
Boundary for River Rch & Prof#=UNT 206 IN UKCR,Reach-1         , 7
Up Type= 0
Dn Type= 3
Dn Slope=0.002
DSS Import GetInterval= 0
DSS Import GetPeak= 0
DSS Import FillOption= 0

--- UNT 206 IN UKCR.g01 (geometry) ---

Geom Title=Existing Conditions
Program Version=4.10

River Reach=UNT 206 IN UKCR ,Reach-1
Reach XY= 30
       3704286.5       10486972.      3704809.75       10487213.
        3705368.       10487003.      3706142.25       10487490.
      3706753.25       10487286.       3709780.5       10487918.
       3711272.5       10487056.        3711798.       10487571.
        3712818.       10487915.      3713259.25       10488631.
        3713664.       10488432.      3714120.75       10488938.
       3716344.5       10489860.      3717785.25       10491125.
      3719295.75       10491738.        3719630.       10492310.
      3720699.75       10492309.      3720790.75       10492093.
        3721427.       10492276.      3721790.75       10492595.
       3721692.5       10492859.      3722365.75       10493152.
      3722489.25       10493591.      3723806.25       10493772.
       3724239.5       10494439.       3727430.5       10496804.
      3729507.25       10496425.      3730670.75       10497627.
      3732650.25       10497671.       3732769.5       10498010.

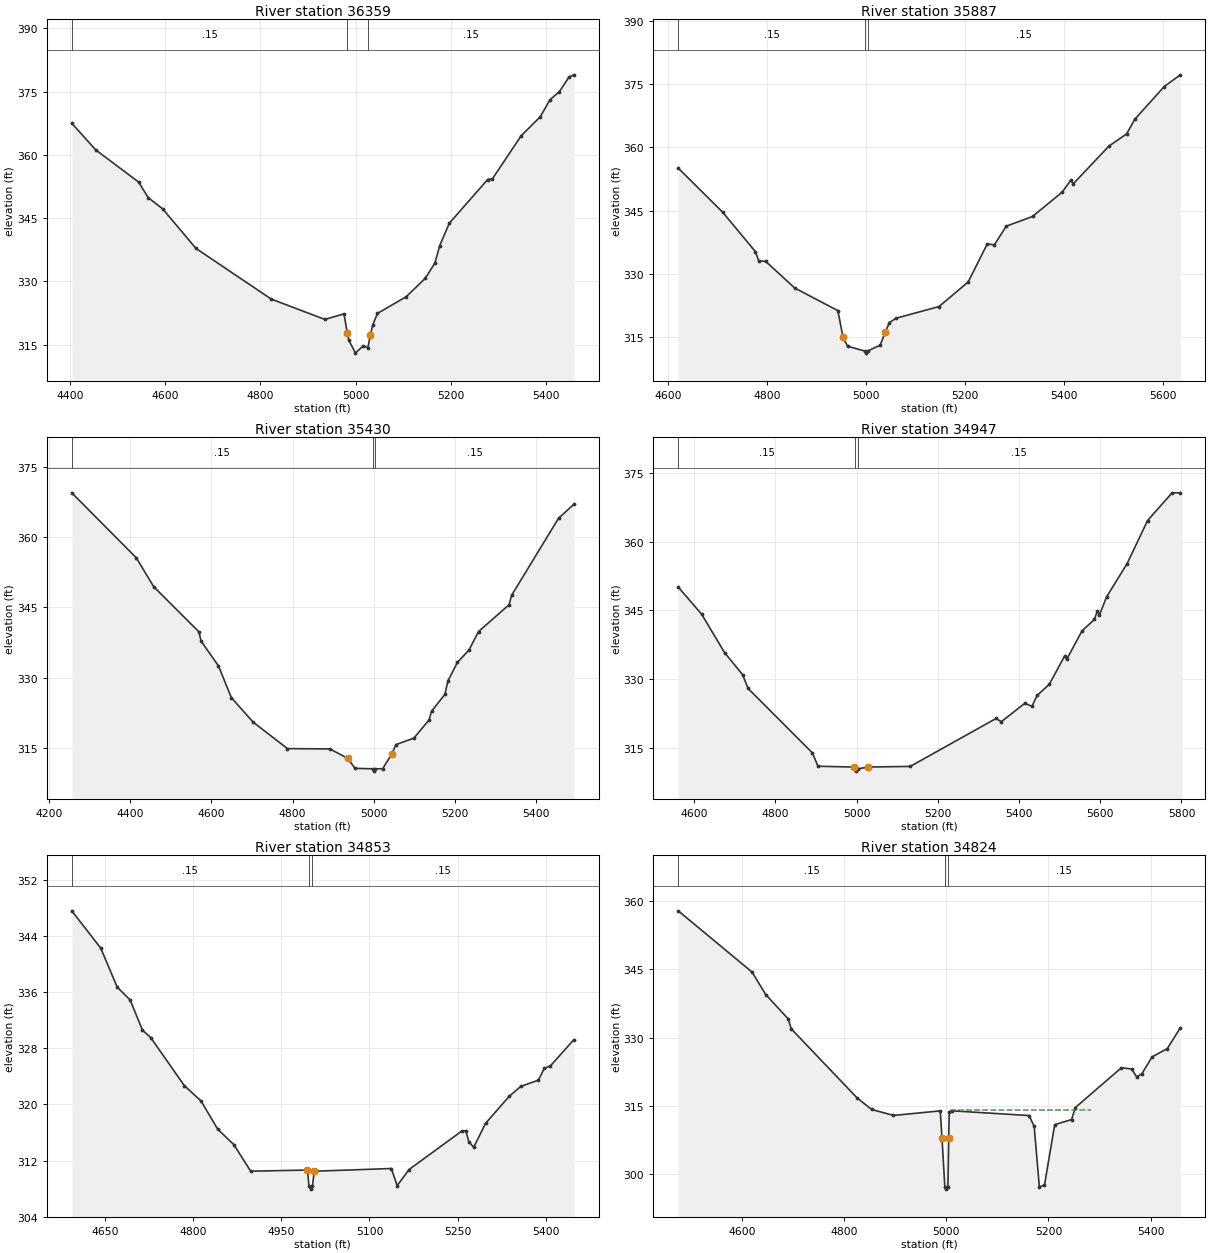
Type RM Length L Ch R = 1 ,36359   ,472,472,472
BEGIN DESCRIPTION:
UNT 206 IN UKCR 67.0
END DESCRIPTION:
XS GIS Cut Line= 3
      3704649.61      10487610.2      3704599.61     10487010.19
      3704549.61     10486560.15
#Sta/Elev= 30
  4403.7  367.49  4453.9  361.19  4544.2  353.55  4564.3  349.86  4594.4  347.24
  4664.6  337.83  4822.7  325.83  4935.6  320.99  4975.7  322.33 4982.68  317.67
  4985.7   316.1  4999.8  313.01  5015.9  314.74  5025.9   314.3  5031.1  317.31
    5036  319.68    5046  322.42  5106.4  326.39  5146.7  330.77  5166.8   334.4
  5176.8  338.49    5197   343.8  5277.5  354.16  5287.5  354.32  5347.9  364.53
  5388.1  369.03  5408.3  373.04  5428.4  375.01  5448.5  378.46  5458.6  378.97
#Mann= 3 ,-1 , 0
  4403.7     .15       0 4982.68     .05       0  5025.9     .15       0
Bank Sta=4982.68,5031.1
XS Rating Curve= 0 ,0
Exp/Cntr=0.3,0.1

Type RM Length L Ch R = 1 ,35887   ,457,457,457
BEGIN DESCRIPTION:
UNT 206 IN UKCR 66.0
END DESCRIPTION:
XS GIS Cut Line= 3
      3704799.62     10487510.16      3704899.61     10487160.19
       3704649.6     10486560.17
#Sta/Elev= 30
  4620.4  355.09  4710.1  344.61  4776.4  335.23  4782.9  333.05  4797.2  332.91
  4855.7  326.59  4942.8  321.22  4953.2   314.9  4962.3  312.76    4997  311.62
  4999.8  311.12    5003  311.62  5028.3  313.01  5038.5  316.11  5046.7  318.36
  5060.2  319.41  5146.9  322.18  5205.9  328.01  5244.4  337.05    5259  336.87
  5282.8  341.28  5335.9  343.59    5396  349.39  5412.8  352.15  5418.3  351.36
  5489.8  360.27    5526  363.22  5542.8  366.74  5601.9  374.46  5634.4  377.25
#Mann= 3 ,-1 , 0
  4620.4     .15       0    4997     .05       0    5003     .15       0
Bank Sta=4953.2,5038.5
XS Rating Curve= 0 ,0
Exp/Cntr=0.3,0.1

Type RM Length L Ch R = 1 ,35430   ,483,483,483
BEGIN DESCRIPTION:
UNT 206 IN UKCR 65.0
END DESCRIPTION:
XS GIS Cut Line= 3
       3705049.6      10487710.2      3705299.61     10487010.19
      3705499.62     10486560.15
#Sta/Elev= 30
  4256.3  369.48  4415.1  355.61  4458.1  349.42    4569  339.82  4574.9  337.79
  4617.4  332.51  4649.2  325.73  4702.3  320.54  4787.2  314.86  4891.8  314.79
  4935.9  312.76  4953.4  310.64    4997  310.55  4999.8  310.05    5003  310.55
  5021.5  310.56  5043.4  313.62  5054.3  315.72  5098.1  317.08  5135.7  320.98
  5141.9  322.85  5174.7  326.44  5182.2  329.33  5205.5  333.26  5234.2  335.95
  5257.5  339.86  5332.7  345.58  5338.9  347.59  5454.4  364.04  5492.1  367.03
#Mann= 3 ,-1 , 0
  4256.3     .15       0    4997     .05       0    5003     .15       0
Bank Sta=4935.9,5043.4
XS Rating Curve= 0 ,0
Exp/Cntr=0.3,0.1

Type RM Length L Ch R = 1 ,34947   ,94,94,94
BEGIN DESCRIPTION:
UNT 206 IN UKCR 64.0
END DESCRIPTION:
XS GIS Cut Line= 3
      3705399.63     10487660.15      3705649.61     10487310.19
      3705549.61     10486510.19
#Sta/Elev= 30
  4560.9  350.13  4618.6  344.18  4675.1  335.78  4719.4  330.95  4732.9  327.94
  4891.4  313.83    4905  310.92  4993.5  310.74    4997  310.35  4999.8  309.85
    5003  310.35  5028.8  310.75  5132.1  310.88  5343.7  321.38  5356.3  320.66
  5414.2  324.69  5431.9  324.03  5444.5  326.41  5474.7  328.86  5512.5  335.07
  5517.5  334.32  5555.3  340.56  5585.6  343.04  5593.1   344.9  5598.2  344.04
  5615.8  348.01  5666.2  355.26  5716.6  364.69    5777  370.75  5797.2  370.75
#Mann= 3 ,-1 , 0
  4560.9     .15       0    4997     .05       0    5003     .15       0
Bank Sta=4993.5,5028.8
XS Rating Curve= 0 ,0
Exp/Cntr=0.3,0.1

Type RM Length L Ch R = 1 ,34853   ,29,29,29
BEGIN DESCRIPTION:
Mapping XS ee1f3674
END DESCRIPTION:
XS GIS Cut Line= 5
      3705422.55     10487642.74      3705695.98     10487404.03
      3705722.02     10487354.11      3705728.53      10487260.8
      3705741.55     10486920.06
#Sta/Elev= 30
  4593.7   347.6  4642.9  342.29    4671  336.72  4692.9   334.9  4713.8  330.61
    4728  329.52    4785  322.69  4813.4   320.5  4841.9  316.47  4869.4  314.26
  4897.9  310.48 4994.55  310.64    4997  308.42  4999.8  307.92    5003  308.42
  5006.1  310.47  5137.1  310.86  5147.1  308.42  5167.2  310.71  5257.2  316.22
  5263.9  316.24  5268.9  314.69  5277.2  313.89  5297.3  317.29  5337.3  321.13
  5357.3  322.57  5387.3  323.46  5397.3  325.15  5407.3  325.46  5447.5  329.23
#Mann= 3 ,-1 , 0
  4593.7     .15       0    4997     .05       0    5003     .15       0
Bank Sta=4994.55,5006.1
XS Rating Curve= 0 ,0
Exp/Cntr=0.3,0.1

Type RM Length L Ch R = 1 ,34824   ,55,55,55
BEGIN DESCRIPTION:
Mapping XS dbb2a034
END DESCRIPTION:
XS GIS Cut Line= 6
      3705344.41     10487716.53      3705613.52     10487510.36
      3705726.36     10487412.71       3705752.4     10487356.28
      3705780.62     10487080.68      3705787.11     10486924.84
#Sta/Elev= 30
  4474.8  357.93  4619.3  344.44  4646.4  339.45    4690  334.13  4696.3   331.9
  4825.1   316.7  4853.6  314.15  4896.4  312.83    4988  313.84 4991.43  307.86
    4997  297.09  4999.8  296.59    5003  297.09 5004.63  307.83  5005.5  313.58
    5011  313.85    5162  312.81    5172  310.41  5182.1  297.09  5192.1  297.47
  5212.2   310.8  5245.3  311.92  5252.5  314.56  5342.8  323.34  5362.8  323.07
  5372.8  321.32  5382.8     322    5403  325.74  5432.8  327.58  5458.2  332.13
#Mann= 3 ,-1 , 0
  4474.8     .15       0    4997     .05       0    5003     .15       0
#XS Ineff= 1 ,-1
 5009.55 5283.64  314.13
Permanent Ineff=
       F
Bank Sta=4991.43,5004.63
XS Rating Curve= 0 ,0
Exp/Cntr=0.3,0.1

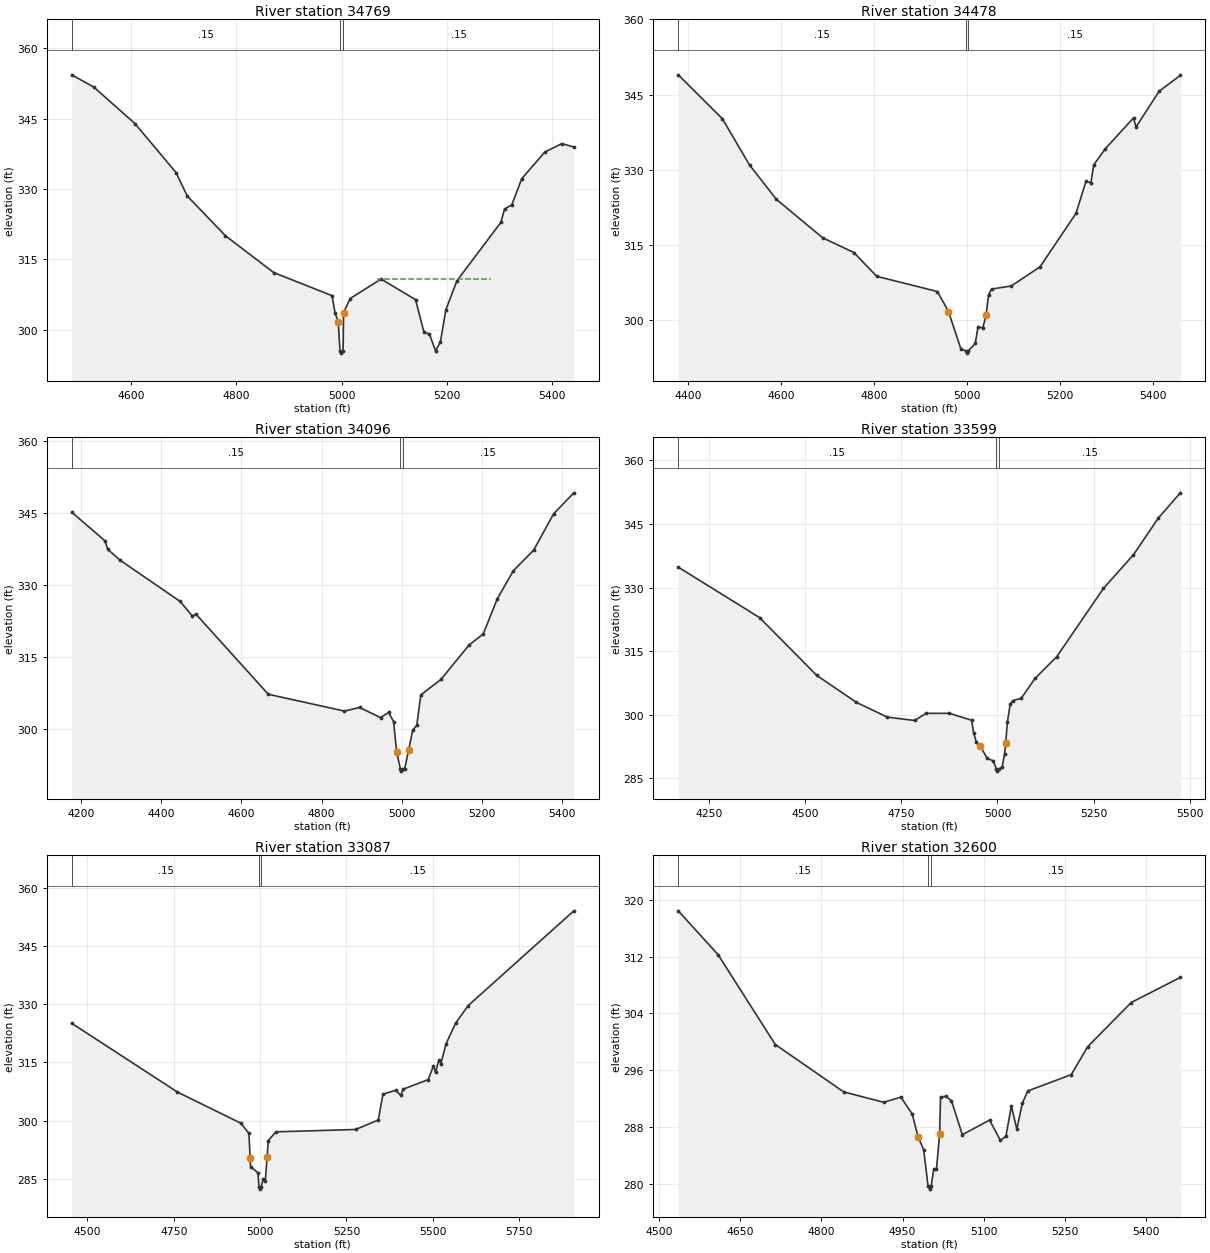
Type RM Length L Ch R = 1 ,34769   ,291,291,291
BEGIN DESCRIPTION:
Mapping XS e5485f52
END DESCRIPTION:
XS GIS Cut Line= 4
      3705403.04      10487731.7      3705754.57      10487471.3
      3705824.02     10487343.26      3705932.52     10486987.37
#Sta/Elev= 30
  4486.8  354.32  4528.7  351.71    4607  343.94  4685.2  333.51  4706.5  328.52
  4779.2  320.05  4870.9  312.22    4982  307.29  4987.7   303.6  4993.8  301.77
    4997  295.56  4999.8  295.06    5003  295.56  5003.9  303.67  5016.5  306.69
  5075.2  310.84  5140.8  306.45  5156.8  299.55  5167.2  299.11  5178.9  295.56
  5188.1  297.42  5198.6  304.31  5219.5  310.45  5303.1   322.9  5310.2  325.73
  5324.1  326.67    5343  332.23  5386.8  337.87  5419.1  339.67    5442  338.95
#Mann= 3 ,-1 , 0
  4486.8     .15       0    4997     .05       0    5003     .15       0
#XS Ineff= 1 ,-1
 5070.23 5284.32  310.85
Permanent Ineff=
       F
Bank Sta=4993.8,5003.9
XS Rating Curve= 0 ,0
Exp/Cntr=0.3,0.1

Type RM Length L Ch R = 1 ,34478   ,382,382,382
BEGIN DESCRIPTION:
UNT 206 IN UKCR 63.0
END DESCRIPTION:
XS GIS Cut Line= 3
      3705499.62     10487760.18      3706049.61     10487410.19
      3706199.61     10487010.19
#Sta/Elev= 30
  4379.2  348.95    4474  340.19  4532.4  330.95    4590   324.1  4689.9  316.39
  4756.8  313.46  4805.9  308.71  4936.3  305.68    4960  301.69  4987.1  294.11
    4997  293.88  4999.8  293.38    5003  293.88  5017.6  295.31  5023.5  298.62
  5033.8  298.41  5040.9  300.98  5046.2  305.06  5052.5  306.17  5095.2   306.8
  5156.6  310.59    5234  321.27  5255.4  327.65  5266.1  327.42  5272.3  330.98
  5297.2   334.2  5357.7  340.34  5363.1  338.53  5412.9  345.69  5458.3  348.84
#Mann= 3 ,-1 , 0
  4379.2     .15       0    4997     .05       0    5003     .15       0
Bank Sta=4960,5040.9
XS Rating Curve= 0 ,0
Exp/Cntr=0.3,0.1

Type RM Length L Ch R = 1 ,34096   ,497,497,497
BEGIN DESCRIPTION:
UNT 206 IN UKCR 62.0
END DESCRIPTION:
XS GIS Cut Line= 3
      3706299.61     10488260.16      3706349.61     10487460.19
      3706299.61     10487010.19
#Sta/Elev= 30
  4176.1  345.14  4258.7  339.21  4266.2   337.4  4296.3  335.19  4446.6  326.62
  4476.7  323.63  4486.7  323.93    4667  307.32  4857.4  303.82    4895  304.58
  4947.6  302.47  4967.6  303.55  4980.1  301.62  4987.7  295.34    4997  291.85
  4999.8  291.35    5003  291.85  5007.8  291.85  5017.9  295.82  5027.9  299.89
    5038  300.85  5048.1  307.19  5098.4   310.4  5168.8  317.56    5204  319.84
  5239.2  327.15  5279.5     333  5329.8  337.23  5380.1  344.83  5430.4  349.16
#Mann= 3 ,-1 , 0
  4176.1     .15       0    4997     .05       0    5003     .15       0
Bank Sta=4987.7,5017.9
XS Rating Curve= 0 ,0
Exp/Cntr=0.3,0.1

Type RM Length L Ch R = 1 ,33599   ,512,512,512
BEGIN DESCRIPTION:
UNT 206 IN UKCR 61.0
END DESCRIPTION:
XS GIS Cut Line= 3
      3706849.61     10488110.21      3706749.61     10487310.19
      3706449.58     10486910.15
#Sta/Elev= 30
  4169.4  334.81  4381.1  322.89  4529.7  309.26    4633  302.89  4713.6   299.4
  4784.2  298.62  4814.4   300.3  4874.9   300.3  4932.8  298.67  4937.9  295.69
  4945.4  293.44  4955.5  292.59  4973.1  289.66  4989.2  289.09    4997  287.16
  4999.8  286.66    5003  287.16  5012.1  287.57  5018.4  290.67 5021.53  293.39
  5025.7  298.15  5032.9  302.39  5039.2  303.27  5062.1  303.88  5097.5  308.53
  5153.8  313.63  5275.7  329.79  5353.8  337.73  5418.4  346.38  5475.7  352.35
#Mann= 3 ,-1 , 0
  4169.4     .15       0    4997     .05       0    5003     .15       0
Bank Sta=4955.5,5021.53
XS Rating Curve= 0 ,0
Exp/Cntr=0.3,0.1

Type RM Length L Ch R = 1 ,33087   ,487,487,487
BEGIN DESCRIPTION:
UNT 206 IN UKCR 60.0
END DESCRIPTION:
XS GIS Cut Line= 3
      3707099.61     10487910.18      3707199.61     10487410.19
       3706699.6     10486610.18
#Sta/Elev= 30
  4454.9  325.12  4760.8  307.36  4944.4  299.31  4967.7  296.68 4971.07  290.43
  4972.5  288.06  4993.7  286.54    4997  282.78  4999.8  282.28    5003  282.78
    5009   284.9  5014.9  284.31 5020.41  290.59  5023.8  294.82  5045.6  297.08
  5276.7  297.69  5342.1  300.15  5355.7  306.81  5392.3  307.82  5407.6  306.49
  5413.5  308.08  5486.6  310.58  5501.9  314.13  5507.8  312.43  5517.3  315.59
  5523.2  314.67  5538.5  319.86  5566.2  325.21  5602.2  329.69  5908.2  354.19
#Mann= 3 ,-1 , 0
  4454.9     .15       0    4997     .05       0    5003     .15       0
Bank Sta=4971.07,5020.41
XS Rating Curve= 0 ,0
Exp/Cntr=0.3,0.1

Type RM Length L Ch R = 1 ,32600   ,436,436,436
BEGIN DESCRIPTION:
UNT 206 IN UKCR 59.0
END DESCRIPTION:
XS GIS Cut Line= 3
      3707499.62     10487910.15      3707649.61     10487460.19
      3707599.61     10487010.16
#Sta/Elev= 30
  4535.8  318.45  4609.5  312.26    4715  299.61  4841.4  292.93  4915.2  291.47
  4946.9  292.19  4967.9  289.82  4978.5  286.62    4989   284.8    4997  279.73
  4999.8  279.23    5003  279.73  5007.5     282  5012.6     282 5018.41  286.96
  5020.2   292.2  5030.2  292.32  5040.3  291.68  5060.4   286.9  5110.7  288.96
  5130.8  286.09  5140.9   286.7    5151  290.94    5161  287.67  5171.1  291.31
  5181.1  293.06  5261.6  295.37  5291.8   299.3  5372.3  305.53  5462.9  309.06
#Mann= 3 ,-1 , 0
  4535.8     .15       0    4997     .05       0    5003     .15       0
Bank Sta=4978.5,5018.41
XS Rating Curve= 0 ,0
Exp/Cntr=0.3,0.1

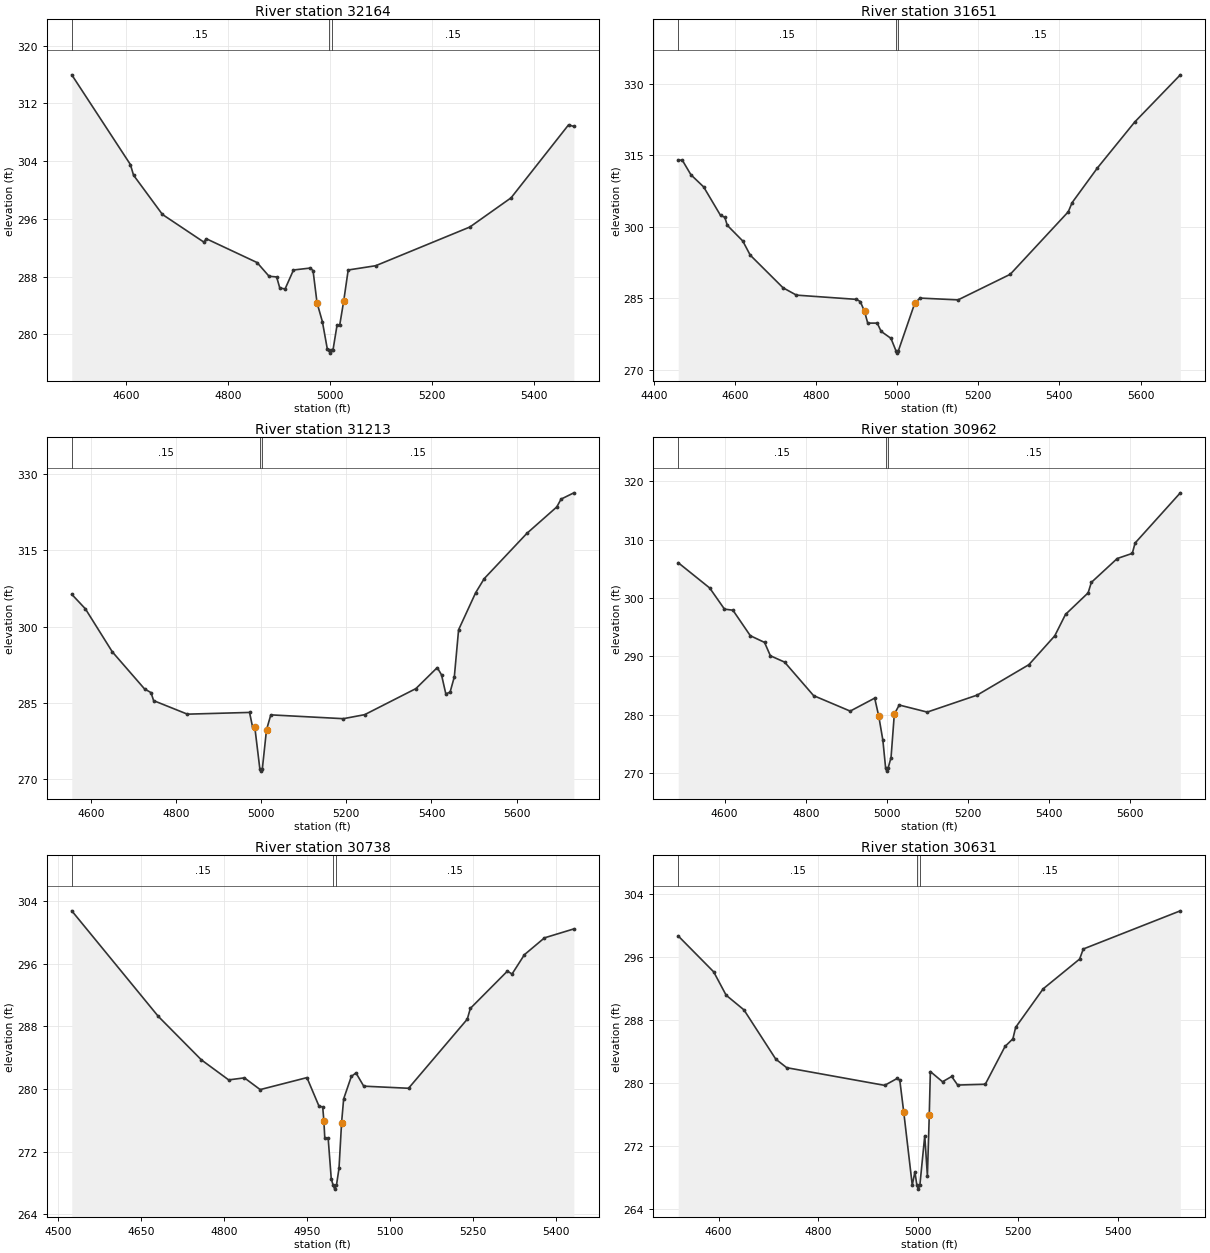
Type RM Length L Ch R = 1 ,32164   ,513,513,513
BEGIN DESCRIPTION:
UNT 206 IN UKCR 58.0
END DESCRIPTION:
XS GIS Cut Line= 3
      3707899.61     10488010.18      3708049.61     10487510.19
      3707949.61     10487060.18
#Sta/Elev= 30
  4494.2  315.95    4609  303.53  4615.1  302.06  4671.7  296.62  4752.6   292.8
  4757.8  293.25    4857  289.96  4880.5  288.06  4895.3  287.97  4901.4  286.45
  4911.8   286.3  4928.3  288.93  4961.4   289.2  4966.6  288.84  4974.4  284.39
  4984.9  281.77  4994.5     278    4997  277.92  4999.8  277.42    5003  277.92
  5005.8  277.92  5013.6   281.3  5018.8   281.3  5026.5  284.58  5035.4  288.93
  5089.2  289.52  5273.6  294.88  5354.3  298.92  5466.9  309.03  5477.2   308.8
#Mann= 3 ,-1 , 0
  4494.2     .15       0    4997     .05       0    5003     .15       0
Bank Sta=4974.4,5026.5
XS Rating Curve= 0 ,0
Exp/Cntr=0.3,0.1

Type RM Length L Ch R = 1 ,31651   ,438,438,438
BEGIN DESCRIPTION:
UNT 206 IN UKCR 57.0
END DESCRIPTION:
XS GIS Cut Line= 3
      3708349.62     10488060.14      3708499.61     10487560.19
      3708649.62     10486860.15
#Sta/Elev= 30
  4460.2  314.01  4470.6  313.89  4491.5  310.88  4522.8  308.34  4564.6  302.34
    4575  301.97  4581.1  300.28  4619.4  296.98  4637.6  294.03  4718.6  287.17
  4751.6  285.63  4899.5  284.74  4909.1  284.28  4919.5  282.21  4927.4  279.76
  4950.8  279.76  4960.4  278.03  4984.7  276.56    4997  273.96  4999.8  273.46
    5003  273.96  5043.5  283.96  5056.3  285.01  5150.1  284.63  5278.8     290
  5421.9  303.12  5431.3  305.03  5493.5  312.29  5585.6  321.94  5698.1  331.85
#Mann= 3 ,-1 , 0
  4460.2     .15       0    4997     .05       0    5003     .15       0
Bank Sta=4919.5,5043.5
XS Rating Curve= 0 ,0
Exp/Cntr=0.3,0.1

Type RM Length L Ch R = 1 ,31213   ,251,251,251
BEGIN DESCRIPTION:
UNT 206 IN UKCR 56.0
END DESCRIPTION:
XS GIS Cut Line= 3
      3708749.62     10488110.15      3708899.61     10487710.19
      3708849.61     10486960.22
#Sta/Elev= 30
  4555.5  306.34  4587.5  303.48  4650.7  295.02  4726.3  287.73  4741.5     287
  4747.7  285.42  4826.9  282.76  4972.9   283.1    4980  280.23  4985.2  280.23
    4997  272.05  4999.8  271.55    5003  272.05  5012.7  279.67  5022.8  282.62
  5193.1  281.87  5243.2  282.66  5363.5  287.79  5413.6  291.92  5423.6   290.5
  5433.7  286.76  5443.7  287.08  5453.7  290.11  5463.7  299.36  5503.8  306.66
  5523.9  309.43  5624.1  318.34  5694.2  323.53  5704.3  325.07  5734.3  326.31
#Mann= 3 ,-1 , 0
  4555.5     .15       0    4997     .05       0    5003     .15       0
Bank Sta=4985.2,5012.7
XS Rating Curve= 0 ,0
Exp/Cntr=0.3,0.1

Type RM Length L Ch R = 1 ,30962   ,224,224,224
BEGIN DESCRIPTION:
Mapping XS 3f43fc46
END DESCRIPTION:
XS GIS Cut Line= 4
        3708868.     10488158.61      3709128.43     10487850.43
       3709167.5     10487533.59      3709007.25     10487044.18
#Sta/Elev= 30
  4485.7  306.03  4563.3   301.7  4599.7  298.08  4620.5   297.9  4663.4  293.53
  4698.5  292.38  4712.8   290.1  4747.9  289.01  4819.4  283.27  4909.6  280.62
    4970  282.84  4980.1  279.72  4990.2  275.61    4997  270.84  4999.8  270.34
    5003  270.84  5010.3  272.67  5018.4  280.11  5030.5  281.66  5099.5  280.45
  5222.7  283.36  5350.1  288.57  5413.9  293.51  5440.4  297.18  5496.1  300.87
  5504.1  302.66  5567.9  306.75    5605  307.63  5611.9   309.4  5723.4     318
#Mann= 3 ,-1 , 0
  4485.7     .15       0    4997     .05       0    5003     .15       0
Bank Sta=4980.1,5018.4
XS Rating Curve= 0 ,0
Exp/Cntr=0.3,0.1

Type RM Length L Ch R = 1 ,30738   ,107,107,107
BEGIN DESCRIPTION:
UNT 206 IN UKCR 55.0
END DESCRIPTION:
XS GIS Cut Line= 3
      3708999.57     10488110.22      3709349.61     10487810.19
      3709549.59     10487410.22
#Sta/Elev= 30
  4524.2  302.76  4680.6  289.29  4758.6  283.73    4808  281.17  4836.5  281.43
    4865  279.93  4949.6  281.46  4971.5   277.8  4978.1  277.72 4980.23  275.96
  4981.9  273.71    4988  273.71  4993.6  268.52    4997  267.72  4999.8  267.22
    5003  267.72  5007.6  269.87 5012.27  275.71    5016  278.74  5029.9  281.61
  5038.3  282.06  5052.3  280.37  5133.4   280.1  5239.6  288.92  5245.2   290.3
  5312.2  295.06  5320.6  294.69    5343  297.16  5379.3  299.31  5432.4  300.45
#Mann= 3 ,-1 , 0
  4524.2     .15       0    4997     .05       0    5003     .15       0
Bank Sta=4980.23,5012.27
XS Rating Curve= 0 ,0
Exp/Cntr=0.3,0.1

Type RM Length L Ch R = 1 ,30631   ,354,354,354
BEGIN DESCRIPTION:
Mapping XS a98aea4b
END DESCRIPTION:
XS GIS Cut Line= 2
      3709280.34     10488293.14       3709631.9     10487351.31
#Sta/Elev= 30
  4519.2   298.7  4590.2  294.13  4615.1  291.16  4650.8  289.29  4714.5  283.02
  4736.4  281.93  4932.5  279.68  4957.5  280.56  4962.8  280.35  4970.7  276.29
  4987.8  266.97  4993.1  268.69    4997  266.97  4999.8  266.47    5003  266.97
  5012.8  273.27  5018.1  268.16 5021.82  275.86    5024  281.44  5048.4  280.14
  5066.7  280.81  5078.7  279.72    5134  279.82  5173.5  284.63  5189.3  285.61
  5194.8  287.07  5249.9  291.97  5322.9  295.76  5330.2  297.04  5524.5   301.9
#Mann= 3 ,-1 , 0
  4519.2     .15       0    4997     .05       0    5003     .15       0
Bank Sta=4970.7,5021.82
XS Rating Curve= 0 ,0
Exp/Cntr=0.3,0.1

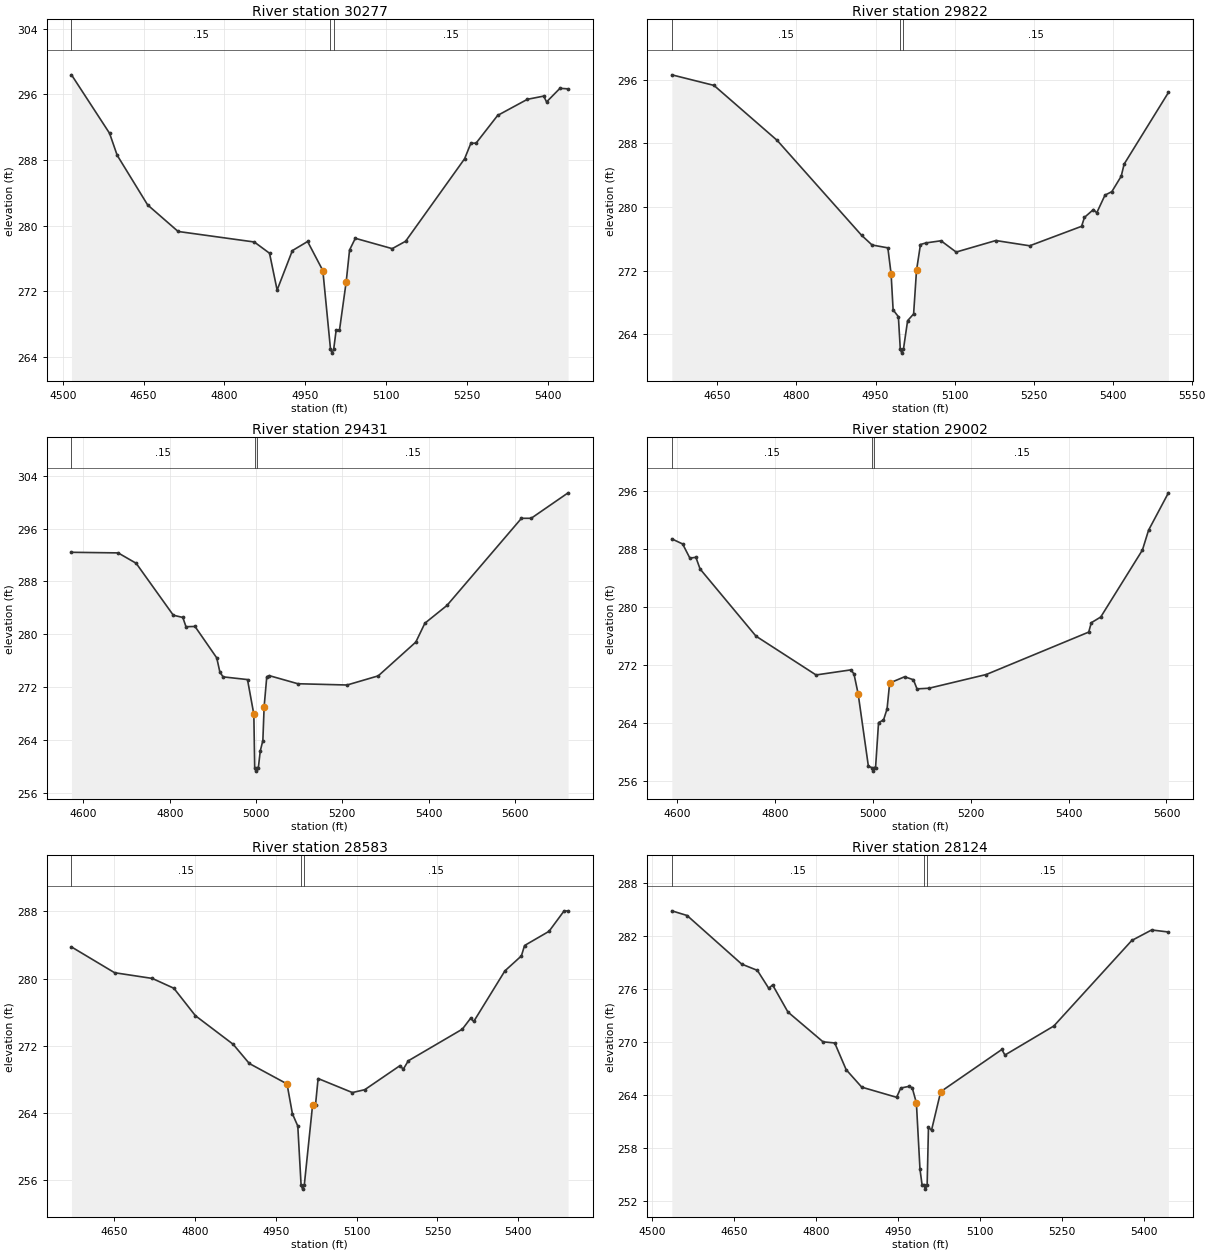
Type RM Length L Ch R = 1 ,30277   ,455,455,455
BEGIN DESCRIPTION:
UNT 206 IN UKCR 54.0
END DESCRIPTION:
XS GIS Cut Line= 3
      3709449.63     10488260.17      3709799.61     10487910.19
      3709649.63     10487510.23
#Sta/Elev= 30
  4516.1  298.37  4586.8  291.25  4600.9  288.58  4657.5  282.53  4714.1   279.3
  4855.5  278.02  4883.8  276.65  4897.9  272.17  4926.2  276.97  4954.5  278.08
  4982.8  274.54    4997  264.99  4999.8  264.49    5003  264.99  5007.5  267.28
  5013.7  267.28  5026.2  273.19  5032.4  277.04  5043.1  278.47  5111.6  277.21
  5136.5  278.11    5246  288.15  5257.6  290.03  5267.4  290.06  5307.4  293.43
  5362.6  295.39  5392.9  295.78  5398.2  295.07  5423.1  296.73  5438.2  296.66
#Mann= 3 ,-1 , 0
  4516.1     .15       0    4997     .05       0    5003     .15       0
Bank Sta=4982.8,5026.2
XS Rating Curve= 0 ,0
Exp/Cntr=0.3,0.1

Type RM Length L Ch R = 1 ,29822   ,391,391,391
BEGIN DESCRIPTION:
UNT 206 IN UKCR 53.0
END DESCRIPTION:
XS GIS Cut Line= 3
      3710199.61     10488210.23      3710199.61     10487760.19
       3709749.6     10487560.18
#Sta/Elev= 30
  4563.4  296.63  4643.4   295.3  4763.4  288.38  4923.4  276.46  4943.4  275.23
  4973.4  274.87 4979.55  271.61  4983.4  267.07  4993.4  266.21    4997  262.13
  4999.8  261.63    5003  262.13  5010.9  265.71  5022.3  266.56  5027.8  272.04
  5035.3  275.29  5045.6  275.49  5074.3  275.76    5103  274.34  5178.3  275.79
  5242.6  275.13  5341.1  277.58  5346.5   278.7  5363.6  279.69  5369.8  279.27
  5385.5   281.5  5398.5  281.94  5416.3  283.88  5421.8   285.4  5505.9  294.41
#Mann= 3 ,-1 , 0
  4563.4     .15       0    4997     .05       0    5003     .15       0
Bank Sta=4979.55,5027.8
XS Rating Curve= 0 ,0
Exp/Cntr=0.3,0.1

Type RM Length L Ch R = 1 ,29431   ,429,429,429
BEGIN DESCRIPTION:
UNT 206 IN UKCR 52.0
END DESCRIPTION:
XS GIS Cut Line= 3
      3710799.61     10487960.19      3710549.61     10487610.19
      3710149.63     10487010.21
#Sta/Elev= 30
  4572.3  292.41  4680.4  292.32  4722.2  290.75  4808.3   282.9  4830.4  282.56
  4837.7  281.16  4858.6   281.2    4909  276.45  4916.4  274.27  4923.8  273.58
  4980.3  273.17    4995  267.92    4997  259.83  4999.8  259.33    5003  259.83
  5005.4  259.83  5009.9  262.38  5015.9  263.95 5018.86  269.07    5025  273.61
    5031  273.76  5097.1  272.54  5211.2  272.35  5283.4  273.73  5370.5  278.84
  5391.5  281.69  5442.6  284.37  5615.4  297.55  5637.9  297.55  5723.5   301.4
#Mann= 3 ,-1 , 0
  4572.3     .15       0    4997     .05       0    5003     .15       0
Bank Sta=4995,5018.86
XS Rating Curve= 0 ,0
Exp/Cntr=0.3,0.1

Type RM Length L Ch R = 1 ,29002   ,419,419,419
BEGIN DESCRIPTION:
UNT 206 IN UKCR 51.0
END DESCRIPTION:
XS GIS Cut Line= 3
      3711049.61     10487660.19      3710799.61     10487310.19
      3710599.59     10486760.15
#Sta/Elev= 30
  4588.6   289.4  4610.7   288.7  4625.5  286.75  4637.8  286.86  4646.4  285.25
  4760.7  275.99  4883.5  270.64  4954.8  271.34    4961  270.79  4969.6  268.03
  4990.5  258.06    4997  257.88  4999.8  257.38    5003  257.88  5005.2  257.88
  5011.3  264.08  5021.4  264.42  5028.7  265.95    5034  269.53  5064.6  270.39
  5082.6  269.98  5089.9  268.72  5114.5  268.81  5231.5   270.7    5441  276.55
  5446.3  277.84  5465.6  278.63  5550.8  287.86  5563.4   290.6    5604  295.75
#Mann= 3 ,-1 , 0
  4588.6     .15       0    4997     .05       0    5003     .15       0
Bank Sta=4969.6,5034
XS Rating Curve= 0 ,0
Exp/Cntr=0.3,0.1

Type RM Length L Ch R = 1 ,28583   ,459,459,459
BEGIN DESCRIPTION:
UNT 206 IN UKCR 50.0
END DESCRIPTION:
XS GIS Cut Line= 3
      3711099.61     10487510.19      3711099.61     10487060.19
      3710849.61     10486660.19
#Sta/Elev= 30
  4570.9  283.78  4650.9  280.71  4720.9  280.03  4760.9  278.86  4800.9  275.59
  4870.9  272.19  4900.9   269.9  4970.9  267.47  4980.9  263.92  4990.9  262.45
    4997  255.44  4999.8  254.94    5003  255.44  5018.4  264.98  5023.8  264.98
  5028.6  268.11  5092.2  266.44  5115.2  266.78  5180.7  269.65  5186.6  269.21
    5196  270.22  5296.3  273.99  5311.6  275.28  5317.5  274.91  5375.3  280.93
  5405.9  282.71  5411.8  283.95  5457.2  285.64  5484.9  288.05  5492.6  288.08
#Mann= 3 ,-1 , 0
  4570.9     .15       0    4997     .05       0    5003     .15       0
Bank Sta=4970.9,5018.4
XS Rating Curve= 0 ,0
Exp/Cntr=0.3,0.1

Type RM Length L Ch R = 1 ,28124   ,432,432,432
BEGIN DESCRIPTION:
UNT 206 IN UKCR 49.0
END DESCRIPTION:
XS GIS Cut Line= 3
      3711199.64     10487560.15      3711499.61     10487210.19
      3711699.59     10486810.23
#Sta/Elev= 30
  4536.1  284.87    4564  284.34  4663.9  278.83  4692.5  278.12  4713.3  276.09
  4720.4  276.47  4748.4   273.4  4812.6  270.02    4834  269.89  4854.9  266.86
  4883.4  264.88  4947.1  263.73  4954.8  264.78    4969  264.96  4975.6  264.83
  4983.3   263.1  4989.9  255.56  4993.7  253.82    4997  253.82  4999.8  253.32
    5003  253.82  5005.4  260.33    5011     260  5027.8  264.37  5139.6  269.15
  5145.2  268.52  5234.6  271.81  5377.2  281.51  5413.5   282.7  5444.2  282.47
#Mann= 3 ,-1 , 0
  4536.1     .15       0    4997     .05       0    5003     .15       0
Bank Sta=4983.3,5027.8
XS Rating Curve= 0 ,0
Exp/Cntr=0.3,0.1

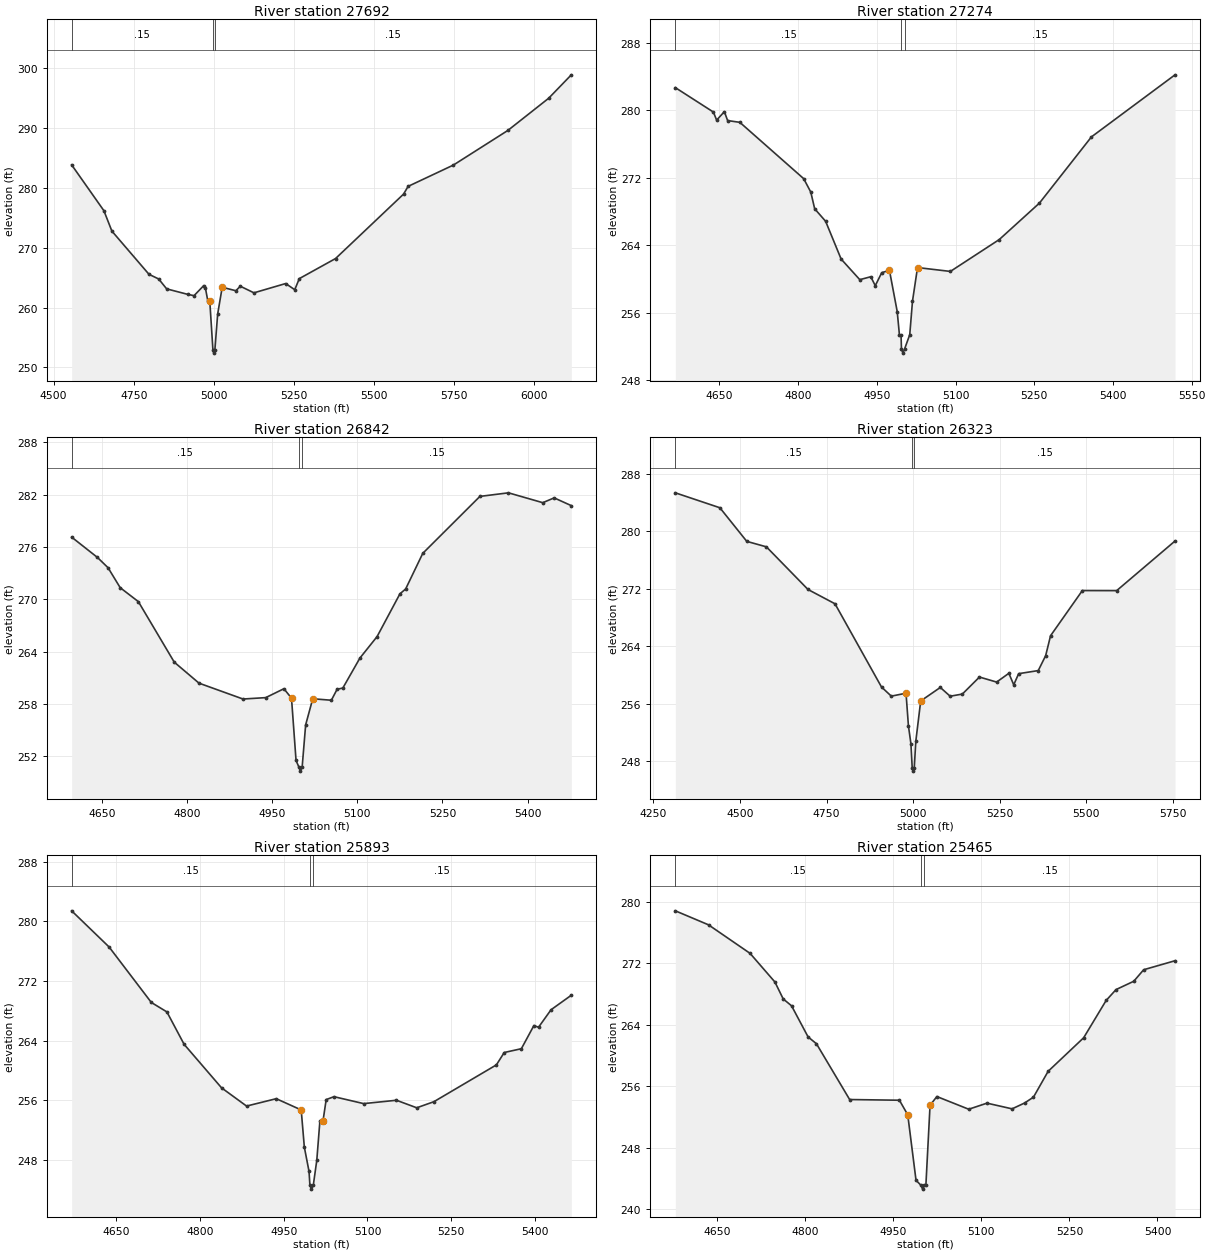
Type RM Length L Ch R = 1 ,27692   ,418,418,418
BEGIN DESCRIPTION:
UNT 206 IN UKCR 48.0
END DESCRIPTION:
XS GIS Cut Line= 3
       3711599.6     10487960.21      3711749.61     10487560.19
      3712549.62     10486760.18
#Sta/Elev= 30
  4556.3   283.8  4656.9  276.15  4681.8  272.75  4797.5  265.54  4827.8  264.76
  4852.7  263.11  4919.4  262.18  4938.1  261.98  4968.4  263.66  4973.7  263.21
  4980.9  261.14  4987.1  261.14    4997  252.89  4999.8  252.39    5003  252.89
  5011.8  258.92  5025.9  263.38  5068.4   262.8  5082.5  263.55  5124.9  262.45
  5223.9     264  5252.2  262.97  5266.4  264.82  5379.5  268.17  5591.6  278.92
  5605.8  280.21  5747.2  283.77  5916.9  289.54  6044.2  294.91  6114.9  298.82
#Mann= 3 ,-1 , 0
  4556.3     .15       0    4997     .05       0    5003     .15       0
Bank Sta=4987.1,5025.9
XS Rating Curve= 0 ,0
Exp/Cntr=0.3,0.1

Type RM Length L Ch R = 1 ,27274   ,432,432,432
BEGIN DESCRIPTION:
UNT 206 IN UKCR 47.0
END DESCRIPTION:
XS GIS Cut Line= 3
      3711899.59     10488010.21      3712149.61     10487660.19
      3712299.62     10487160.15
#Sta/Elev= 30
  4566.1   282.7  4638.6   279.8  4644.8  278.84  4659.5  279.85  4665.7  278.79
    4689  278.58  4810.7  271.89  4824.2   270.3  4831.6  268.32  4852.5  266.83
    4882  262.35  4917.6   259.9  4938.5  260.25  4947.1  259.19  4959.4  260.73
  4974.1  261.01  4988.9  256.12  4993.2   253.3  4996.2   253.3    4997  251.68
  4999.8  251.18    5003  251.68  5012.8  253.37    5018  257.34  5027.6  261.34
  5090.2  260.88  5183.3  264.66  5259.9  268.99    5359  276.85  5518.3  284.22
#Mann= 3 ,-1 , 0
  4566.1     .15       0    4997     .05       0    5003     .15       0
Bank Sta=4974.1,5027.6
XS Rating Curve= 0 ,0
Exp/Cntr=0.3,0.1

Type RM Length L Ch R = 1 ,26842   ,519,519,519
BEGIN DESCRIPTION:
UNT 206 IN UKCR 46.0
END DESCRIPTION:
XS GIS Cut Line= 3
      3712399.59     10488210.23      3712549.61     10487810.19
      3712599.61      10487360.2
#Sta/Elev= 30
    4597  277.14  4642.4  274.81  4661.1  273.63  4682.5  271.34  4714.5  269.74
  4777.7   262.8  4821.3  260.39  4898.8  258.57  4938.8  258.73  4970.8  259.75
  4984.2  258.67  4992.2  251.52    4997   250.8  4999.8   250.3    5003   250.8
  5009.1   255.6  5021.6   258.6  5054.4  258.43  5064.5  259.69  5074.6  259.83
  5104.7  263.27  5134.9  265.73  5175.2  270.64  5185.2  271.19  5215.4  275.28
    5316  281.81  5366.3  282.22  5426.7  281.09  5446.8  281.64    5477  280.75
#Mann= 3 ,-1 , 0
    4597     .15       0    4997     .05       0    5003     .15       0
Bank Sta=4984.2,5021.6
XS Rating Curve= 0 ,0
Exp/Cntr=0.3,0.1

Type RM Length L Ch R = 1 ,26323   ,430,430,430
BEGIN DESCRIPTION:
UNT 206 IN UKCR 45.0
END DESCRIPTION:
XS GIS Cut Line= 2
      3712396.73     10488578.96      3713438.42     10487580.68
#Sta/Elev= 30
  4313.1  285.37  4441.7  283.29  4519.4  278.61    4576  277.85  4696.2  271.91
  4774.1  269.92  4908.4  258.33  4936.7  257.06  4979.2  257.47  4986.1  252.93
  4993.3  250.45    4997  247.12  4999.8  246.62    5003  247.12  5007.5  250.81
  5021.6  256.39  5078.2  258.27  5106.6  257.05  5141.8  257.35  5191.2  259.72
  5240.8  259.02  5276.1  260.24  5290.2  258.64  5304.4  260.19    5361  260.62
  5382.4   262.7  5396.5  265.47  5488.3  271.76  5587.4  271.75  5755.9  278.66
#Mann= 3 ,-1 , 0
  4313.1     .15       0    4997     .05       0    5003     .15       0
Bank Sta=4979.2,5021.6
XS Rating Curve= 0 ,0
Exp/Cntr=0.3,0.1

Type RM Length L Ch R = 1 ,25893   ,428,428,428
BEGIN DESCRIPTION:
UNT 206 IN UKCR 44.0
END DESCRIPTION:
XS GIS Cut Line= 3
      3712699.59      10488610.2      3713099.61     10488410.19
      3713499.57     10488210.21
#Sta/Elev= 30
  4570.5  281.41  4637.6  276.55  4713.1  269.11    4741  267.84  4771.8  263.49
  4838.8  257.65  4883.6   255.2  4936.7  256.19  4981.4  254.68    4987  249.69
  4995.4  246.43    4997  244.55  4999.8  244.05    5003  244.55  5009.3  247.92
  5014.9  253.24  5020.5  253.24  5026.1  256.07  5040.1  256.46  5093.2  255.53
  5151.9  255.98  5188.2  254.97    5219  255.79  5330.8  260.73  5344.8  262.39
  5375.5   262.9  5397.9  266.01  5406.2  265.78  5428.6  268.13  5464.9  270.08
#Mann= 3 ,-1 , 0
  4570.5     .15       0    4997     .05       0    5003     .15       0
Bank Sta=4981.4,5020.5
XS Rating Curve= 0 ,0
Exp/Cntr=0.3,0.1

Type RM Length L Ch R = 1 ,25465   ,1099,1099,1099
BEGIN DESCRIPTION:
UNT 206 IN UKCR 43.0
END DESCRIPTION:
XS GIS Cut Line= 3
      3713099.63     10488910.17      3713399.61     10488610.19
       3713549.6     10488210.22
#Sta/Elev= 30
  4578.5  278.81    4635  276.99  4705.8  273.28  4748.2  269.55  4762.3  267.35
  4776.5  266.46  4804.7  262.41  4818.9  261.53  4875.5  254.27  4960.3  254.18
  4974.5  252.28  4988.6  243.77    4997  243.12  4999.8  242.62    5003  243.12
  5005.4  243.12  5012.5  253.52  5024.1  254.66  5078.4  253.01  5109.5   253.8
  5152.3  253.06  5173.6  253.82  5188.7  254.58  5213.7  257.94  5274.2   262.3
  5312.5  267.15  5329.4  268.57  5359.6  269.65  5376.5  271.15  5429.9  272.32
#Mann= 3 ,-1 , 0
  4578.5     .15       0    4997     .05       0    5003     .15       0
Bank Sta=4974.5,5012.5
XS Rating Curve= 0 ,0
Exp/Cntr=0.3,0.1