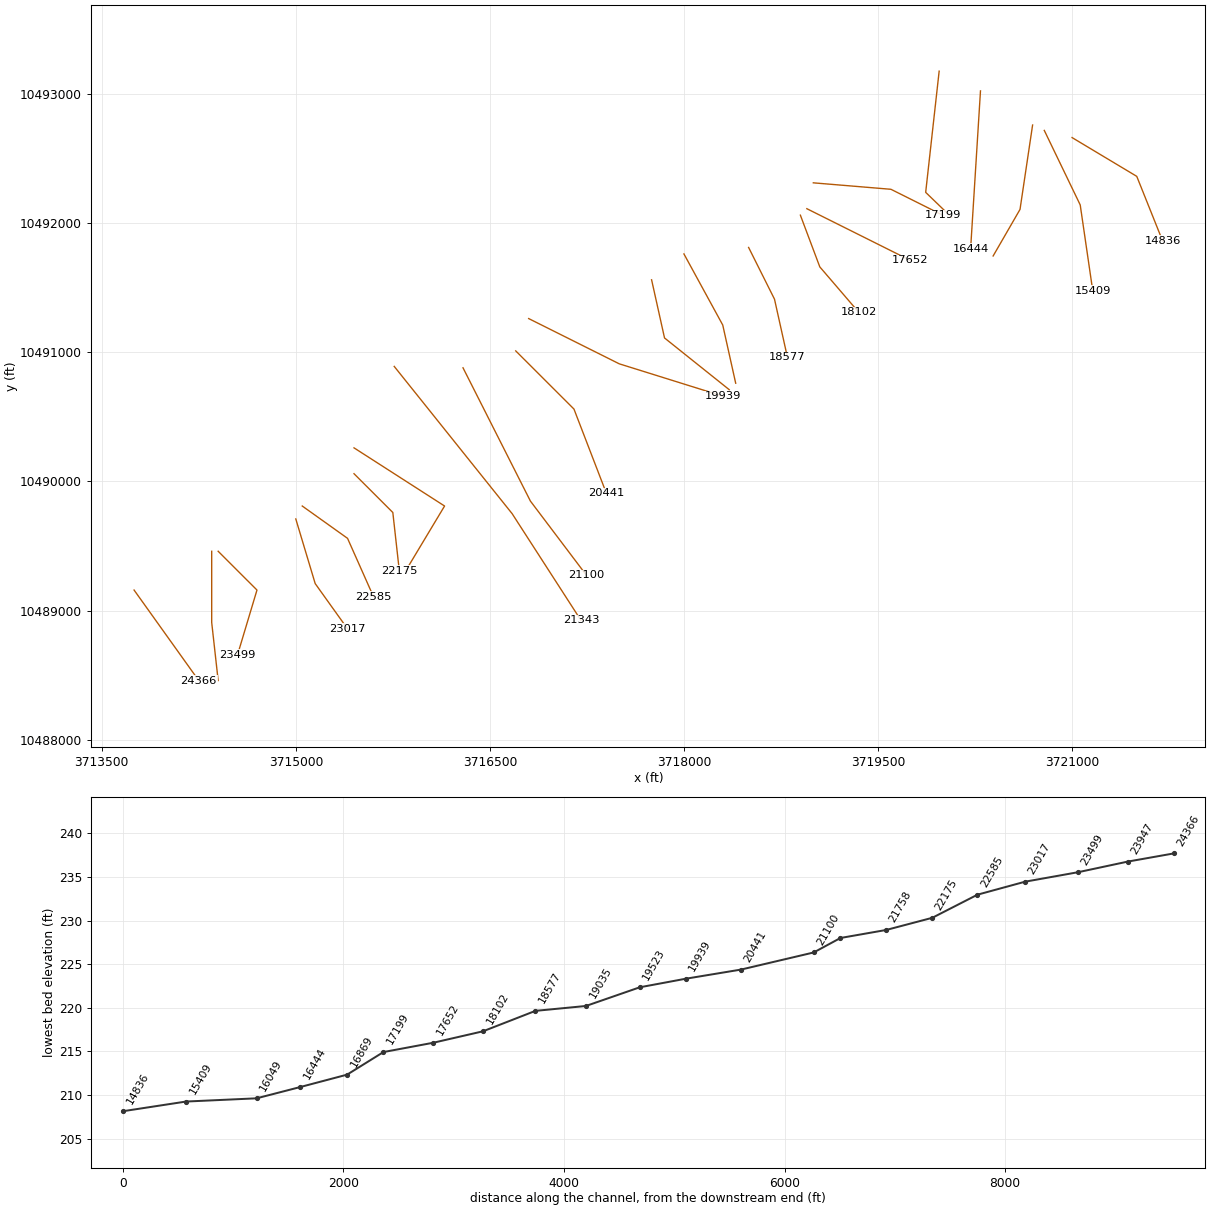
HEC-RAS study UNT 206 IN UKCR.prj: UNT 206 IN UKCR Base Level Engineering

--- UNT 206 IN UKCR.g01 (geometry) --- (continued)

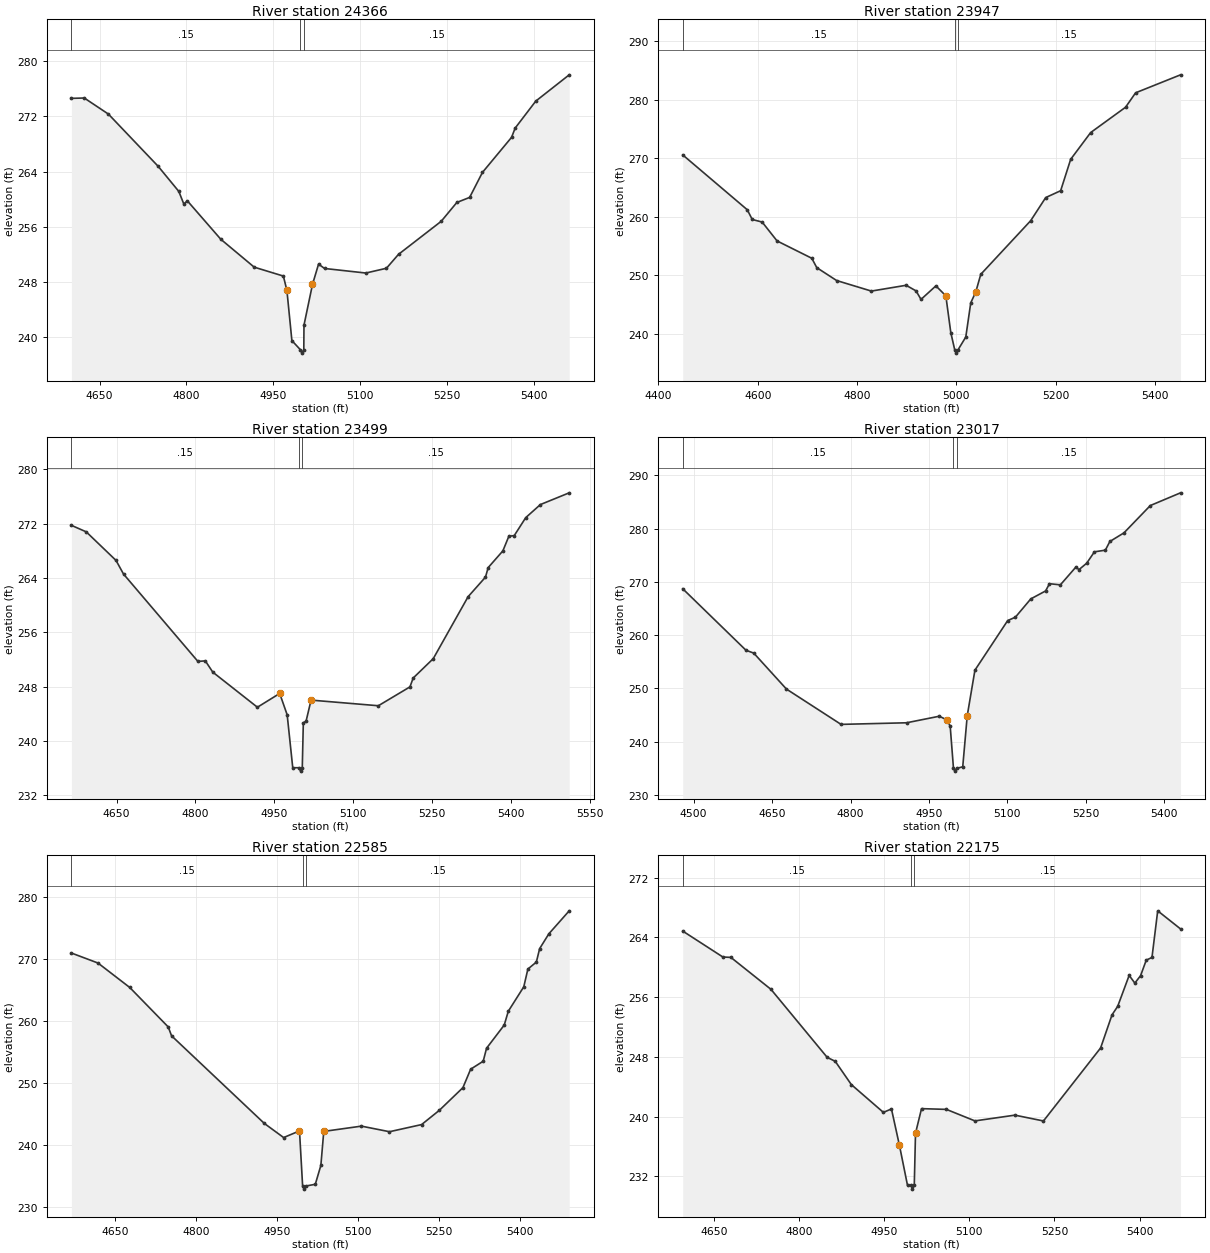
Type RM Length L Ch R = 1 ,24366   ,419,419,419
BEGIN DESCRIPTION:
UNT 206 IN UKCR 41.0
END DESCRIPTION:
XS GIS Cut Line= 3
      3713749.59     10489160.22      3713999.61     10488810.19
      3714249.63     10488460.17
#Sta/Elev= 30
  4601.4  274.62  4623.6  274.67  4665.3  272.34  4751.4  264.76    4787  261.13
  4795.6  259.31  4801.8  259.76  4859.5   254.2  4917.3  250.15  4967.7  248.86
  4973.8  246.78  4982.4  239.51    4997  238.19  4999.8  237.69    5003  238.19
  5003.3  241.74    5018  247.64  5028.5  250.59  5038.9  249.96  5110.2   249.3
  5145.8  249.99  5166.7  252.01  5240.5   256.8  5267.5  259.53  5289.6  260.26
  5311.7  263.88  5362.1  268.97  5368.3  270.31  5403.9  274.22  5461.7  278.03
#Mann= 3 ,-1 , 0
  4601.4     .15       0    4997     .05       0    5003     .15       0
Bank Sta=4973.8,5018
XS Rating Curve= 0 ,0
Exp/Cntr=0.3,0.1

Type RM Length L Ch R = 1 ,23947   ,448,448,448
BEGIN DESCRIPTION:
UNT 206 IN UKCR 40.0
END DESCRIPTION:
XS GIS Cut Line= 3
      3714349.61     10489460.23      3714349.61     10488910.19
      3714399.61      10488460.2
#Sta/Elev= 30
  4448.9  270.58  4578.9  261.22  4588.9  259.56  4608.9  259.12  4638.9   255.9
  4708.9  252.94  4718.9  251.34  4758.9  249.14  4828.9  247.34  4898.9  248.33
  4918.9  247.37  4928.9  245.92  4958.9  248.23  4978.9  246.53  4988.9  240.26
    4997  237.25  4999.8  236.75    5003  237.25  5019.1   239.5  5029.1  245.33
  5039.2  247.19  5049.3   250.2  5149.9  259.36  5180.1   263.3  5210.2  264.47
  5230.4  269.83  5270.6  274.39    5341  278.72  5361.2  281.18  5451.7  284.25
#Mann= 3 ,-1 , 0
  4448.9     .15       0    4997     .05       0    5003     .15       0
Bank Sta=4978.9,5039.2
XS Rating Curve= 0 ,0
Exp/Cntr=0.3,0.1

Type RM Length L Ch R = 1 ,23499   ,482,482,482
BEGIN DESCRIPTION:
UNT 206 IN UKCR 39.0
END DESCRIPTION:
XS GIS Cut Line= 3
      3714399.64     10489460.16      3714699.61     10489160.19
      3714549.62     10488660.22
#Sta/Elev= 30
  4564.2  271.74  4592.4  270.78    4649  266.57  4663.2  264.57  4804.6   251.7
  4818.7  251.78  4832.9  250.12  4917.7  244.95  4960.1  246.98  4974.3  243.83
  4984.9  236.04    4997  236.04  4999.8  235.54    5003  236.04    5005  242.66
  5010.2  242.89  5019.7     246  5147.6  245.17  5207.7  247.95  5213.8  249.25
    5252  252.11  5318.2  261.23  5351.2  264.11  5356.4  265.52  5384.3  267.98
  5395.6  270.12    5406  270.24  5427.8  272.88  5455.6   274.8  5510.4  276.53
#Mann= 3 ,-1 , 0
  4564.2     .15       0    4997     .05       0    5003     .15       0
Bank Sta=4960.1,5019.7
XS Rating Curve= 0 ,0
Exp/Cntr=0.3,0.1

Type RM Length L Ch R = 1 ,23017   ,432,432,432
BEGIN DESCRIPTION:
UNT 206 IN UKCR 38.0
END DESCRIPTION:
XS GIS Cut Line= 3
       3714999.6     10489710.22      3715149.61     10489210.19
      3715399.63     10488860.16
#Sta/Elev= 30
  4479.1   268.7  4600.1  257.15  4614.9  256.62  4677.5  249.86  4781.9  243.23
  4907.2  243.53  4969.8  244.76  4984.6  244.07  4990.7  242.89    4997  234.95
  4999.8  234.45    5003  234.95  5014.7  235.27  5023.3  244.85    5038  253.41
  5100.7  262.73  5115.4  263.36  5144.9   266.8  5173.2  268.29  5180.6  269.65
  5201.5  269.44    5231  272.76  5237.1   272.3  5251.8   273.5  5266.6  275.64
  5287.5  275.95  5296.1  277.58  5323.1   279.2  5373.5  284.33  5431.3  286.72
#Mann= 3 ,-1 , 0
  4479.1     .15       0    4997     .05       0    5003     .15       0
Bank Sta=4984.6,5023.3
XS Rating Curve= 0 ,0
Exp/Cntr=0.3,0.1

Type RM Length L Ch R = 1 ,22585   ,410,410,410
BEGIN DESCRIPTION:
UNT 206 IN UKCR 37.0
END DESCRIPTION:
XS GIS Cut Line= 3
      3715049.61     10489810.19      3715399.61     10489560.19
      3715599.63     10489110.15
#Sta/Elev= 30
  4568.5     271  4617.7  269.39  4676.6  265.45  4747.9  259.09  4754.1  257.66
  4926.1  243.54  4961.8  241.27  4991.2  242.34    4997  233.46  4999.8  232.96
    5003  233.46  5020.5  233.74  5030.8  236.78  5036.2  242.26    5106  243.11
    5158  242.21  5217.5  243.36  5250.3  245.65  5294.1  249.31  5308.4  252.28
  5331.7  253.57  5337.9  255.66  5370.7   259.4  5378.2  261.62  5406.9  265.56
  5414.5  268.42  5430.2  269.54  5436.3  271.71  5453.4   274.1  5491.1   277.8
#Mann= 3 ,-1 , 0
  4568.5     .15       0    4997     .05       0    5003     .15       0
Bank Sta=4991.2,5036.2
XS Rating Curve= 0 ,0
Exp/Cntr=0.3,0.1

Type RM Length L Ch R = 1 ,22175   ,417,417,417
BEGIN DESCRIPTION:
UNT 206 IN UKCR 36.0
END DESCRIPTION:
XS GIS Cut Line= 3
      3715449.62     10490060.17      3715749.61     10489760.19
      3715799.61      10489310.2
#Sta/Elev= 30
  4595.1  264.84  4665.8  261.37  4679.9  261.32  4750.6  257.04  4849.6  247.94
  4863.8  247.41  4892.1   244.3  4948.6  240.58  4962.8  241.04  4976.9  236.16
  4991.1  230.81    4997  230.81  4999.8  230.31    5003  230.81  5005.2  237.79
  5015.8  241.08  5059.6  240.98  5109.9  239.44  5180.3  240.21  5230.6  239.43
  5331.3   249.2  5351.4  253.63  5361.4  254.77  5381.6  258.91  5391.6  257.88
  5401.7  258.87  5411.7  260.95  5421.8  261.31  5431.9  267.55  5472.1  265.13
#Mann= 3 ,-1 , 0
  4595.1     .15       0    4997     .05       0    5003     .15       0
Bank Sta=4976.9,5005.2
XS Rating Curve= 0 ,0
Exp/Cntr=0.3,0.1

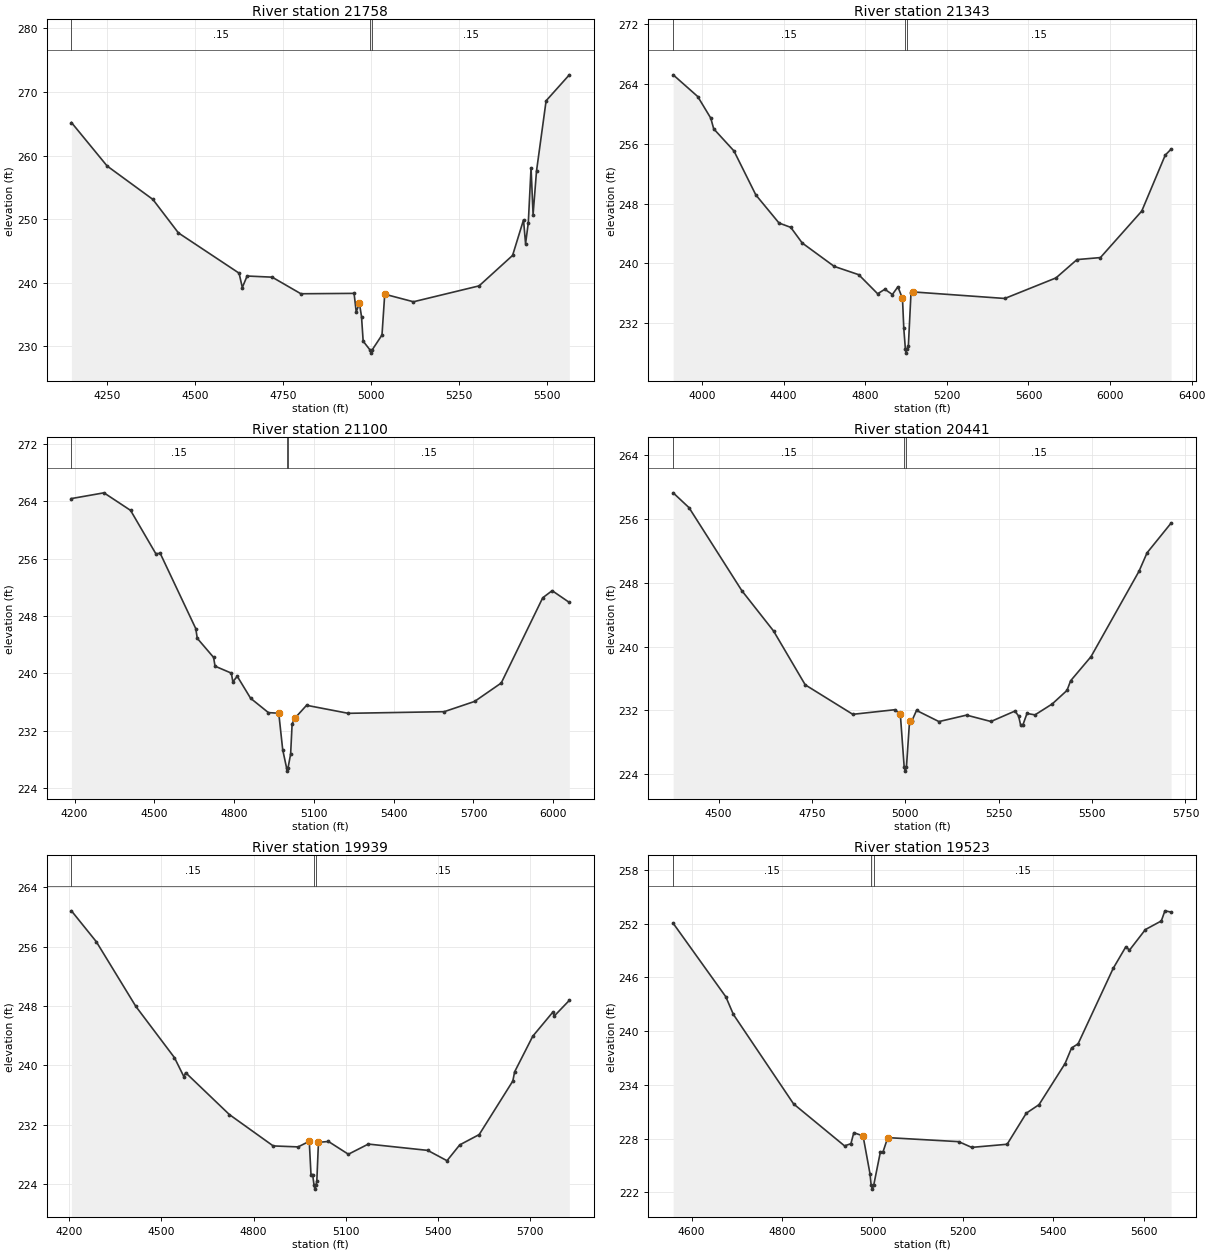
Type RM Length L Ch R = 1 ,21758   ,415,415,415
BEGIN DESCRIPTION:
UNT 206 IN UKCR 35.0
END DESCRIPTION:
XS GIS Cut Line= 3
      3715449.63     10490260.17      3716149.61     10489810.19
      3715849.63     10489310.22
#Sta/Elev= 30
  4148.3   265.2  4249.7  258.36  4379.8   253.1  4452.4  247.83  4624.8   241.5
    4634  239.24  4647.6  241.05  4718.9  240.87  4800.5  238.26  4951.7  238.32
  4957.7  235.42  4966.9  236.75  4972.8  234.68  4977.5   230.8    4997  229.42
  4999.8  228.92    5003  229.42    5031  231.77  5038.8  238.19  5120.4     237
    5307   239.5  5402.2  244.29  5433.3  249.88  5439.1  246.12  5446.9  249.44
  5454.7  258.07  5460.5  250.72  5470.2  257.56  5497.5  268.62  5563.5   272.7
#Mann= 3 ,-1 , 0
  4148.3     .15       0    4997     .05       0    5003     .15       0
Bank Sta=4966.9,5038.8
XS Rating Curve= 0 ,0
Exp/Cntr=0.3,0.1

Type RM Length L Ch R = 1 ,21343   ,243,243,243
BEGIN DESCRIPTION:
UNT 206 IN UKCR 34.0
END DESCRIPTION:
XS GIS Cut Line= 3
      3715760.43     10490890.18       3716671.9     10489750.85
      3717203.61     10488926.15
#Sta/Elev= 30
  3858.8  265.22    3979  262.32    4043  259.43  4057.4     258  4156.7  255.04
  4263.9  249.16  4377.6   245.4  4435.1  244.82  4491.2  242.73  4648.1   239.6
  4768.2  238.49    4861  235.94  4896.2  236.54  4933.1  235.84  4960.3  236.87
  4982.7  235.31  4989.1   231.3    4997   228.5  4999.8     228    5003   228.5
  5011.4  228.92  5024.3  235.99  5032.3  236.19  5484.1  235.31  5735.1  238.06
  5837.9  240.51  5952.8  240.78  6155.4     247  6270.5  254.48  6299.1  255.28
#Mann= 3 ,-1 , 0
  3858.8     .15       0    4997     .05       0    5003     .15       0
Bank Sta=4982.7,5032.3
XS Rating Curve= 0 ,0
Exp/Cntr=0.3,0.1

Type RM Length L Ch R = 1 ,21100   ,659,659,659
BEGIN DESCRIPTION:
UNT 206 IN UKCR 33.0
END DESCRIPTION:
XS GIS Cut Line= 3
      3716292.11     10490879.34      3716812.96      10489848.5
      3717245.16     10489275.84
#Sta/Elev= 30
  4188.2  264.39  4310.5  265.19  4410.6  262.74  4505.4   256.7  4522.1  256.74
  4655.8  246.23  4661.4  244.88  4722.7  242.22  4728.3  240.99  4789.6  240.02
  4795.2  238.81  4811.8  239.58    4862  236.51  4928.9  234.51  4967.9  234.42
  4982.7  229.33    4997  226.84  4999.8  226.34    5003  226.84  5012.5  228.72
  5018.1  232.93  5027.5  233.69  5072.4  235.53  5229.2  234.41  5590.1  234.64
  5704.4  236.07  5804.5  238.64  5960.6  250.54    5996  251.53  6060.6  249.89
#Mann= 3 ,-1 , 0
  4188.2     .15       0    4997     .05       0    5003     .15       0
Bank Sta=4967.9,5027.5
XS Rating Curve= 0 ,0
Exp/Cntr=0.3,0.1

Type RM Length L Ch R = 1 ,20441   ,502,502,502
BEGIN DESCRIPTION:
UNT 206 IN UKCR 32.0
END DESCRIPTION:
XS GIS Cut Line= 3
      3716699.63     10491010.16      3717149.61     10490560.19
      3717399.62     10489910.17
#Sta/Elev= 30
  4378.6  259.31    4421  257.45  4562.4  247.03  4647.3  241.97  4732.1  235.21
  4859.4  231.51  4972.5  232.09  4986.7  231.49    4997  224.88  4999.8  224.38
    5003  224.88  5011.4  230.69  5017.6  230.69    5030     232    5090   230.6
  5163.9  231.41  5229.2  230.61  5293.5  231.92  5303.2   231.3  5308.5   230.2
    5315  230.21  5325.7  231.62  5347.1  231.44  5393.2  232.81  5432.8  234.51
  5442.5  235.72  5497.1  238.75  5625.7  249.48  5647.1  251.78  5711.4  255.51
#Mann= 3 ,-1 , 0
  4378.6     .15       0    4997     .05       0    5003     .15       0
Bank Sta=4986.7,5011.4
XS Rating Curve= 0 ,0
Exp/Cntr=0.3,0.1

Type RM Length L Ch R = 1 ,19939   ,416,416,416
BEGIN DESCRIPTION:
UNT 206 IN UKCR 31.0
END DESCRIPTION:
XS GIS Cut Line= 3
      3716799.62     10491260.18      3717499.61     10490910.19
      3718299.65     10490660.18
#Sta/Elev= 30
  4207.2  260.82  4288.2  256.66  4416.8  247.95  4542.6  241.04  4573.3  238.47
  4578.9  239.02  4721.5  233.37    4864  229.15  4945.1  229.02  4981.4  229.77
    4987   225.3  4992.4   225.3    4997  223.83  4999.8  223.33    5003  223.83
    5006  224.41  5011.3  229.63  5043.8  229.75  5108.7  228.03  5173.7   229.4
    5367  228.55  5429.8  227.16  5471.2  229.29  5534.6  230.68  5644.1   237.9
  5649.9  239.13    5709  243.93    5774  247.16  5779.2  246.66    5828  248.76
#Mann= 3 ,-1 , 0
  4207.2     .15       0    4997     .05       0    5003     .15       0
Bank Sta=4981.4,5011.3
XS Rating Curve= 0 ,0
Exp/Cntr=0.3,0.1

Type RM Length L Ch R = 1 ,19523   ,488,488,488
BEGIN DESCRIPTION:
UNT 206 IN UKCR 30.0
END DESCRIPTION:
XS GIS Cut Line= 3
      3717749.61      10491560.2      3717849.61     10491110.19
      3718349.61     10490710.19
#Sta/Elev= 30
  4559.2  252.03  4675.7  243.82  4692.4  241.85  4825.6  231.86  4938.2  227.18
  4952.3  227.42  4958.7  228.65  4979.2  228.29  4994.6  224.05    4997  222.85
  4999.8  222.35    5003  222.85  5017.6  226.52  5023.4  226.52  5033.8   228.1
  5190.7  227.65  5219.5  227.01  5297.9  227.36  5340.3  230.83  5368.4  231.78
    5426  236.37  5440.4  238.11  5454.8  238.57  5532.4  246.99  5560.5  249.41
  5568.5  249.03  5603.7  251.33  5638.9  252.29  5646.9  253.42  5660.5  253.28
#Mann= 3 ,-1 , 0
  4559.2     .15       0    4997     .05       0    5003     .15       0
Bank Sta=4979.2,5033.8
XS Rating Curve= 0 ,0
Exp/Cntr=0.3,0.1

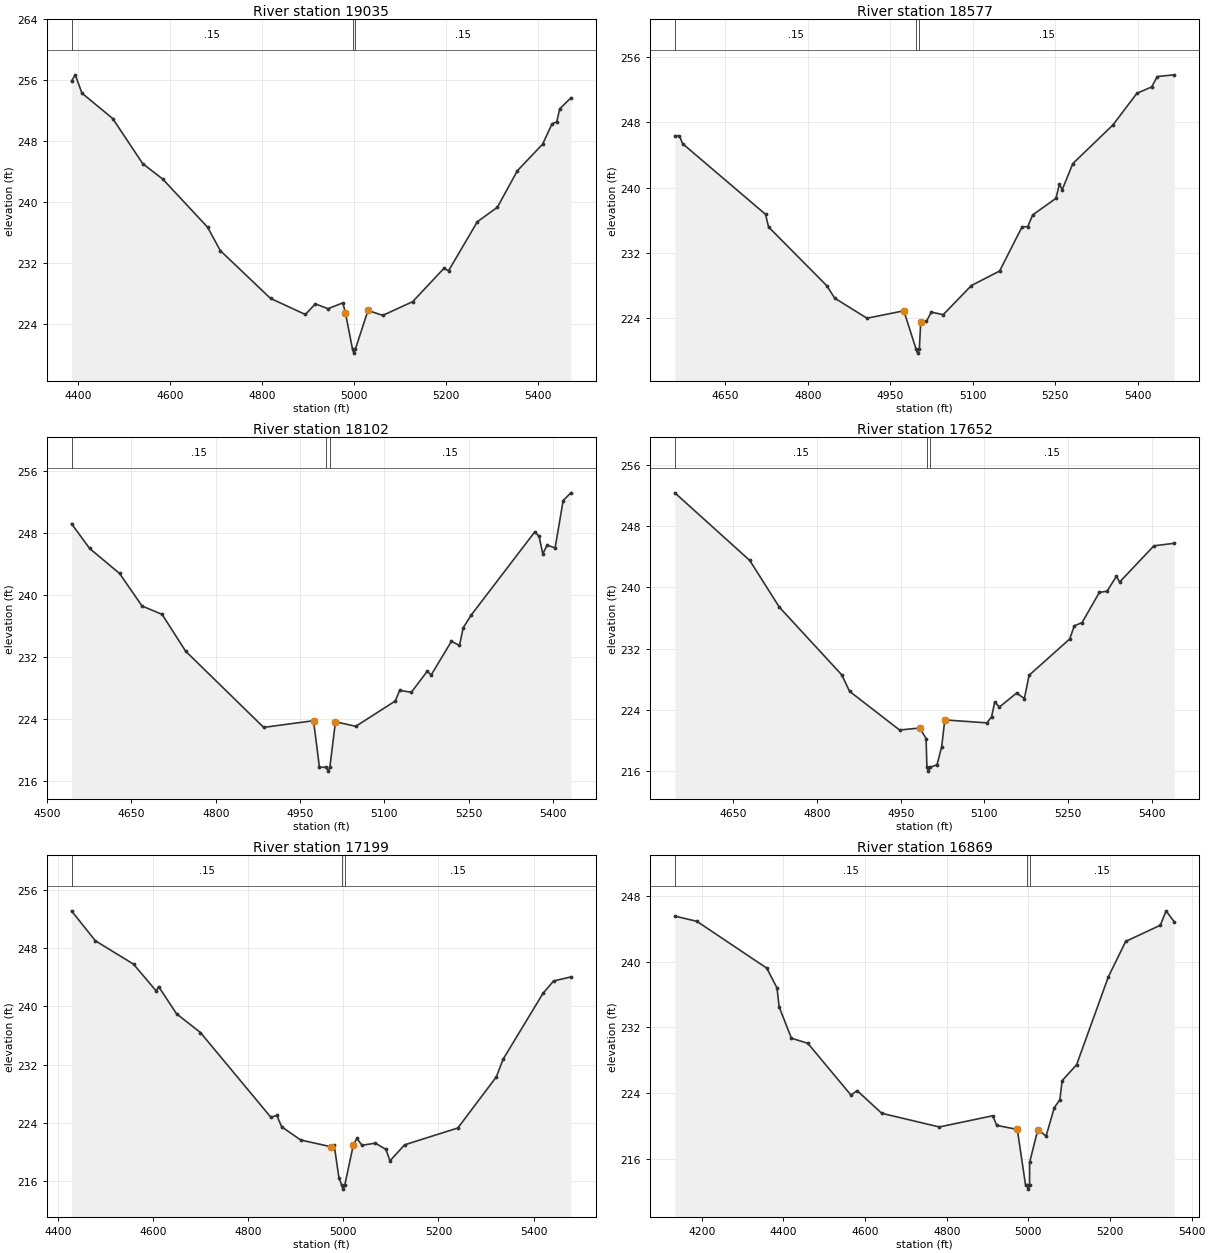
Type RM Length L Ch R = 1 ,19035   ,458,458,458
BEGIN DESCRIPTION:
UNT 206 IN UKCR 29.0
END DESCRIPTION:
XS GIS Cut Line= 3
       3717999.6     10491760.21      3718299.61     10491210.19
      3718399.61     10490760.19
#Sta/Elev= 30
  4384.9   255.9    4393  256.72  4407.7  254.31  4474.6  250.99  4540.1  245.06
  4583.8  243.03  4681.1  236.74  4709.1  233.65  4818.3  227.39  4894.2  225.28
    4916  226.67  4943.6  226.04  4975.8   226.8  4981.5   225.5    4997  220.71
  4999.8  220.21    5003  220.71  5030.6  225.81  5062.6  225.16  5127.9  226.96
  5195.8  231.32  5206.1  231.02  5268.8  237.45  5312.3  239.34  5355.9  244.14
  5410.9  247.62  5431.4  250.29  5441.7  250.55  5448.1  252.26  5472.4  253.69
#Mann= 3 ,-1 , 0
  4384.9     .15       0    4997     .05       0    5003     .15       0
Bank Sta=4981.5,5030.6
XS Rating Curve= 0 ,0
Exp/Cntr=0.3,0.1

Type RM Length L Ch R = 1 ,18577   ,475,475,475
BEGIN DESCRIPTION:
UNT 206 IN UKCR 28.0
END DESCRIPTION:
XS GIS Cut Line= 3
       3718499.6     10491810.21      3718699.61     10491410.19
      3718799.61     10490960.21
#Sta/Elev= 30
  4558.3  246.37  4566.7  246.36  4572.3   245.4  4723.2  236.71  4728.8  235.15
    4835  227.91    4849  226.41  4907.7  223.94  4974.8  224.85    4997  220.15
  4999.8  219.65    5003  220.15  5005.5  223.44  5015.8  223.54  5024.7  224.69
  5046.5  224.38  5097.7  227.96    5149  229.74  5189.9  235.18  5200.2  235.19
  5209.1  236.63  5251.4  238.67  5257.8  240.41  5262.9  239.74  5282.1  242.94
  5355.1  247.69  5398.7  251.58  5425.5  252.36  5435.8  253.64  5466.5  253.85
#Mann= 3 ,-1 , 0
  4558.3     .15       0    4997     .05       0    5003     .15       0
Bank Sta=4974.8,5005.5
XS Rating Curve= 0 ,0
Exp/Cntr=0.3,0.1

Type RM Length L Ch R = 1 ,18102   ,450,450,450
BEGIN DESCRIPTION:
UNT 206 IN UKCR 27.0
END DESCRIPTION:
XS GIS Cut Line= 3
       3718899.6     10492060.22      3719049.61     10491660.19
       3719349.6      10491310.2
#Sta/Elev= 30
  4543.5  249.16  4575.6  245.98    4629  242.75    4669  238.56  4704.6  237.49
  4746.5  232.75  4885.3  222.94    4974   223.8  4984.5  217.81    4997  217.81
  4999.8  217.31    5003  217.81    5013  223.66  5049.2  223.08  5119.5  226.34
  5127.1   227.7    5148  227.46  5176.5  230.19  5183.1  229.67  5219.3  234.02
  5233.6  233.48  5240.2  235.76  5254.5   237.4  5367.5   248.1  5375.2  247.53
  5381.8  245.27  5389.5  246.41  5403.7  246.03    5418  252.14  5431.7  253.13
#Mann= 3 ,-1 , 0
  4543.5     .15       0    4997     .05       0    5003     .15       0
Bank Sta=4974,5013
XS Rating Curve= 0 ,0
Exp/Cntr=0.3,0.1

Type RM Length L Ch R = 1 ,17652   ,453,453,453
BEGIN DESCRIPTION:
UNT 206 IN UKCR 26.0
END DESCRIPTION:
XS GIS Cut Line= 3
      3718949.61     10492110.19      3719349.61     10491910.19
      3719749.59      10491710.2
#Sta/Elev= 30
  4545.5  252.34  4679.7  243.51  4732.8   237.4  4844.6  228.56  4858.5  226.42
    4948  221.37  4984.3  221.63  4995.5  220.26    4997   216.5  4999.8     216
    5003   216.5  5015.1  216.84  5023.5  219.19    5029  222.69  5104.5   222.3
  5112.9  223.11  5118.5  225.04  5126.9  224.37  5157.6  226.19  5171.6  225.48
    5180  228.52  5252.7  233.25    5261  234.97    5275   235.4  5305.8  239.33
  5319.7   239.5  5336.5  241.45  5342.1  240.69  5403.6  245.42  5439.9  245.75
#Mann= 3 ,-1 , 0
  4545.5     .15       0    4997     .05       0    5003     .15       0
Bank Sta=4984.3,5029
XS Rating Curve= 0 ,0
Exp/Cntr=0.3,0.1

Type RM Length L Ch R = 1 ,17199   ,330,330,330
BEGIN DESCRIPTION:
UNT 206 IN UKCR 25.0
END DESCRIPTION:
XS GIS Cut Line= 3
      3718999.65     10492310.18      3719599.61     10492260.19
      3719999.56     10492060.21
#Sta/Elev= 30
    4429  253.12  4479.1  249.01  4559.4   245.8  4607.1  242.11  4612.1  242.73
  4649.7  238.99  4699.9  236.42  4847.9  224.79  4860.4  225.04  4870.5  223.49
  4910.6  221.67  4973.3  220.76  4980.9  220.98  4990.9  216.51    4997  215.43
  4999.8  214.93    5003  215.43    5021  220.95  5028.5   221.9  5039.4  220.95
  5067.4  221.24  5089.7  220.38  5098.1  218.81  5128.9  221.01  5240.7  223.32
  5321.7  230.34  5335.7  232.74  5419.6  241.79  5441.9  243.49  5478.2  244.05
#Mann= 3 ,-1 , 0
    4429     .15       0    4997     .05       0    5003     .15       0
Bank Sta=4973.3,5021
XS Rating Curve= 0 ,0
Exp/Cntr=0.3,0.1

Type RM Length L Ch R = 1 ,16869   ,425,425,425
BEGIN DESCRIPTION:
UNT 206 IN UKCR 24.0
END DESCRIPTION:
XS GIS Cut Line= 3
      3719972.24       10493174.      3719868.08     10492236.52
      3720069.48     10492042.07
#Sta/Elev= 30
    4134  245.54  4188.1   244.9  4359.2  239.21  4384.3   236.8  4389.4  234.51
  4419.6  230.69  4459.8  230.07  4565.4  223.78  4580.5  224.32  4640.9  221.56
  4781.8   219.9  4912.6  221.26  4922.6  220.09  4972.9   219.6  4993.1  212.84
    4997  212.84  4999.8  212.34    5003  212.84  5003.1   215.6  5023.3  219.59
  5043.4  218.79  5063.5  222.24  5077.2  223.22  5082.7  225.53  5118.2  227.47
  5195.9  238.15  5238.4  242.46  5323.3  244.43  5337.4  246.18  5357.2  244.85
#Mann= 3 ,-1 , 0
    4134     .15       0    4997     .05       0    5003     .15       0
Bank Sta=4972.9,5023.3
XS Rating Curve= 0 ,0
Exp/Cntr=0.3,0.1

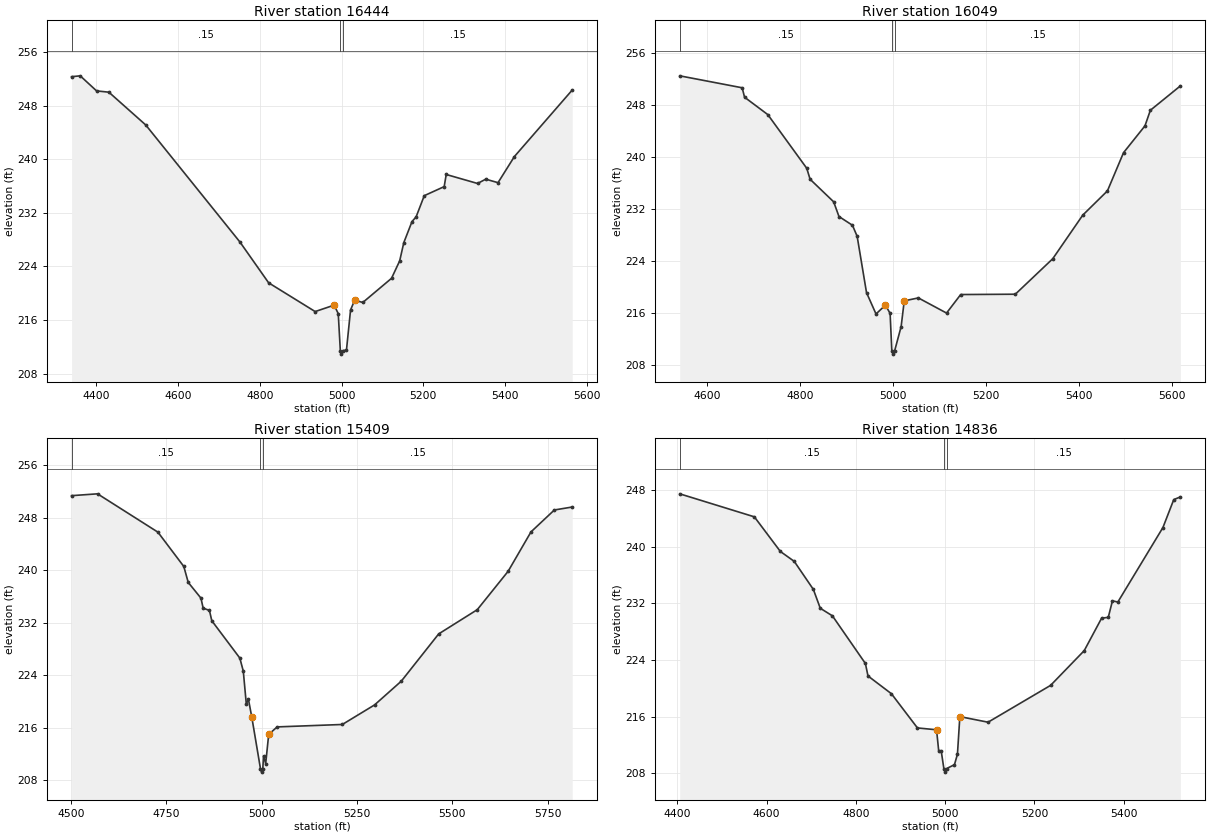
Type RM Length L Ch R = 1 ,16444   ,395,395,395
BEGIN DESCRIPTION:
UNT 206 IN UKCR 23.0
END DESCRIPTION:
XS GIS Cut Line= 2
      3720291.69     10493021.24       3720215.3     10491799.02
#Sta/Elev= 30
  4339.6  252.31  4360.7  252.44  4400.8  250.19  4430.8     250    4521  245.11
  4751.5  227.64  4821.6  221.56  4935.4  217.27  4981.9  218.23  4991.9  216.95
    4997  211.42  4999.8  210.92    5003  211.42    5012  211.54    5022  217.51
    5032  218.96    5052  218.63  5122.2  222.23  5142.2  224.84  5152.2  227.55
  5172.3   230.7  5182.3  231.39  5202.3  234.56    5251  235.91    5256  237.72
  5332.6  236.38  5352.6  237.02  5382.7   236.5  5422.8   240.4  5564.2  250.32
#Mann= 3 ,-1 , 0
  4339.6     .15       0    4997     .05       0    5003     .15       0
Bank Sta=4981.9,5032
XS Rating Curve= 0 ,0
Exp/Cntr=0.3,0.1

Type RM Length L Ch R = 1 ,16049   ,640,640,640
BEGIN DESCRIPTION:
UNT 206 IN UKCR 22.0
END DESCRIPTION:
XS GIS Cut Line= 3
      3720694.47     10492757.38      3720597.24     10492104.58
      3720389.41     10491744.33
#Sta/Elev= 30
  4541.2  252.46  4675.4  250.62  4680.5  249.17  4730.5  246.49  4814.1  238.24
  4821.4  236.54    4872  233.07  4883.4  230.81  4912.4  229.46  4922.5  227.76
  4942.6   219.1    4963  215.81  4983.2  217.17  4993.3   215.9    4997  210.13
  4999.8  209.63    5003  210.13    5017  213.87  5023.7  217.83    5054  218.28
  5114.6  215.95    5145   218.8  5262.4  218.85  5342.8  224.31  5407.4  231.03
  5460.3  234.75  5494.9  240.63    5541  244.76  5552.6  247.16  5617.1  250.91
#Mann= 3 ,-1 , 0
  4541.2     .15       0    4997     .05       0    5003     .15       0
Bank Sta=4983.2,5023.7
XS Rating Curve= 0 ,0
Exp/Cntr=0.3,0.1

Type RM Length L Ch R = 1 ,15409   ,573,573,573
BEGIN DESCRIPTION:
Mapping XS d9c9c25c
END DESCRIPTION:
XS GIS Cut Line= 3
      3720784.74      10492715.7      3721062.52      10492139.3
      3721159.56     10491473.88
#Sta/Elev= 30
  4501.8  251.38  4569.8  251.66  4728.1  245.82    4796  240.59  4807.6  238.16
  4840.9  235.77  4846.7  234.24  4863.1   233.9  4869.4  232.32  4942.8  226.64
  4951.9  224.65  4959.8  219.63  4965.4  220.35  4974.1  217.67    4997  209.76
  4999.8  209.26    5003  209.76  5005.1  211.75  5010.6  210.57  5018.5  215.01
  5040.7  216.15  5211.5  216.52    5296   219.5  5366.1  223.12  5464.1  230.32
  5565.2  234.01  5646.1  239.86    5706  245.86  5767.3   249.2  5814.1  249.65
#Mann= 3 ,-1 , 0
  4501.8     .15       0    4997     .05       0    5003     .15       0
Bank Sta=4974.1,5018.5
XS Rating Curve= 0 ,0
Exp/Cntr=0.3,0.1

Type RM Length L Ch R = 1 ,14836   ,680,680,680
BEGIN DESCRIPTION:
UNT 206 IN UKCR 21.0
END DESCRIPTION:
XS GIS Cut Line= 3
      3720999.57     10492660.21      3721499.61     10492360.19
      3721699.62     10491860.15
#Sta/Elev= 30
  4405.2  247.45  4572.4   244.2  4630.7  239.31  4661.8  237.91  4704.6  233.95
  4720.1  231.29  4747.3  230.22  4821.2  223.49    4827  221.73  4879.5  219.22
  4937.8  214.39  4980.6  214.13  4985.4  211.16    4991  211.16    4997  208.65
  4999.8  208.15    5003  208.65  5020.7   209.2  5027.4  210.67  5032.8  215.99
    5096   215.2  5236.1   220.4  5311.5  225.31  5350.5   229.9  5365.3     230
  5374.7  232.34  5386.8  232.17  5487.8  242.69  5512.1  246.64  5526.9  247.01
#Mann= 3 ,-1 , 0
  4405.2     .15       0    4997     .05       0    5003     .15       0
Bank Sta=4980.6,5032.8
XS Rating Curve= 0 ,0
Exp/Cntr=0.3,0.1