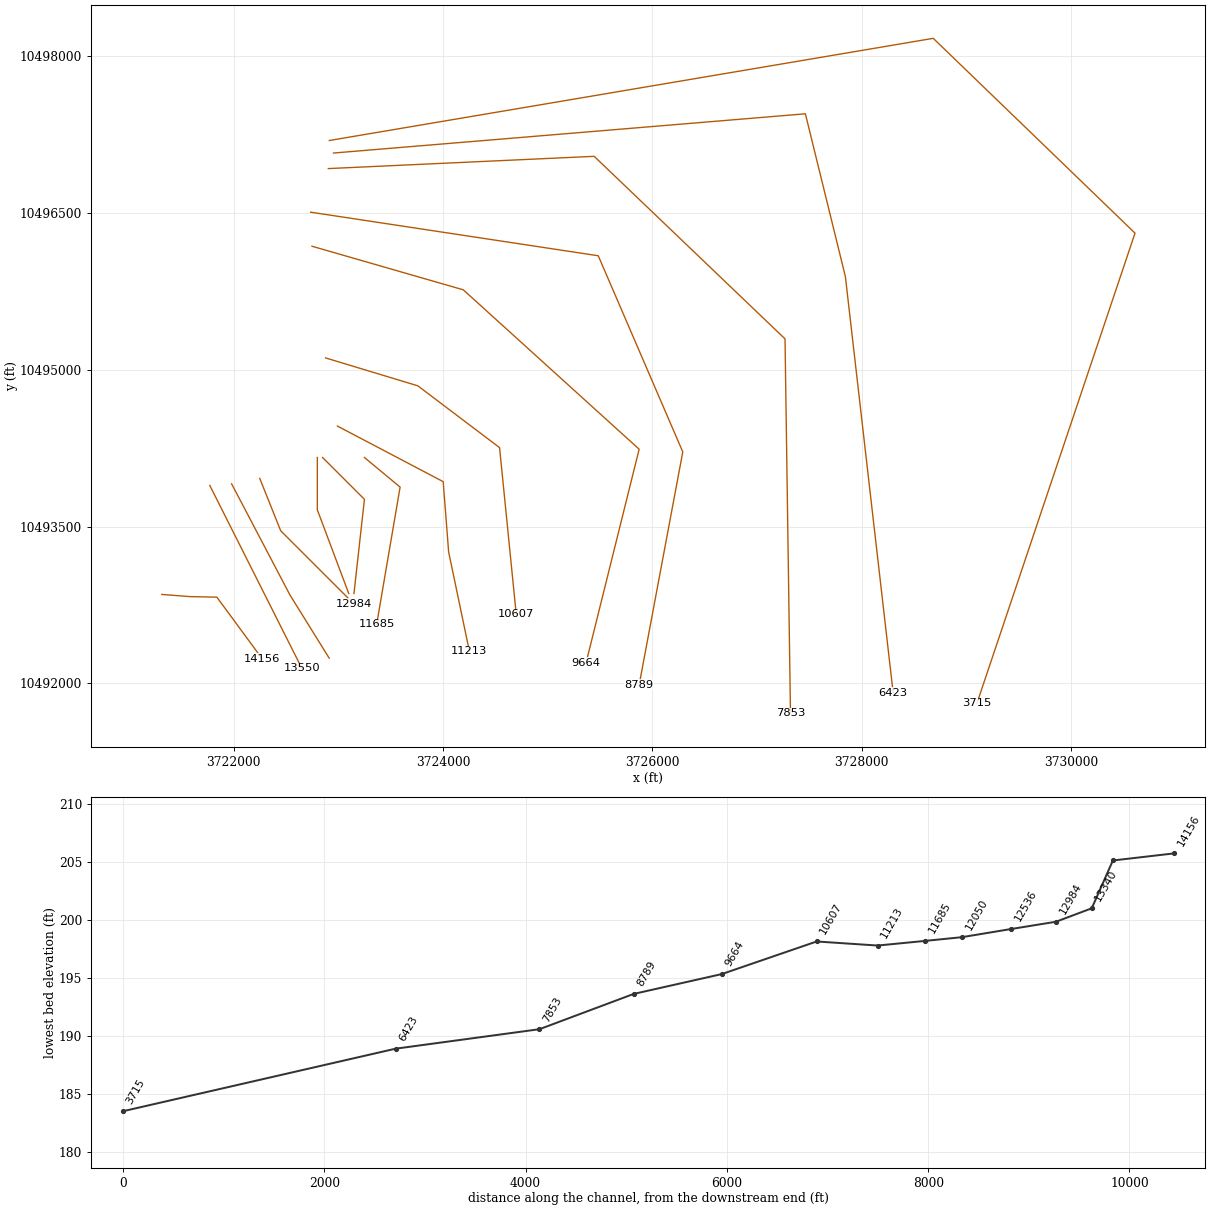
HEC-RAS study UNT 206 IN UKCR.prj: UNT 206 IN UKCR Base Level Engineering

--- UNT 206 IN UKCR.g01 (geometry) --- (continued)

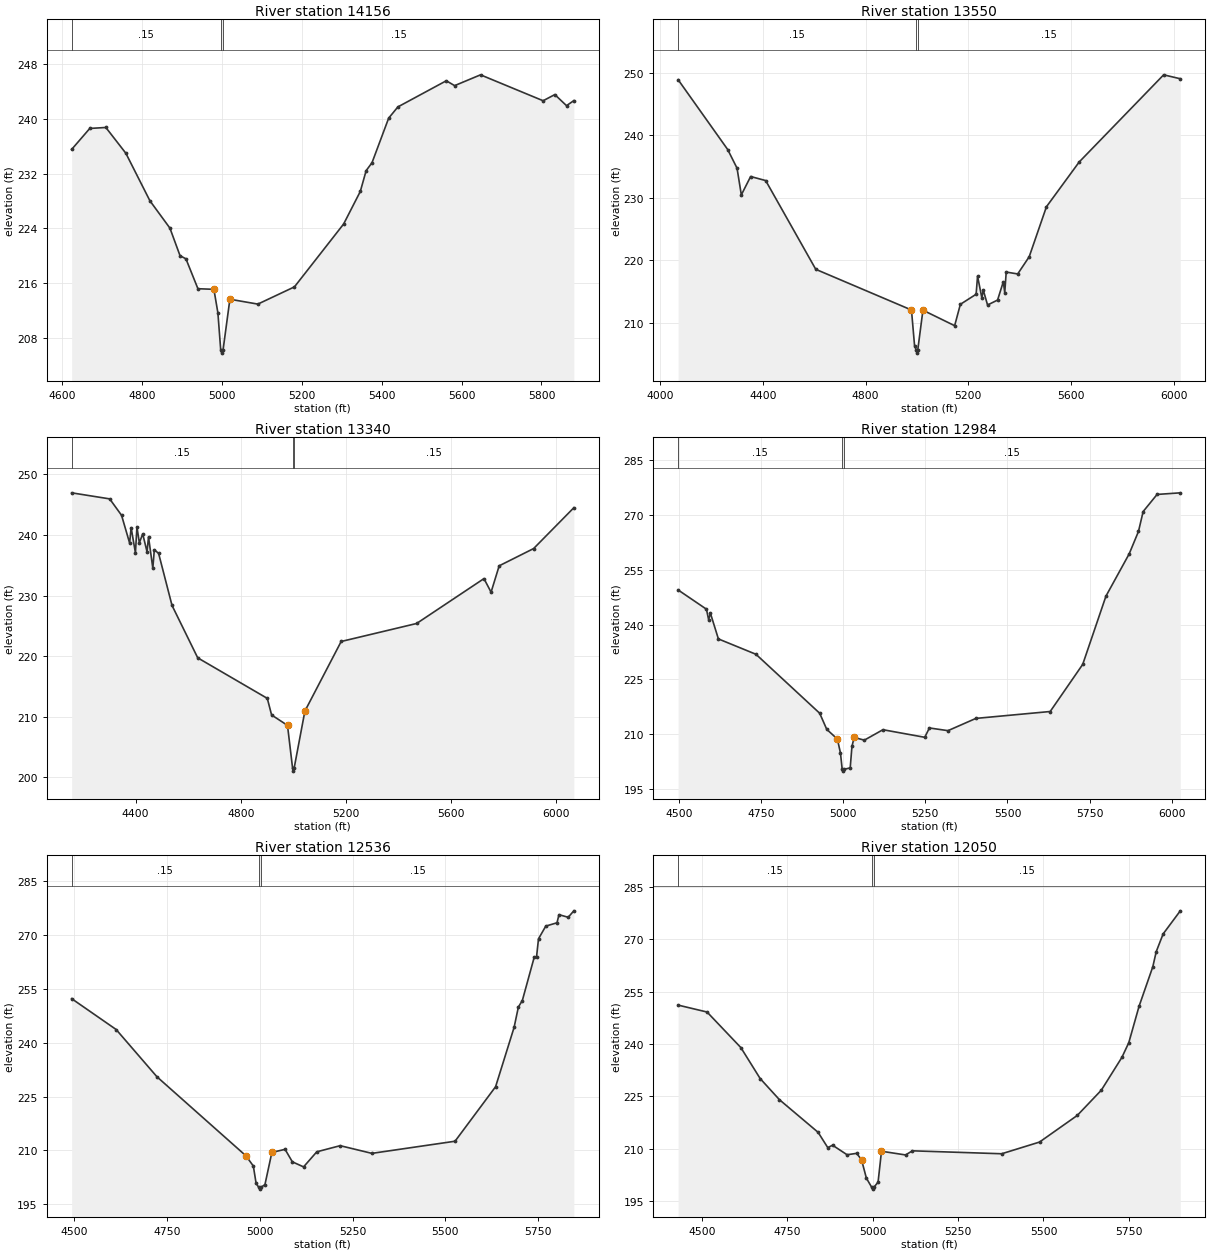
Type RM Length L Ch R = 1 ,14156   ,606,606,606
BEGIN DESCRIPTION:
UNT 206 IN UKCR 20.0
END DESCRIPTION:
XS GIS Cut Line= 4
      3721314.31      10492851.1      3721585.09     10492830.27
       3721840.3     10492825.07       3722272.6     10492236.52
#Sta/Elev= 30
  4623.9  235.53  4669.3   238.6  4709.5  238.74  4759.6  234.97  4819.8  228.02
  4869.9  224.02  4895.2  219.99    4910  219.53    4940  215.16    4980  215.07
    4990  211.62    4997  206.24  4999.8  205.74    5003  206.24    5020  213.62
    5090  212.91  5181.6  215.43  5304.8  224.63  5346.5  229.39  5361.1  232.43
  5375.8  233.59  5417.5  240.11  5440.6  241.75  5561.7  245.57  5582.6  244.86
  5647.4  246.44  5804.1  242.65  5833.4  243.55  5862.7  241.93    5881  242.67
#Mann= 3 ,-1 , 0
  4623.9     .15       0    4997     .05       0    5003     .15       0
Bank Sta=4980,5020
XS Rating Curve= 0 ,0
Exp/Cntr=0.3,0.1

Type RM Length L Ch R = 1 ,13550   ,210,210,210
BEGIN DESCRIPTION:
UNT 206 IN UKCR 19.0
END DESCRIPTION:
XS GIS Cut Line= 2
      3721772.61     10493892.75      3722652.19     10492143.99
#Sta/Elev= 30
  4068.9  248.88  4262.1  237.71  4298.6  234.72  4315.3  230.45  4351.6  233.39
  4410.2  232.74  4605.5  218.54  4978.5  212.03  4990.5  206.34    4997  205.63
  4999.8  205.13    5003  205.63  5023.2     212  5146.8  209.52  5169.1  212.94
  5230.5  214.55  5236.1  217.45  5252.8  213.98  5258.4  215.21  5275.1  212.83
  5314.1  213.62  5336.5  216.55  5342.1  214.82  5347.8   218.1  5392.6   217.8
  5437.4  220.55  5504.6  228.55  5632.2  235.71  5961.5  249.66  6026.4  249.03
#Mann= 3 ,-1 , 0
  4068.9     .15       0    4997     .05       0    5003     .15       0
Bank Sta=4978.5,5023.2
XS Rating Curve= 0 ,0
Exp/Cntr=0.3,0.1

Type RM Length L Ch R = 1 ,13340   ,356,356,356
BEGIN DESCRIPTION:
UNT 206 IN UKCR 18.0
END DESCRIPTION:
XS GIS Cut Line= 3
      3721980.95     10493908.36      3722538.22      10492845.9
      3722913.21     10492241.75
#Sta/Elev= 30
  4156.4  246.95  4301.1  245.95  4346.3  243.24    4377  238.66  4382.7   241.2
  4399.1  237.04  4404.8  241.32    4414   238.7  4426.8  240.17  4443.2  237.22
  4448.9  239.67  4465.3  234.49  4470.9  237.56  4487.3  236.95  4538.3  228.36
  4636.1  219.71  4900.8  213.02  4917.2  210.28  4977.7  208.56    4997  201.51
  4999.8  201.01    5003  201.51  5043.9  210.92  5181.9  222.41  5468.9  225.38
  5725.2  232.79  5752.3  230.55  5783.1   234.9  5914.2  237.75  6067.2  244.49
#Mann= 3 ,-1 , 0
  4156.4     .15       0    4997     .05       0    5003     .15       0
Bank Sta=4977.7,5043.9
XS Rating Curve= 0 ,0
Exp/Cntr=0.3,0.1

Type RM Length L Ch R = 1 ,12984   ,448,448,448
BEGIN DESCRIPTION:
UNT 206 IN UKCR 17.0
END DESCRIPTION:
XS GIS Cut Line= 3
      3722249.59     10493960.23      3722449.61     10493460.19
       3723149.6      10492760.2
#Sta/Elev= 30
  4497.6   249.5  4583.8  244.23  4590.5  241.35  4595.9  243.13  4620.2  236.08
  4734.6  231.87  4928.5  215.71    4950   211.3  4982.3  208.64  4991.7  204.84
    4997  200.35  4999.8  199.85    5003  200.35  5021.4  200.74  5026.7  206.65
  5033.5  209.08  5064.4  208.34    5121   211.2  5248.3  209.12  5262.4  211.68
    5319  210.94  5403.9   214.3  5630.1  216.19  5729.1  229.11  5799.8  247.81
  5870.5  259.39  5898.8  265.54    5913  270.99  5955.4  275.68  6026.1  276.12
#Mann= 3 ,-1 , 0
  4497.6     .15       0    4997     .05       0    5003     .15       0
Bank Sta=4982.3,5033.5
XS Rating Curve= 0 ,0
Exp/Cntr=0.3,0.1

Type RM Length L Ch R = 1 ,12536   ,486,486,486
BEGIN DESCRIPTION:
UNT 206 IN UKCR 16.0
END DESCRIPTION:
XS GIS Cut Line= 3
      3722799.61     10494160.15      3722799.61     10493660.19
      3723099.62     10492860.15
#Sta/Elev= 30
  4492.4  252.31  4612.4  243.71  4722.4  230.54  4962.4  208.51  4982.4  205.66
  4989.9  200.82    4997  199.72  4999.8  199.22    5003  199.72  5013.7  200.48
  5032.4  209.45    5068  210.31  5087.6  206.83  5117.9  205.42  5153.5  209.62
  5216.6  211.33  5302.1  209.19  5526.4  212.57  5635.8  227.77  5685.7  244.31
  5697.2  249.97  5707.9  251.79    5740  263.88  5746.2  263.94  5751.5  268.99
  5771.1  272.53  5801.4  273.46  5806.7  275.72  5831.6  274.99  5846.8  276.79
#Mann= 3 ,-1 , 0
  4492.4     .15       0    4997     .05       0    5003     .15       0
Bank Sta=4962.4,5032.4
XS Rating Curve= 0 ,0
Exp/Cntr=0.3,0.1

Type RM Length L Ch R = 1 ,12050   ,365,365,365
BEGIN DESCRIPTION:
UNT 206 IN UKCR 15.0
END DESCRIPTION:
XS GIS Cut Line= 3
      3722849.64     10494160.16      3723249.61     10493760.19
      3723149.61     10492860.17
#Sta/Elev= 30
  4429.7  251.12  4514.5  249.14  4613.5  238.98  4670.1  230.12  4726.6  224.08
  4839.8  214.76  4868.1  210.39  4882.2  211.07  4924.6  208.35  4952.9  208.75
  4967.1  206.89  4981.2  201.67    4997  199.02  4999.8  198.52    5003  199.02
  5015.5  200.53  5025.5  209.35    5096  208.29  5116.1  209.47  5377.7  208.63
  5488.4  211.97    5599  219.58  5669.5   226.8  5729.8  236.18    5750  240.39
  5780.1   250.8  5820.4   262.1  5830.4  266.41  5850.6  271.47  5900.9  278.07
#Mann= 3 ,-1 , 0
  4429.7     .15       0    4997     .05       0    5003     .15       0
Bank Sta=4967.1,5025.5
XS Rating Curve= 0 ,0
Exp/Cntr=0.3,0.1

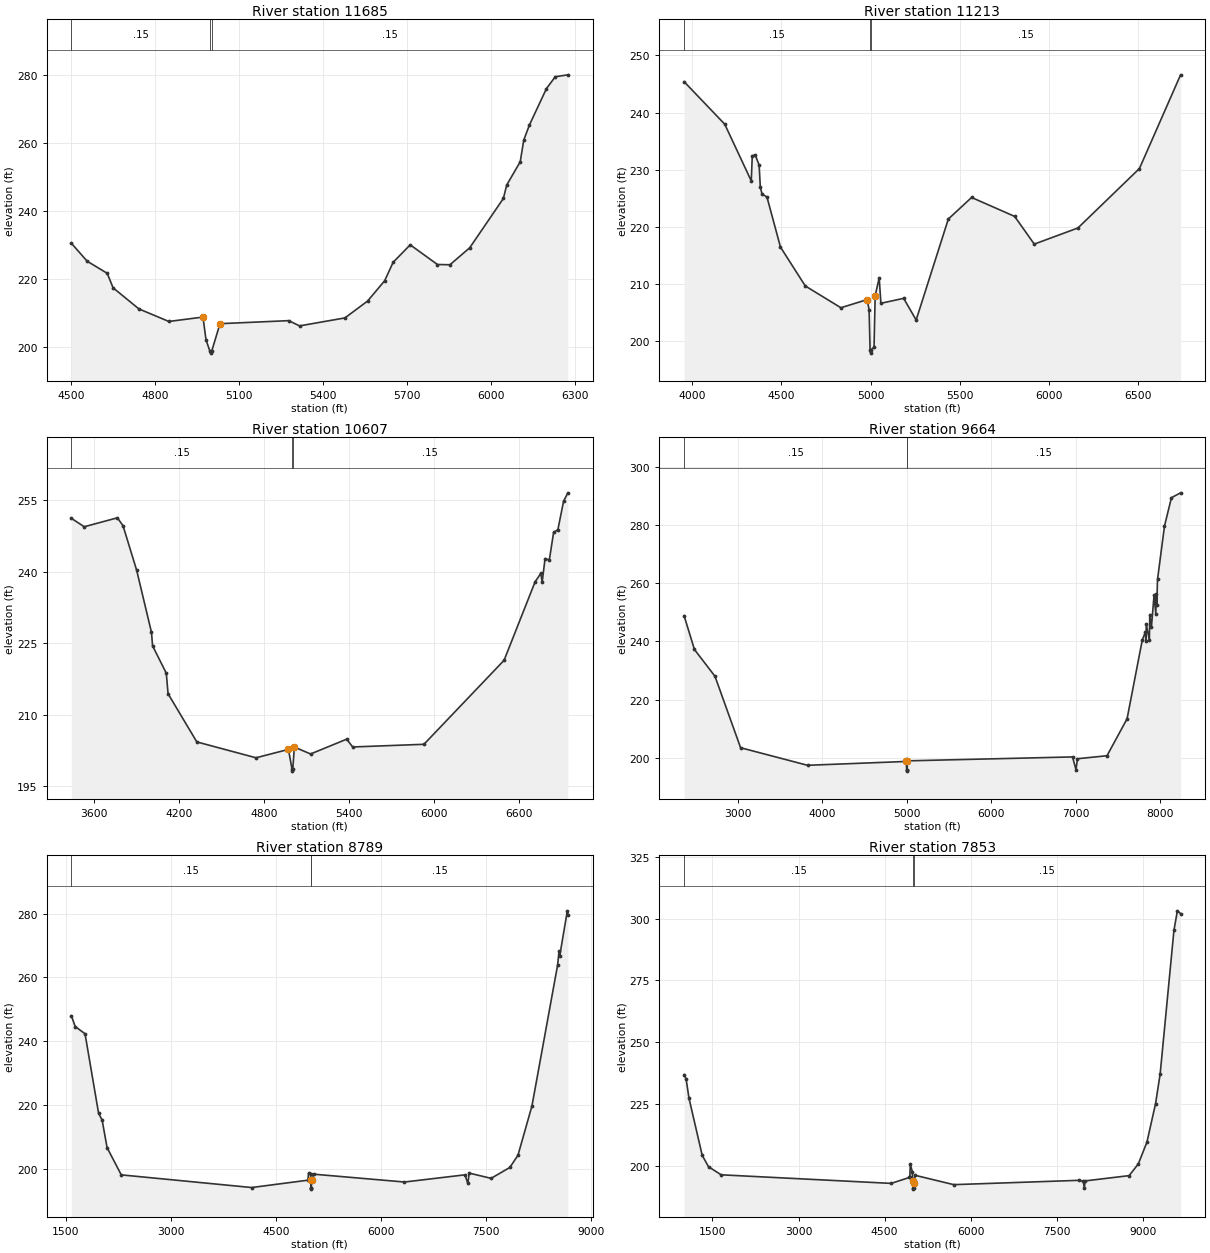
Type RM Length L Ch R = 1 ,11685   ,472,472,472
BEGIN DESCRIPTION:
UNT 206 IN UKCR 14.0
END DESCRIPTION:
XS GIS Cut Line= 3
      3723249.62     10494160.18       3723590.3     10493877.15
      3723366.39     10492564.93
#Sta/Elev= 30
  4501.8  230.47  4558.4  225.19    4630  221.64  4650.9  217.38  4743.3  211.18
  4850.1   207.5  4972.1  208.79  4982.9  202.14    4997   198.7  4999.8   198.2
    5003   198.7  5032.9  206.85  5278.6  207.74    5317   206.2  5479.3  208.54
  5560.4   213.5  5621.3  219.46  5651.7  224.89  5712.6  230.01  5809.9  224.23
  5854.6  224.16  5925.2  229.14  6045.5  243.63  6057.5  247.58  6105.7  254.41
  6118.4  260.79  6138.7  265.23  6199.5  275.92    6231  279.38  6275.9  279.94
#Mann= 3 ,-1 , 0
  4501.8     .15       0    4997     .05       0    5003     .15       0
Bank Sta=4972.1,5032.9
XS Rating Curve= 0 ,0
Exp/Cntr=0.3,0.1

Type RM Length L Ch R = 1 ,11213   ,606,606,606
BEGIN DESCRIPTION:
UNT 206 IN UKCR 13.0
END DESCRIPTION:
XS GIS Cut Line= 4
      3722991.36     10494460.47      3724001.76     10493929.23
      3724053.84     10493257.36      3724251.76     10492309.43
#Sta/Elev= 30
  3954.1  245.41    4182  237.95  4330.7     228  4336.3  232.39  4352.7  232.57
  4374.8  230.77  4381.4  226.91  4391.2  225.71  4418.8  225.17  4494.4   216.4
  4633.6  209.58  4833.4  205.76  4980.6  207.19  4991.4  205.41    4997   198.3
  4999.8   197.8    5003   198.3  5019.1   198.9  5025.4  207.88    5048  210.99
  5057.5  206.54    5185  207.41  5255.2  203.61  5435.7  221.32  5566.1   225.1
  5807.5  221.78  5917.4  216.92  6162.3  219.75  6507.2  230.18  6737.9  246.61
#Mann= 3 ,-1 , 0
  3954.1     .15       0    4997     .05       0    5003     .15       0
Bank Sta=4980.6,5025.4
XS Rating Curve= 0 ,0
Exp/Cntr=0.3,0.1

Type RM Length L Ch R = 1 ,10607   ,943,943,943
BEGIN DESCRIPTION:
UNT 206 IN UKCR 11.0
END DESCRIPTION:
XS GIS Cut Line= 4
      3722878.74     10495111.78      3723759.37     10494845.25
      3724540.18     10494254.49       3724699.6     10492660.23
#Sta/Elev= 30
  3441.4   251.2  3532.2  249.43  3766.2  251.31  3806.1  249.61    3902  240.29
  4006.5  227.25  4014.1  224.45    4111  218.69  4123.3  214.39  4326.2  204.28
  4743.5  200.95  4972.4  202.71    4997  198.65  4999.8  198.15    5003  198.65
    5014   203.2  5128.5  201.75  5382.6  204.85  5425.3  203.22  5927.8  203.78
  6493.1  221.41  6711.7  237.87  6751.9  239.64  6761.9  237.83    6782  242.76
  6812.2  242.47  6842.3  248.23  6872.5  248.83  6912.7  254.79  6942.8  256.55
#Mann= 3 ,-1 , 0
  3441.4     .15       0    4997     .05       0    5003     .15       0
Bank Sta=4972.4,5014
XS Rating Curve= 0 ,0
Exp/Cntr=0.3,0.1

Type RM Length L Ch R = 1 ,9664    ,875,875,875
BEGIN DESCRIPTION:
UNT 206 IN UKCR 9.0
END DESCRIPTION:
XS GIS Cut Line= 4
      3722748.52     10496179.49      3724193.84     10495762.82
      3725873.53     10494239.38      3725365.72     10492195.13
#Sta/Elev= 30
  2361.6  248.87  2483.9  237.24    2727  228.02  3030.5   203.4    3823  197.35
  4990.4  198.67    4997  195.84  4999.8  195.34    5003  195.84  5004.6  198.88
  6960.3  200.23  7001.6  195.84  7018.7  199.61  7368.6  200.64  7606.1  213.36
  7787.2  240.64  7822.4  243.19  7828.6  240.11  7833.7  245.92  7869.9  240.41
  7875.1  249.28  7894.6     245  7925.5  255.89  7946.1   249.6  7952.6  256.25
  7957.8  252.73  7966.7  261.37  8049.1  279.75  8131.6  289.53  8239.8   291.2
#Mann= 3 ,-1 , 0
  2361.6     .15       0    4997     .05       0    5003     .15       0
Bank Sta=4990.4,5004.6
XS Rating Curve= 0 ,0
Exp/Cntr=0.3,0.1

Type RM Length L Ch R = 1 ,8789    ,936,936,936
BEGIN DESCRIPTION:
UNT 206 IN UKCR 7.0
END DESCRIPTION:
XS GIS Cut Line= 4
      3722735.48     10496505.01       3725482.9     10496088.34
      3726290.19     10494213.34      3725873.52     10491986.74
#Sta/Elev= 30
  1578.4     248  1633.1  244.62  1773.5  242.34  1966.9  217.42  2017.5  215.26
  2088.3  206.63  2290.6   198.1  4151.6  194.13    4954  196.43    4964  198.72
  4992.9  198.53 4995.57  196.42    4997  194.13  4999.8  193.63    5003  194.13
 5005.98   196.4    5040  198.31  6332.6  195.86  7195.4  198.11  7236.1  195.43
  7256.4  198.65  7568.7  197.01  7836.3  200.43  7952.3  204.27  8151.7  219.73
    8518  263.92  8538.3  268.27  8546.3  266.57  8656.6  280.89  8663.9  279.53
#Mann= 3 ,-1 , 0
  1578.4     .15       0    4997     .05       0    5003     .15       0
Bank Sta=4995.57,5005.98
XS Rating Curve= 0 ,0
Exp/Cntr=0.3,0.1

Type RM Length L Ch R = 1 ,7853    ,1430,1430,1430
BEGIN DESCRIPTION:
UNT 206 IN UKCR 5.0
END DESCRIPTION:
XS GIS Cut Line= 4
      3722904.77     10496921.67      3725443.84     10497038.86
      3727266.75     10495294.07      3727318.82     10491714.28
#Sta/Elev= 30
  1007.7  236.89  1042.6  235.13  1092.6  227.37  1322.9  204.25    1433  199.64
  1653.2  196.38  4613.5  192.91  4931.7  195.32    4939  195.58  4945.9  200.73
  4981.4  197.66 4991.35  193.78    4997  191.09  4999.8  190.59    5003  191.09
  5009.7  193.09  5030.8  196.18  5702.9   192.4  7886.9  194.15  7956.9  193.81
  7976.9  191.09    7990  193.91    8757  196.05    8917  200.79    9067   209.6
    9217  225.13  9297.1  237.16  9537.1   295.2  9597.1  303.12    9653  302.01
#Mann= 3 ,-1 , 0
  1007.7     .15       0    4997     .05       0    5003     .15       0
Bank Sta=4991.35,5009.7
XS Rating Curve= 0 ,0
Exp/Cntr=0.3,0.1

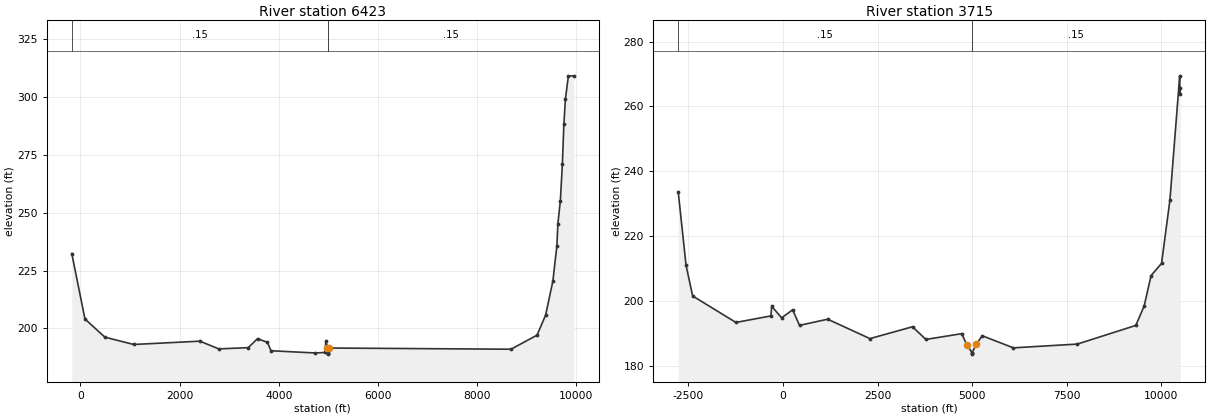
Type RM Length L Ch R = 1 ,6423    ,2708,2708,2708
BEGIN DESCRIPTION:
UNT 206 IN UKCR 3.0
END DESCRIPTION:
XS GIS Cut Line= 4
      3722954.26     10497070.29       3727461.2     10497445.29
      3727843.14     10495889.73      3728299.61      10491910.2
#Sta/Elev= 30
  -175.4  232.38    90.9  204.09   492.3  196.24  1074.3  193.08  2408.9  194.51
  2790.2  191.18  3384.2   191.7  3572.9   195.6  3773.6  193.98  3843.8  190.37
  4738.7  189.41    4929  189.62  4951.6  194.49 4982.45  191.58    4997  189.41
  4999.8  188.91    5003  189.41 5008.52  191.55  8686.7  191.03  9211.7  197.11
    9385  205.76  9531.8  220.53  9612.3  235.74  9632.4  245.26  9682.7  255.25
    9723  271.02  9753.2  288.16  9783.4  298.96  9843.8  309.04  9954.5  309.18
#Mann= 3 ,-1 , 0
  -175.4     .15       0    4997     .05       0    5003     .15       0
Bank Sta=4982.45,5008.52
XS Rating Curve= 0 ,0
Exp/Cntr=0.3,0.1

Type RM Length L Ch R = 1 ,3715    ,0,0,0
BEGIN DESCRIPTION:
UNT 206 IN UKCR 2.0
END DESCRIPTION:
XS GIS Cut Line= 4
       3722914.3     10497190.07      3728682.55     10498166.64
      3730609.64     10496304.66       3729099.6     10491810.15
#Sta/Elev= 30
 -2767.9  233.58 -2561.1  210.92 -2387.3  201.48 -1242.9   193.3  -318.2  195.32
  -297.9   198.3   -34.2  194.72   256.5  197.21   437.6   192.4  1182.8   194.3
  2299.3  188.31  3424.5  191.97  3777.9  188.05  4725.6  189.84  4859.9  186.41
    4997  184.02  4999.8  183.52    5003  184.02  5114.6  186.66  5270.2  189.18
  6090.2  185.46  7781.7  186.62  9326.6  192.38  9547.3  198.35  9731.1  207.77
 10007.6  211.53 10229.2  231.11 10487.7  269.44   10493  263.87 10503.5  265.74
#Mann= 3 ,-1 , 0
 -2767.9     .15       0    4997     .05       0    5003     .15       0
Bank Sta=4859.9,5114.6
XS Rating Curve= 0 ,0
Exp/Cntr=0.3,0.1

Chan Stop Cuts=-1
Use User Specified Reach Order=0
Composite Channel Slope=5