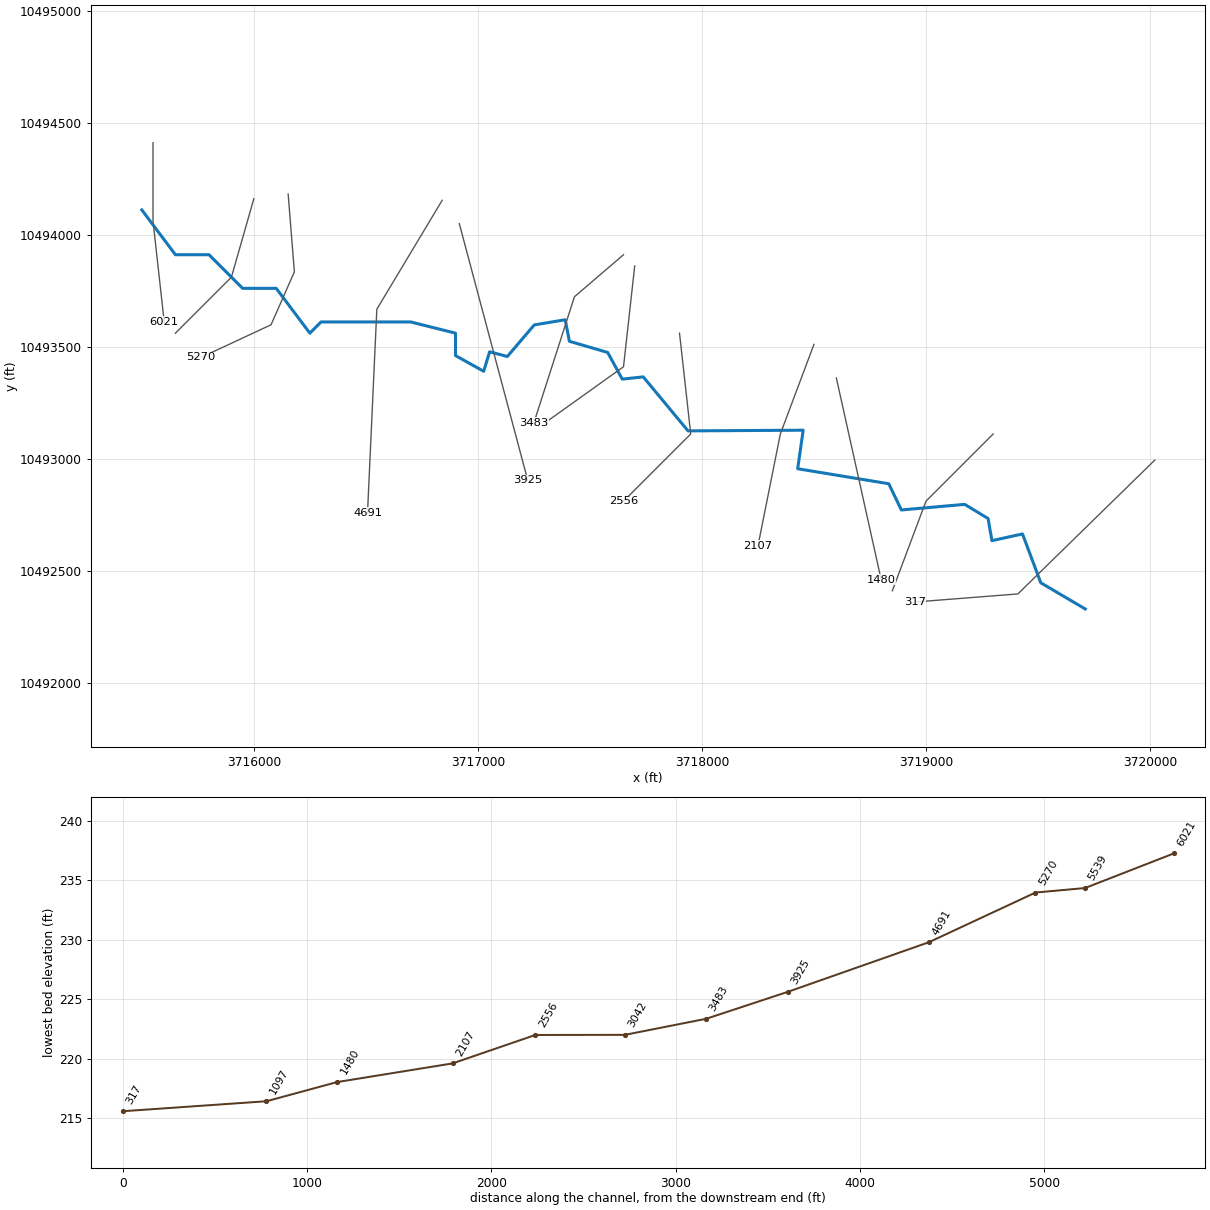
--- UNT 207 IN UKCR.prj (project) ---

Proj Title=UNT 207 IN UKCR Base Level Engineering
Current Plan=p01
Default Exp/Contr=0.3,0.1
English Units
Geom File=g01
Flow File=f01
Plan File=p01
BEGIN DESCRIPTION:
UNT 207 IN UKCR
END DESCRIPTION:

--- UNT 207 IN UKCR.p01 (plan) ---

Plan Title=Multiple Run
Short Identifier=Multiple
Geom File=g01
Flow File=f01
Subcritical Flow
K Sum by GR= 0
Std Step Tol= 0.01
Critical Tol= 0.01
Num of Std Step Trials= 20
Max Error Tol= 0.3
Flow Tol Ratio= 0.001
Split Flow NTrial= 30
Split Flow Tol= 0.02
Split Flow Ratio= 0.02
Log Output Level= 0
Friction Slope Method= 1
Unsteady Friction Slope Method= 2
Unsteady Bridges Friction Slope Method= 1
Parabolic Critical Depth
Global Vel Dist=  1 , 1 , 1
Global Log Level= 0
CheckData=True
Encroach Param= -1, 0, 0, 0
BEGIN DESCRIPTION:
Multiple Run
END DESCRIPTION:

--- UNT 207 IN UKCR.f01 (steady flow) ---

Flow Title=Multiple
Number of Profiles=7
Profile Names=10-year,25-year,50-year,1pct_min,100-year,1pct_plu,500-year
River Rch & RM= UNT 207 IN UKCR,Reach-1,6021
     692     951    1169    1055    1427    1930    2136
Boundary for River Rch & Prof#=UNT 207 IN UKCR,Reach-1,1
Up Type=0
Dn Type=3
Dn Slope=0.005
Boundary for River Rch & Prof#=UNT 207 IN UKCR,Reach-1,2
Up Type=0
Dn Type=3
Dn Slope=0.005
Boundary for River Rch & Prof#=UNT 207 IN UKCR,Reach-1,3
Up Type=0
Dn Type=3
Dn Slope=0.005
Boundary for River Rch & Prof#=UNT 207 IN UKCR,Reach-1,4
Up Type=0
Dn Type=3
Dn Slope=0.005
Boundary for River Rch & Prof#=UNT 207 IN UKCR,Reach-1,5
Up Type=0
Dn Type=3
Dn Slope=0.005
Boundary for River Rch & Prof#=UNT 207 IN UKCR,Reach-1,6
Up Type=0
Dn Type=3
Dn Slope=0.005
Boundary for River Rch & Prof#=UNT 207 IN UKCR,Reach-1,7
Up Type=0
Dn Type=3
Dn Slope=0.005

--- UNT 207 IN UKCR.g01 (geometry) ---

Geom Title=Existing Conditions

River Reach=UNT 207 IN UKCR,Reach-1
Reach XY= 30
      3715499.61     10494110.19      3715649.61     10493910.19
      3715799.61     10493910.19      3715949.61     10493760.19
      3716099.61     10493760.19      3716249.61     10493560.19
      3716299.61     10493610.19      3716699.61     10493610.19
      3716899.61     10493560.19      3716899.61     10493460.19
      3717025.50     10493390.00      3717052.00     10493477.00
      3717131.00     10493456.00      3717251.25     10493597.00
      3717389.50     10493620.00      3717408.00     10493524.00
      3717579.00     10493474.00      3717644.00     10493355.00
      3717737.75     10493365.00      3717937.50     10493124.00
      3718451.50     10493127.00      3718427.00     10492955.00
      3718833.50     10492888.00      3718889.75     10492771.00
      3719172.50     10492796.00      3719276.75     10492733.00
      3719294.00     10492634.00      3719430.50     10492664.00
      3719512.00     10492446.00      3719710.75     10492329.00

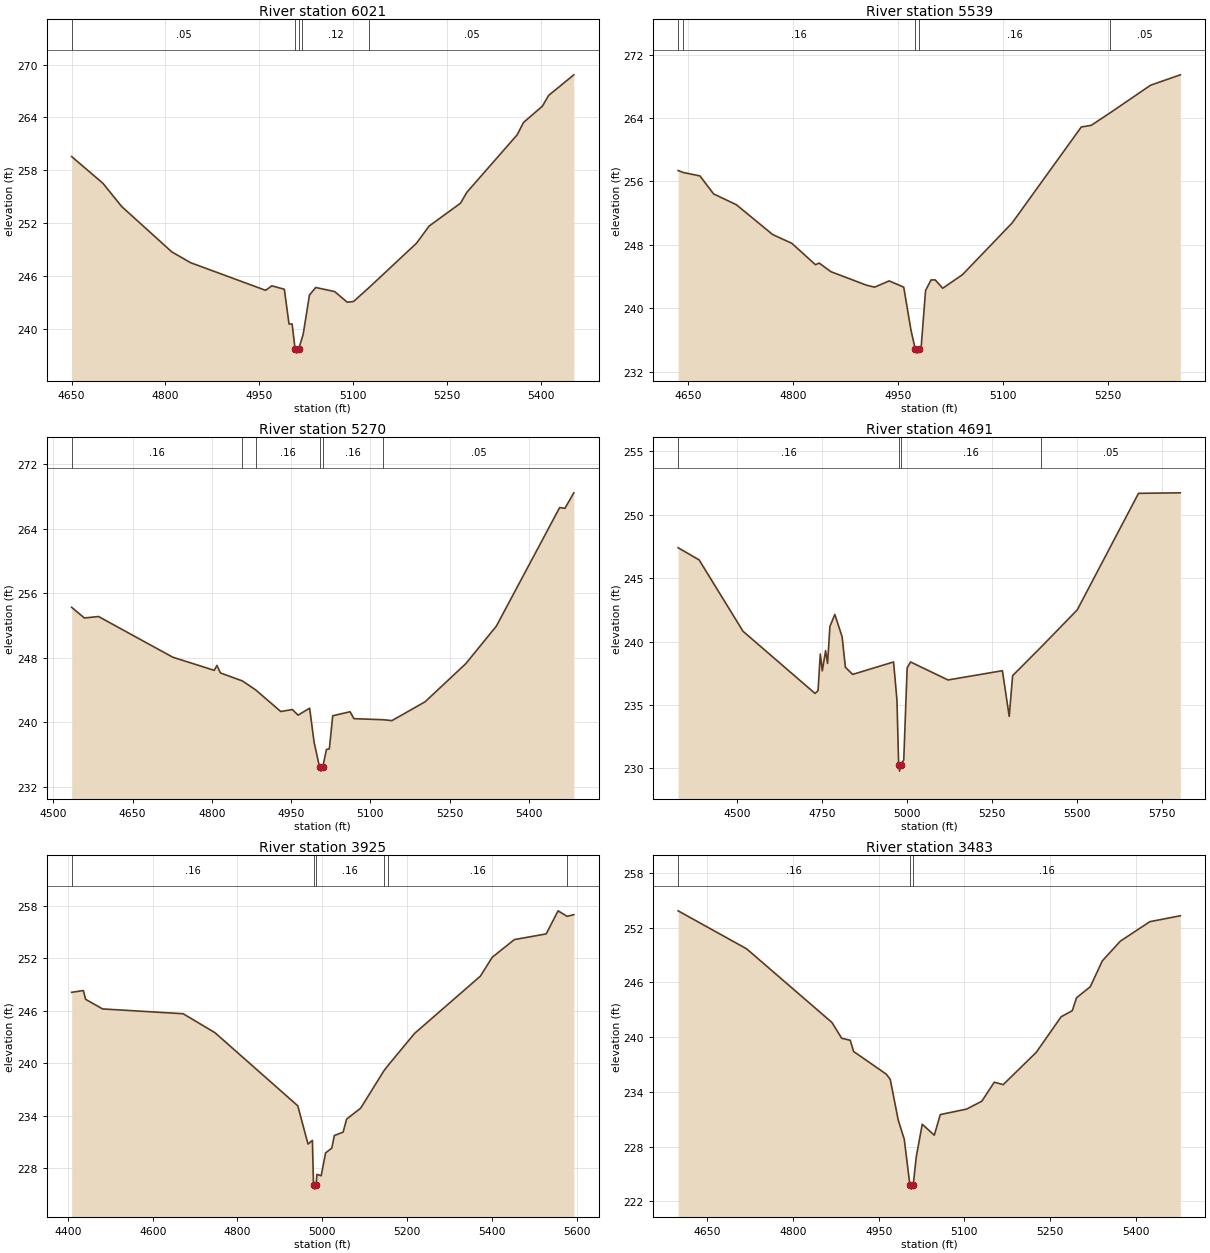
Type RM Length L Ch R = 1,6021,482,482,482
BEGIN DESCRIPTION:
UNT 207 IN UKCR 12.0
END DESCRIPTION:
XS GIS Cut Line= 3
      3715549.61     10494410.19      3715549.61     10494060.19
      3715599.61     10493610.16
#Sta/Elev= 30
  4650.0  259.56  4700.0  256.53  4730.0  253.89  4810.0  248.75  4840.0  247.52
  4960.0  244.38  4970.0  244.89  4990.0  244.50  4997.5  240.56  5002.5  240.56
  5007.1  237.75  5009.8  237.25  5013.1  237.75  5017.7  238.82  5020.1  239.38
  5030.2  243.85  5040.2  244.70  5070.4  244.24  5090.6  243.03  5100.6  243.11
  5126.0  244.73  5201.2  249.72  5221.4  251.67  5271.7  254.27  5281.7  255.50
  5362.2  262.03  5372.3  263.43  5402.5  265.28  5412.5  266.50  5452.8  268.84
#Mann=5,-1,0
  4650.0    0.05       0  5007.1    0.03       0  5013.1    0.05       0
  5017.7    0.12       0  5126.0    0.05       0
Bank Sta=5007.1,5013.1
Exp/Cntr=0.3,0.1

Type RM Length L Ch R = 1,5539,269,269,269
BEGIN DESCRIPTION:
UNT 207 IN UKCR 11.0
END DESCRIPTION:
XS GIS Cut Line= 3
      3715999.61     10494160.18      3715899.61     10493810.19
      3715649.58     10493560.16
#Sta/Elev= 30
  4636.0  257.37  4643.4  257.12  4667.2  256.69  4686.7  254.42  4719.2  253.06
  4771.2  249.29  4798.5  248.19  4832.3  245.49  4837.5  245.70  4854.4  244.61
  4905.1  242.91  4916.8  242.66  4937.6  243.45  4958.4  242.66  4968.8  237.21
  4974.9  234.84  4977.6  234.34  4980.9  234.84  4983.1  234.86  4989.6  242.24
  4997.4  243.57  5003.5  243.57  5014.1  242.52  5042.4  244.24  5113.1  250.74
  5212.1  262.86  5226.3  263.07  5252.9  264.62  5311.1  268.13  5353.6  269.44
#Mann=5,-1,0
  4636.0    0.05       0  4643.4    0.16       0  4974.9    0.07       0
  4980.9    0.16       0  5252.9    0.05       0
Bank Sta=4974.9,4980.9
Exp/Cntr=0.3,0.1

Type RM Length L Ch R = 1,5270,579,579,579
BEGIN DESCRIPTION:
UNT 207 IN UKCR 10.0
END DESCRIPTION:
XS GIS Cut Line= 4
      3716152.80     10494180.94      3716180.58     10493833.75
      3716076.41     10493597.64      3715764.30     10493451.98
#Sta/Elev= 30
  4534.5  254.26  4558.7  252.94  4585.4  253.12  4725.9  248.08  4804.5  246.45
  4809.5  247.06  4816.2  246.13  4857.7  245.14  4882.9  244.03  4930.4  241.35
  4952.4  241.59  4963.2  240.90  4985.1  241.76  4993.6  237.51  5003.9  234.46
  5006.7  233.96  5009.9  234.46  5016.9  236.64  5022.4  236.72  5028.8  240.82
  5061.6  241.32  5069.0  240.46  5124.6  240.33  5140.9  240.22  5203.6  242.55
  5280.8  247.28  5338.7  251.94  5458.5  266.63  5468.4  266.53  5485.3  268.45
#Mann=6,-1,0
  4534.5    0.16       0  4857.7    0.05       0  4882.9    0.16       0
  5003.9    0.07       0  5009.9    0.16       0  5124.6    0.05       0
Bank Sta=5003.9,5009.9
Exp/Cntr=0.3,0.1

Type RM Length L Ch R = 1,4691,766,766,766
BEGIN DESCRIPTION:
UNT 207 IN UKCR 9.0
END DESCRIPTION:
XS GIS Cut Line= 3
      3716840.30     10494153.19      3716548.63     10493667.08
      3716506.97     10492757.33
#Sta/Elev= 30
  4326.1  247.40  4387.9  246.44  4517.1  240.81  4728.9  235.91  4737.8  236.12
  4744.5  239.02  4750.3  237.69  4760.0  239.28  4765.8  238.28  4772.8  241.19
  4787.2  242.14  4808.6  240.38  4818.3  237.97  4839.7  237.41  4960.0  238.39
  4970.0  235.40  4975.0  230.28  4977.7  229.78  4981.0  230.28  4990.0  230.66
  5000.0  237.93  5010.0  238.39  5120.1  236.97  5280.3  237.70  5300.3  234.10
  5310.3  237.31  5394.3  239.57  5500.5  242.50  5680.7  251.69  5803.7  251.73
#Mann=4,-1,0
  4326.1    0.16       0  4975.0    0.07       0  4981.0    0.16       0
  5394.3    0.05       0
Bank Sta=4975,4981
Exp/Cntr=0.3,0.1

Type RM Length L Ch R = 1,3925,442,442,442
BEGIN DESCRIPTION:
UNT 207 IN UKCR 8.0
END DESCRIPTION:
XS GIS Cut Line= 2
      3716916.69     10494049.02      3717221.97     10492904.23
#Sta/Elev= 30
  4408.8  248.12  4436.5  248.32  4441.7  247.32  4481.8  246.22  4671.9  245.67
  4747.0  243.50  4942.3  235.14  4966.5  230.76  4976.8  231.19  4979.4  226.11
  4982.2  225.61  4985.4  226.11  4987.6  227.30  4997.5  227.14  5007.9  229.75
  5022.5  230.30  5028.6  231.74  5049.3  232.13  5057.5  233.62  5090.7  234.87
  5145.3  239.13  5156.0  239.80  5217.9  243.42  5373.1  249.97  5401.1  252.13
  5453.3  254.15  5528.4  254.80  5556.4  257.44  5577.7  256.81  5593.6  257.00
#Mann=6,-1,0
  4408.8    0.16       0  4979.4    0.07       0  4985.4    0.16       0
  5145.3    0.12       0  5156.0    0.16       0  5577.7    0.08       0
Bank Sta=4979.4,4985.4
Exp/Cntr=0.3,0.1

Type RM Length L Ch R = 1,3483,441,441,441
BEGIN DESCRIPTION:
UNT 207 IN UKCR 7.0
END DESCRIPTION:
XS GIS Cut Line= 3
      3717649.57     10493910.16      3717430.58     10493722.64
      3717249.59     10493160.14
#Sta/Elev= 30
  4598.8  253.85  4718.9  249.68  4868.2  241.61  4885.1  239.89  4900.2  239.66
  4906.0  238.44  4963.2  235.95  4970.2  235.38  4984.2  230.91  4994.7  228.82
  5004.5  223.85  5007.3  223.35  5010.5  223.85  5015.7  226.88  5026.2  230.46
  5047.3  229.26  5057.8  231.52  5103.8  232.12  5130.6  232.99  5152.3  235.07
  5167.9  234.80  5225.8  238.34  5269.4  242.24  5288.9  242.91  5296.3  244.32
  5320.4  245.53  5341.4  248.36  5372.9  250.52  5424.6  252.66  5478.0  253.31
#Mann=3,-1,0
  4598.8    0.16       0  5004.5    0.07       0  5010.5    0.16       0
Bank Sta=5004.5,5010.5
Exp/Cntr=0.3,0.1

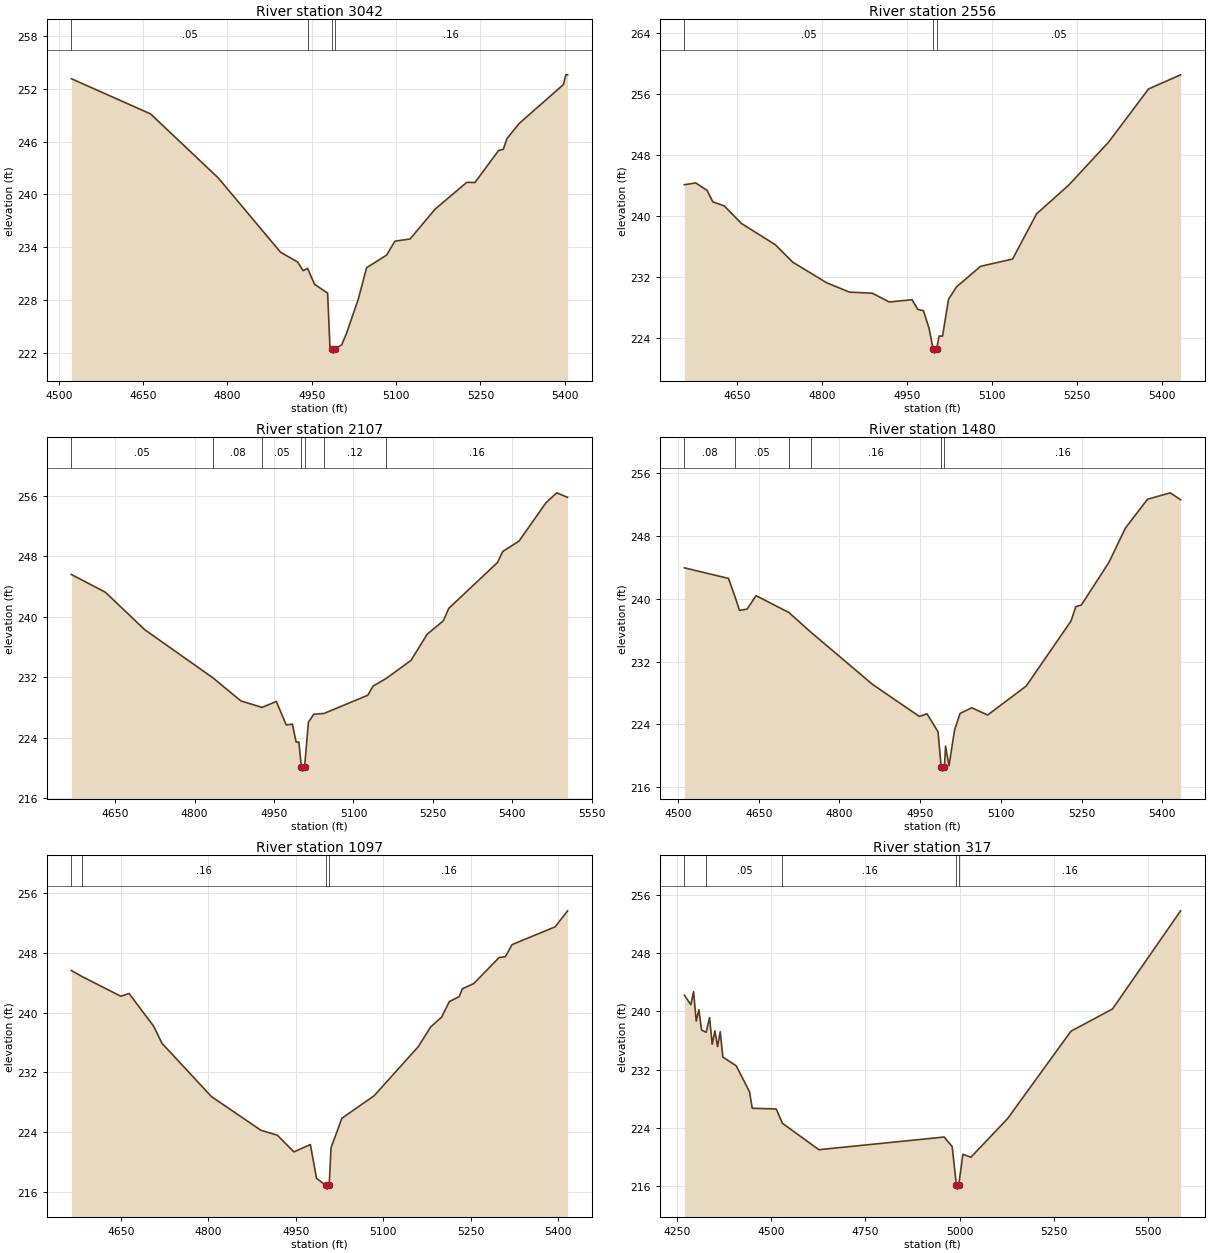
Type RM Length L Ch R = 1,3042,486,486,486
BEGIN DESCRIPTION:
UNT 207 IN UKCR 6.0
END DESCRIPTION:
XS GIS Cut Line= 3
      3717699.61     10493860.20      3717649.61     10493410.19
      3717299.61     10493160.19
#Sta/Elev= 30
  4522.2  253.13  4663.1  249.14  4783.8  241.86  4894.5  233.44  4924.7  232.34
  4934.7  231.35  4942.4  231.62  4954.9  229.81  4978.1  228.81  4982.4  222.57
  4985.5  222.50  4988.2  222.00  4991.5  222.50  5003.2  222.94  5011.8  224.25
  5032.7  228.12  5047.5  231.69  5083.1  233.12  5097.9  234.70  5124.9  234.95
  5169.1  238.32  5225.7  241.37  5240.4  241.36  5282.2  244.98  5290.8  245.12
  5297.0  246.32  5319.1  248.06  5397.7  252.47  5402.0  253.57  5405.1  253.57
#Mann=4,-1,0
  4522.2    0.05       0  4942.4    0.16       0  4985.5    0.07       0
  4991.5    0.16       0
Bank Sta=4985.5,4991.5
Exp/Cntr=0.3,0.1

Type RM Length L Ch R = 1,2556,449,449,449
BEGIN DESCRIPTION:
UNT 207 IN UKCR 5.0
END DESCRIPTION:
XS GIS Cut Line= 3
      3717899.61     10493560.17      3717949.61     10493110.19
      3717649.62     10492810.20
#Sta/Elev= 30
  4556.4  244.10  4576.5  244.34  4596.6  243.36  4606.7  241.85  4626.8  241.33
  4657.0  239.03  4717.4  236.21  4747.6  233.95  4807.9  231.23  4848.2  230.00
  4888.4  229.86  4918.6  228.71  4958.8  229.00  4968.9  227.73  4979.0  227.56
  4989.0  225.21  4996.1  222.49  4998.8  221.99  5002.1  222.49  5006.6  224.23
  5012.7  224.23  5023.3  229.07  5037.4  230.69  5079.9  233.39  5136.4  234.34
  5178.9  240.28  5235.4  244.03  5306.1  249.69  5376.8  256.68  5433.4  258.53
#Mann=3,-1,0
  4556.4    0.05       0  4996.1    0.03       0  5002.1    0.05       0
Bank Sta=4996.1,5002.1
Exp/Cntr=0.3,0.1

Type RM Length L Ch R = 1,2107,627,627,627
BEGIN DESCRIPTION:
UNT 207 IN UKCR 4.0
END DESCRIPTION:
XS GIS Cut Line= 3
      3718499.60     10493510.15      3718349.61     10493110.19
      3718249.60     10492610.16
#Sta/Elev= 30
  4567.3  245.60  4631.3  243.27  4706.1  238.29  4834.6  231.94  4887.7  228.87
  4927.5  228.03  4954.4  228.81  4973.1  225.71  4984.7  225.81  4991.8  223.44
  4997.0  223.44  5001.7  220.10  5004.4  219.60  5007.7  220.10  5014.9  226.05
  5025.1  227.12  5044.5  227.23  5127.0  229.63  5137.2  230.85  5162.4  231.88
  5208.6  234.24  5239.2  237.70  5269.8  239.48  5280.0  241.12  5371.8  247.17
  5382.0  248.65  5412.6  250.01  5463.6  255.09  5484.0  256.40  5504.4  255.80
#Mann=7,-1,0
  4567.3    0.05       0  4834.6    0.08       0  4927.5    0.05       0
  5001.7    0.04       0  5007.7    0.05       0  5044.5    0.12       0
  5162.4    0.16       0
Bank Sta=5001.7,5007.7
Exp/Cntr=0.3,0.1

Type RM Length L Ch R = 1,1480,383,383,383
BEGIN DESCRIPTION:
UNT 207 IN UKCR 3.0
END DESCRIPTION:
XS GIS Cut Line= 3
      3718599.60     10493360.22      3718699.61     10492910.19
      3718799.61     10492460.17
#Sta/Elev= 30
  4511.9  243.95  4593.9  242.60  4606.2  240.22  4614.4  238.52  4628.5  238.69
  4645.1  240.40  4705.9  238.26  4747.4  235.72  4861.5  229.09  4948.6  225.00
  4962.7  225.34  4983.2  223.05  4989.1  218.53  4991.9  218.03  4995.1  218.53
  4997.2  221.22  5003.6  218.71  5013.9  223.27  5024.1  225.38  5045.9  226.11
  5075.3  225.18  5147.1  228.88  5230.3  237.17  5239.2  239.00  5249.5  239.21
  5300.7  244.64  5331.4  249.02  5372.4  252.69  5414.7  253.51  5433.9  252.63
#Mann=6,-1,0
  4511.9    0.08       0  4606.2    0.05       0  4705.9    0.12       0
  4747.4    0.16       0  4989.1    0.07       0  4995.1    0.16       0
Bank Sta=4989.1,4995.1
Exp/Cntr=0.3,0.1

Type RM Length L Ch R = 1,1097,780,780,780
BEGIN DESCRIPTION:
UNT 207 IN UKCR 2.0
END DESCRIPTION:
XS GIS Cut Line= 3
      3719299.62     10493110.20      3718999.61     10492810.19
      3718849.60     10492410.17
#Sta/Elev= 30
  4564.8  245.62  4582.5  244.84  4649.7  242.18  4663.8  242.55  4706.2  238.16
  4720.4  235.89  4805.2  228.78  4890.1  224.28  4918.4  223.62  4946.7  221.39
  4974.9  222.38  4985.5  217.87  5001.2  216.92  5004.0  216.42  5007.2  216.92
  5010.4  221.95  5029.1  225.89  5084.3  228.89  5160.0  235.44  5181.3  238.08
  5200.0  239.38  5213.4  241.47  5230.3  242.13  5235.6  243.17  5255.2  243.87
  5298.8  247.35  5309.5  247.47  5321.1  249.08  5394.9  251.45  5416.3  253.59
#Mann=4,-1,0
  4564.8     0.1       0  4582.5    0.16       0  5001.2    0.07       0
  5007.2    0.16       0
Bank Sta=5001.2,5007.2
Exp/Cntr=0.3,0.1

Type RM Length L Ch R = 1,317,0,0,0
BEGIN DESCRIPTION:
UNT 207 IN UKCR 1.0
END DESCRIPTION:
XS GIS Cut Line= 3
      3720020.82     10492993.44      3719409.74     10492396.25
      3718949.59     10492360.19
#Sta/Elev= 30
  4270.2  242.23  4287.4  240.93  4294.6  242.73  4301.6  238.68  4308.7  240.23
  4315.7  237.45  4328.1  237.14  4337.0  239.16  4344.0  235.49  4351.2  237.33
  4358.2  235.17  4365.3  237.22  4372.3  233.73  4407.8  232.53  4443.0  228.95
  4450.2  226.70  4513.8  226.59  4530.3  224.63  4626.9  221.00  4959.2  222.74
  4980.5  221.43  4991.7  216.08  4994.4  215.58  4997.7  216.08  5008.8  220.38
  5030.0  219.96  5127.2  225.26  5295.3  237.28  5405.6  240.34  5586.2  253.83
#Mann=5,-1,0
  4270.2    0.16       0  4328.1    0.05       0  4530.3    0.16       0
  4991.7    0.07       0  4997.7    0.16       0
Bank Sta=4991.7,4997.7
Exp/Cntr=0.3,0.1

Chan Stop Cuts=-1