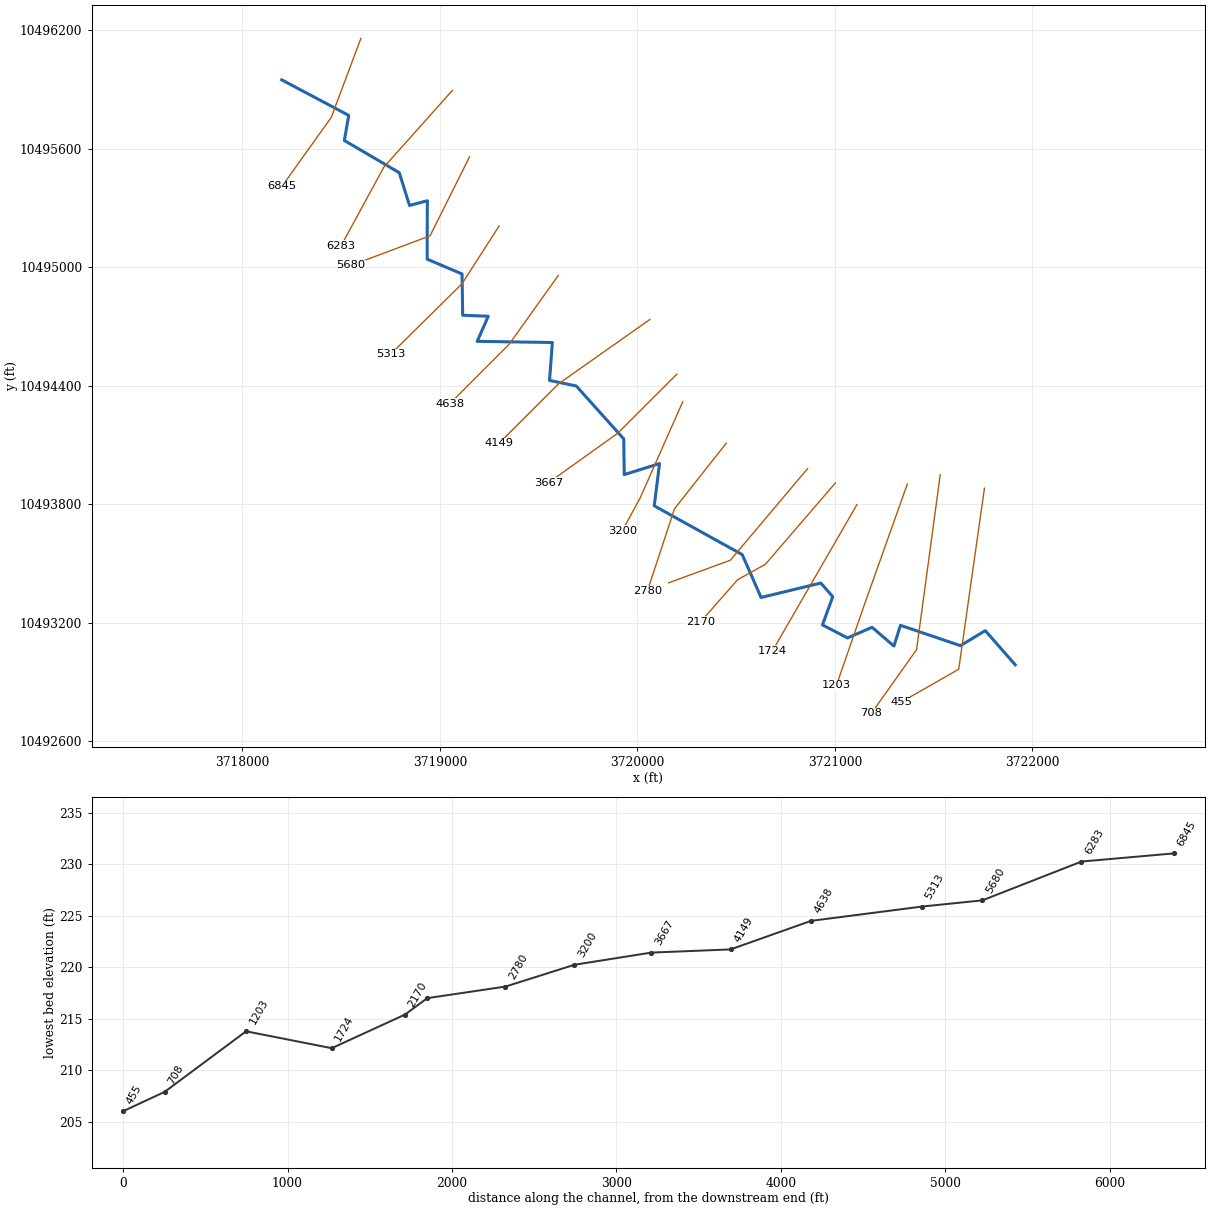
--- UNT 208 IN UKCR.prj (project) ---

Proj Title=UNT 208 IN UKCR Base Level Engineering
Current Plan=p01
Default Exp/Contr=0.3,0.1
English Units
Geom File=g01
Flow File=f01
Plan File=p01
BEGIN DESCRIPTION:
UNT 208 IN UKCR
END DESCRIPTION:

--- UNT 208 IN UKCR.p01 (plan) ---

Plan Title=Multiple Run
Short Identifier=Multiple
Geom File=g01
Flow File=f01
Subcritical Flow
K Sum by GR= 0
Std Step Tol= 0.01
Critical Tol= 0.01
Num of Std Step Trials= 20
Max Error Tol= 0.3
Flow Tol Ratio= 0.001
Split Flow NTrial= 30
Split Flow Tol= 0.02
Split Flow Ratio= 0.02
Log Output Level= 0
Friction Slope Method= 1
Unsteady Friction Slope Method= 2
Unsteady Bridges Friction Slope Method= 1
Parabolic Critical Depth
Global Vel Dist=  1 , 1 , 1
Global Log Level= 0
CheckData=True
Encroach Param= -1, 0, 0, 0
BEGIN DESCRIPTION:
Multiple Run
END DESCRIPTION:

--- UNT 208 IN UKCR.f01 (steady flow) ---

Flow Title=Multiple
Number of Profiles=7
Profile Names=10-year,25-year,50-year,1pct_min,100-year,1pct_plu,500-year
River Rch & RM= UNT 208 IN UKCR,Reach-1,6845
     525     700     841     742    1003    1357    1434
Boundary for River Rch & Prof#=UNT 208 IN UKCR,Reach-1,1
Up Type=0
Dn Type=3
Dn Slope=0.005
Boundary for River Rch & Prof#=UNT 208 IN UKCR,Reach-1,2
Up Type=0
Dn Type=3
Dn Slope=0.005
Boundary for River Rch & Prof#=UNT 208 IN UKCR,Reach-1,3
Up Type=0
Dn Type=3
Dn Slope=0.005
Boundary for River Rch & Prof#=UNT 208 IN UKCR,Reach-1,4
Up Type=0
Dn Type=3
Dn Slope=0.005
Boundary for River Rch & Prof#=UNT 208 IN UKCR,Reach-1,5
Up Type=0
Dn Type=3
Dn Slope=0.005
Boundary for River Rch & Prof#=UNT 208 IN UKCR,Reach-1,6
Up Type=0
Dn Type=3
Dn Slope=0.005
Boundary for River Rch & Prof#=UNT 208 IN UKCR,Reach-1,7
Up Type=0
Dn Type=3
Dn Slope=0.005

--- UNT 208 IN UKCR.g01 (geometry) ---

Geom Title=Existing Conditions

River Reach=UNT 208 IN UKCR,Reach-1
Reach XY= 30
      3718198.50     10495950.00      3718538.00     10495770.00
      3718515.75     10495643.00      3718793.75     10495480.00
      3718845.75     10495314.00      3718936.00     10495338.00
      3718935.00     10495042.00      3719111.75     10494967.00
      3719115.00     10494758.00      3719244.50     10494753.00
      3719188.50     10494626.00      3719569.00     10494620.00
      3719554.75     10494428.00      3719690.00     10494400.00
      3719930.50     10494132.00      3719933.00     10493951.00
      3720111.75     10494007.00      3720085.00     10493793.00
      3720530.50     10493546.00      3720626.00     10493329.00
      3720928.25     10493402.00      3720988.75     10493333.00
      3720936.75     10493190.00      3721063.75     10493124.00
      3721188.00     10493178.00      3721298.50     10493083.00
      3721331.75     10493188.00      3721635.25     10493085.00
      3721761.25     10493161.00      3721913.00     10492988.00

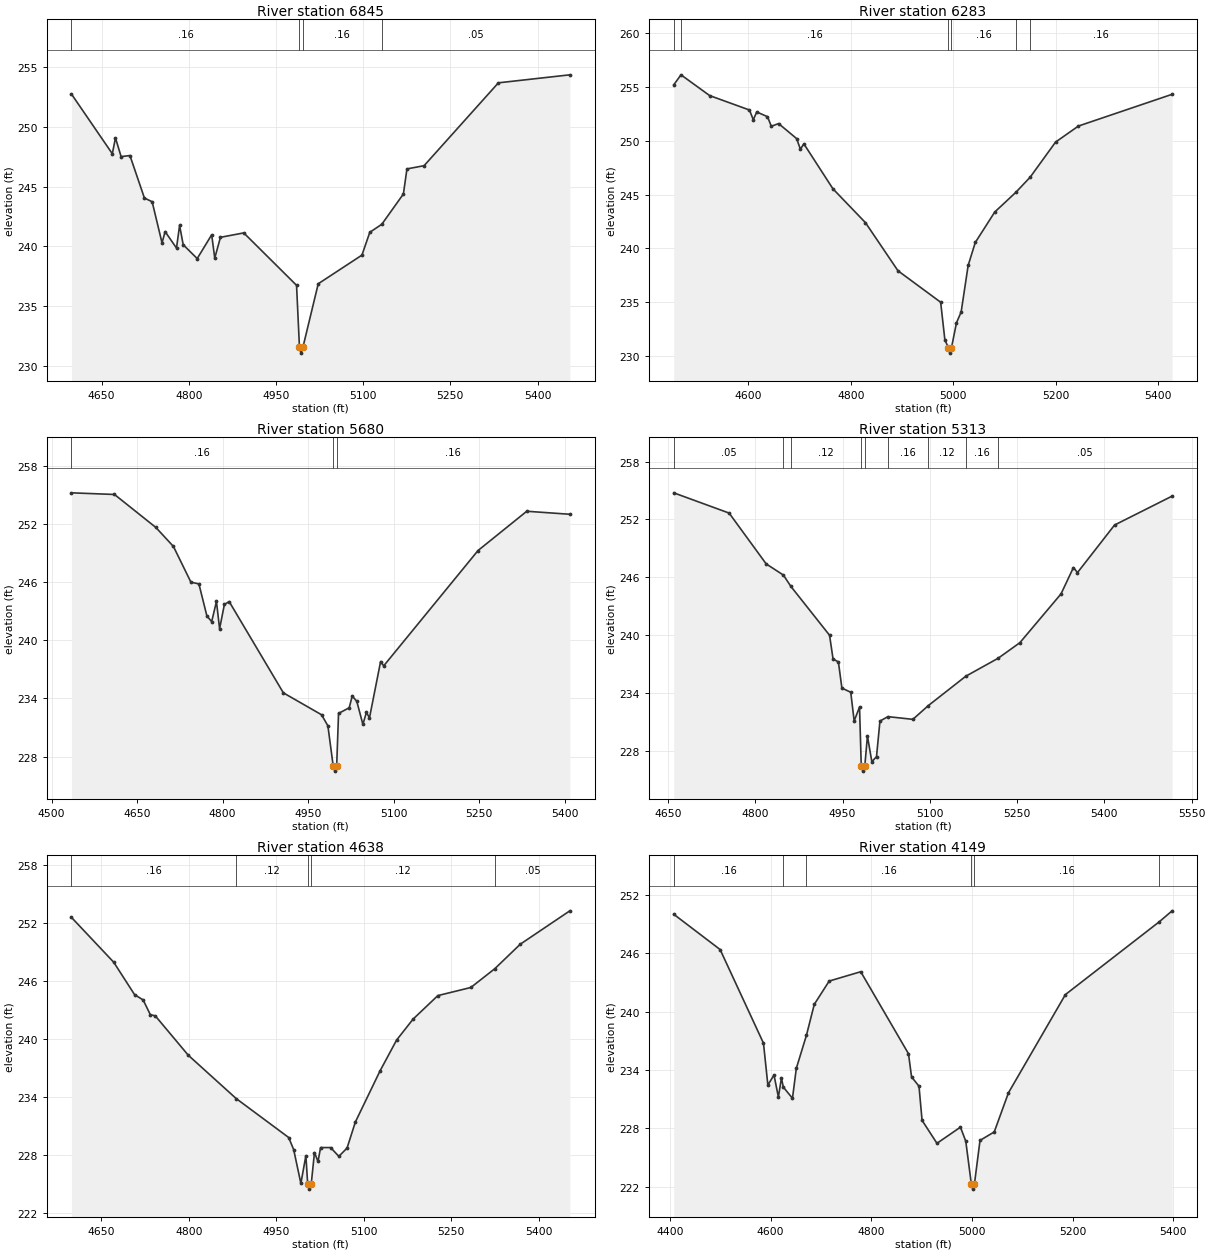
Type RM Length L Ch R = 1,6845,562,562,562
BEGIN DESCRIPTION:
UNT 208 IN UKCR 13.0
END DESCRIPTION:
XS GIS Cut Line= 3
      3718599.61     10496160.20      3718449.61     10495760.19
      3718199.62     10495410.21
#Sta/Elev= 30
  4598.3  252.76  4668.6  247.76  4674.0  249.09  4683.7  247.52  4698.9  247.61
  4723.8  244.05  4737.1  243.74  4754.1  240.29  4759.4  241.24  4779.0  239.86
  4784.3  241.76  4790.5  240.14  4814.6  238.98  4839.5  240.97  4844.8  239.02
  4854.6  240.76  4894.7  241.13  4985.5  236.74  4990.5  231.56  4993.2  231.06
  4996.5  231.56  5022.8  236.87  5098.0  239.27  5111.5  241.18  5132.1  241.85
  5169.3  244.39  5175.4  246.49  5204.9  246.76  5332.7  253.70  5455.6  254.37
#Mann=4,-1,0
  4598.3    0.16       0  4990.5    0.07       0  4996.5    0.16       0
  5132.1    0.05       0
Bank Sta=4990.5,4996.5
Exp/Cntr=0.3,0.1

Type RM Length L Ch R = 1,6283,603,603,603
BEGIN DESCRIPTION:
UNT 208 IN UKCR 12.0
END DESCRIPTION:
XS GIS Cut Line= 3
      3719062.51     10495896.23      3718715.30     10495507.36
      3718499.60     10495110.17
#Sta/Elev= 30
  4454.1  255.20  4468.3  256.13  4524.3  254.20  4602.0  252.86  4609.5  251.95
  4616.2  252.68  4637.2  252.24  4644.7  251.35  4658.9  251.60  4694.0  250.21
  4701.5  249.22  4708.2  249.72  4765.0  245.54  4828.6  242.39  4892.1  237.92
  4975.4  235.00  4983.6  231.51  4990.5  230.77  4993.3  230.27  4996.5  230.77
  5006.3  233.09  5015.4  234.09  5029.1  238.42  5043.0  240.55  5081.0  243.38
  5122.4  245.22  5150.2  246.62  5199.8  249.88  5244.4  251.37  5427.4  254.32
#Mann=6,-1,0
  4454.1    0.05       0  4468.3    0.16       0  4990.5    0.07       0
  4996.5    0.16       0  5122.4    0.05       0  5150.2    0.16       0
Bank Sta=4990.5,4996.5
Exp/Cntr=0.3,0.1

Type RM Length L Ch R = 1,5680,367,367,367
BEGIN DESCRIPTION:
UNT 208 IN UKCR 11.0
END DESCRIPTION:
XS GIS Cut Line= 3
      3719149.61     10495560.19      3718949.61     10495160.19
      3718549.63     10495010.20
#Sta/Elev= 30
  4534.7  255.19  4610.2  255.02  4682.8  251.62  4713.6  249.66  4744.3  245.98
  4758.3  245.80  4772.3  242.50  4780.7  241.91  4789.1  243.99  4794.6  241.17
  4803.0  243.68  4811.4  243.98  4906.5  234.57  4973.5  232.31  4984.6  231.17
  4994.0  227.00  4996.8  226.50  5000.0  227.00  5003.3  232.45  5022.0  233.03
  5027.3  234.24  5035.3  233.70  5046.0  231.32  5052.2  232.55  5057.6  232.00
  5077.1  237.80  5082.5  237.35  5248.0  249.24  5333.5  253.29  5409.1  252.98
#Mann=3,-1,0
  4534.7    0.16       0  4994.0    0.07       0  5000.0    0.16       0
Bank Sta=4994,5000
Exp/Cntr=0.3,0.1

Type RM Length L Ch R = 1,5313,675,675,675
BEGIN DESCRIPTION:
UNT 208 IN UKCR 10.0
END DESCRIPTION:
XS GIS Cut Line= 3
      3719299.63     10495210.22      3719111.13     10494917.08
      3718749.62     10494560.20
#Sta/Elev= 30
  4659.9  254.76  4755.1  252.66  4818.8  247.39  4848.4  246.23  4861.3  245.05
  4927.7  239.99  4933.7  237.53  4942.9  237.22  4948.9  234.51  4964.1  234.08
  4970.0  231.10  4979.2  232.55  4982.2  226.40  4984.9  225.90  4988.2  226.40
  4992.8  229.54  5000.4  226.87  5008.4  227.41  5014.3  231.09  5028.0  231.55
  5070.9  231.27  5097.3  232.69  5161.8  235.74  5217.3  237.60  5254.8  239.22
  5325.5  244.28  5346.8  247.01  5353.8  246.49  5417.5  251.42  5516.4  254.42
#Mann=9,-1,0
  4659.9    0.05       0  4848.4    0.16       0  4861.3    0.12       0
  4982.2    0.07       0  4988.2    0.12       0  5028.0    0.16       0
  5097.3    0.12       0  5161.8    0.16       0  5217.3    0.05       0
Bank Sta=4982.2,4988.2
Exp/Cntr=0.3,0.1

Type RM Length L Ch R = 1,4638,489,489,489
BEGIN DESCRIPTION:
UNT 208 IN UKCR 9.0
END DESCRIPTION:
XS GIS Cut Line= 3
      3719599.61     10494960.19      3719349.61     10494610.19
      3719049.60     10494310.18
#Sta/Elev= 30
  4598.9  252.62  4671.4  247.98  4707.1  244.63  4721.8  244.08  4734.1  242.56
  4742.7  242.43  4799.2  238.36  4881.3  233.88  4971.3  229.85  4979.9  228.59
  4992.2  225.10  5000.8  227.98  5003.9  225.01  5006.7  224.51  5009.9  225.01
  5015.5  228.29  5021.6  227.37  5026.0  228.81  5043.2  228.81  5057.3  227.90
  5071.4  228.76  5085.6  231.45  5128.0  236.75  5156.3  239.93  5184.6  242.10
  5227.0  244.53  5283.6  245.37  5324.8  247.32  5368.4  249.85  5453.3  253.30
#Mann=5,-1,0
  4598.9    0.16       0  4881.3    0.12       0  5003.9    0.07       0
  5009.9    0.12       0  5324.8    0.05       0
Bank Sta=5003.9,5009.9
Exp/Cntr=0.3,0.1

Type RM Length L Ch R = 1,4149,482,482,482
BEGIN DESCRIPTION:
UNT 208 IN UKCR 8.0
END DESCRIPTION:
XS GIS Cut Line= 3
      3720062.50     10494736.51      3719599.61     10494410.19
      3719299.62     10494110.20
#Sta/Elev= 30
  4407.3  250.00  4499.5  246.37  4585.7  236.74  4594.4  232.44  4606.6  233.47
  4615.3  231.21  4621.4  233.16  4625.1  232.23  4643.3  231.08  4651.0  234.16
  4671.0  237.54  4686.7  240.74  4716.3  243.13  4779.0  244.09  4873.9  235.66
  4880.0  233.28  4894.8  232.32  4900.9  228.81  4930.5  226.45  4977.2  228.11
  4987.8  226.66  4998.9  222.24  5001.7  221.74  5004.9  222.24  5016.1  226.75
  5044.4  227.62  5072.6  231.64  5185.8  241.74  5372.3  249.22  5397.9  250.35
#Mann=6,-1,0
  4407.3    0.16       0  4625.1    0.12       0  4671.0    0.16       0
  4998.9    0.07       0  5004.9    0.16       0  5372.3    0.05       0
Bank Sta=4998.9,5004.9
Exp/Cntr=0.3,0.1

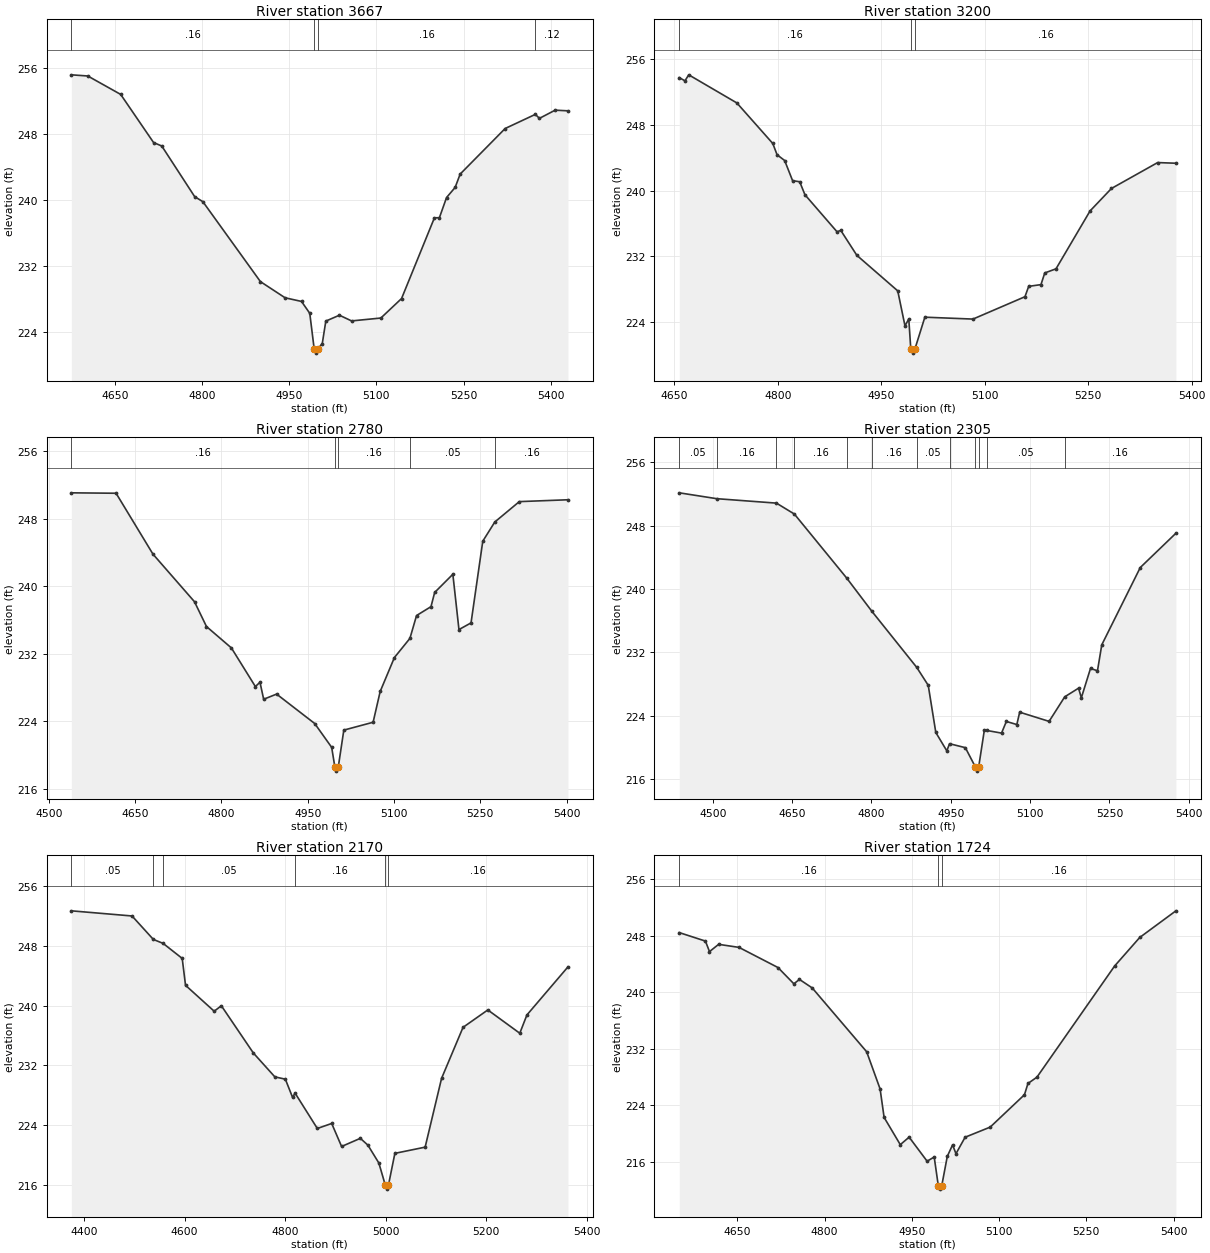
Type RM Length L Ch R = 1,3667,467,467,467
BEGIN DESCRIPTION:
UNT 208 IN UKCR 7.0
END DESCRIPTION:
XS GIS Cut Line= 3
      3720199.58     10494460.16      3719899.61     10494160.19
      3719549.64     10493910.21
#Sta/Elev= 30
  4575.4  255.13  4603.6  254.99  4660.2  252.76  4716.8  246.93  4730.9  246.51
  4787.5  240.38  4801.6  239.77  4900.6  230.09  4943.1  228.13  4971.3  227.69
  4985.5  226.25  4993.1  221.93  4995.8  221.43  4999.1  221.93  5007.0  222.58
  5013.1  225.31  5036.5  226.02  5057.4  225.33  5107.8  225.68  5143.4  228.04
  5199.9  237.81  5208.5  237.83  5220.8  240.27  5235.6  241.50  5244.2  243.11
  5321.6  248.63  5373.5  250.34  5380.6  249.86  5407.6  250.85  5429.7  250.77
#Mann=4,-1,0
  4575.4    0.16       0  4993.1    0.07       0  4999.1    0.16       0
  5373.5    0.12       0
Bank Sta=4993.1,4999.1
Exp/Cntr=0.3,0.1

Type RM Length L Ch R = 1,3200,420,420,420
BEGIN DESCRIPTION:
UNT 208 IN UKCR 6.0
END DESCRIPTION:
XS GIS Cut Line= 3
      3720229.19     10494319.87      3720013.91     10493833.75
      3719924.11     10493667.96
#Sta/Elev= 30
  4657.0  253.75  4665.2  253.36  4670.7  254.09  4740.5  250.67  4792.6  245.74
  4798.8  244.37  4809.8  243.67  4821.3  241.22  4831.6  241.09  4839.2  239.51
  4885.7  235.01  4891.2  235.17  4914.5  232.14  4973.8  227.82  4984.3  223.56
  4989.8  224.41  4992.7  220.75  4995.4  220.25  4998.7  220.75  5013.1  224.62
  5082.9  224.39  5158.3  227.11  5163.7  228.37  5181.5  228.58  5187.0  230.00
  5203.3  230.50  5252.7  237.54  5283.7  240.27  5350.7  243.42  5377.2  243.34
#Mann=3,-1,0
  4657.0    0.16       0  4992.7    0.07       0  4998.7    0.16       0
Bank Sta=4992.7,4998.7
Exp/Cntr=0.3,0.1

Type RM Length L Ch R = 1,2780,475,475,475
BEGIN DESCRIPTION:
UNT 208 IN UKCR 5.0
END DESCRIPTION:
XS GIS Cut Line= 3
      3720449.58     10494110.16      3720187.52     10493778.19
      3720049.61     10493360.19
#Sta/Elev= 30
  4539.2  251.04  4616.9  250.99  4681.0  243.79  4753.2  238.16  4774.0  235.23
  4817.3  232.70  4859.0  228.13  4867.0  228.64  4873.4  226.63  4895.9  227.24
  4962.1  223.76  4991.6  220.94  4997.1  218.63  4999.9  218.13  5003.1  218.63
  5012.7  222.98  5063.6  223.91  5075.9  227.55  5100.6  231.56  5127.6  233.83
  5139.1  236.53  5164.2  237.58  5170.6  239.26  5202.2  241.41  5212.8  234.87
  5233.8  235.66  5254.2  245.32  5275.1  247.59  5317.7  250.00  5402.3  250.22
#Mann=5,-1,0
  4539.2    0.16       0  4997.1    0.07       0  5003.1    0.16       0
  5127.6    0.05       0  5275.1    0.16       0
Bank Sta=4997.1,5003.1
Exp/Cntr=0.3,0.1

Type RM Length L Ch R = 1,2305,135,135,135
BEGIN DESCRIPTION:
UNT 208 IN UKCR 4.0
END DESCRIPTION:
XS GIS Cut Line= 3
      3720861.12     10493981.30      3720470.51     10493517.77
      3720158.01     10493403.19
#Sta/Elev= 30
  4436.6  252.14  4507.5  251.40  4620.3  250.84  4654.2  249.46  4753.0  241.39
  4800.9  237.17  4885.6  230.10  4907.3  227.84  4921.6  221.89  4942.4  219.57
  4947.6  220.47  4977.5  219.97  4996.6  217.51  4999.3  217.01  5002.6  217.51
  5013.4  222.19  5018.2  222.14  5045.9  221.81  5055.0  223.28  5074.8  222.89
  5080.2  224.45  5135.8  223.29  5165.4  226.39  5191.5  227.48  5196.8  226.27
  5214.1  229.97  5227.3  229.68  5235.4  232.95  5308.2  242.71  5375.6  247.04
#Mann=12,-1,0
  4436.6    0.05       0  4507.5    0.16       0  4620.3    0.05       0
  4654.2    0.16       0  4753.0    0.05       0  4800.9    0.16       0
  4885.6    0.05       0  4947.6    0.16       0  4996.6    0.07       0
  5002.6    0.16       0  5018.2    0.05       0  5165.4    0.16       0
Bank Sta=4996.6,5002.6
Exp/Cntr=0.3,0.1

Type RM Length L Ch R = 1,2170,446,446,446
BEGIN DESCRIPTION:
UNT 208 IN UKCR 3.0
END DESCRIPTION:
XS GIS Cut Line= 4
      3721001.79     10493908.43      3720647.59     10493496.94
      3720506.97     10493418.82      3720319.46     10493205.26
#Sta/Elev= 30
  4374.9  252.68  4495.6  251.99  4538.0  248.85  4557.4  248.32  4595.4  246.31
  4602.0  242.71  4659.0  239.24  4673.3  239.97  4736.9  233.65  4779.7  230.45
  4800.6  230.14  4814.9  227.71  4820.0  228.27  4864.2  223.54  4892.8  224.21
  4912.5  221.13  4949.8  222.22  4964.8  221.31  4986.6  218.92  4999.6  215.92
  5002.3  215.42  5005.6  215.92  5018.5  220.21  5078.7  221.04  5111.4  230.25
  5154.1  237.08  5203.4  239.41  5267.0  236.29  5281.2  238.74  5362.9  245.18
#Mann=6,-1,0
  4374.9    0.05       0  4538.0    0.16       0  4557.4    0.05       0
  4820.0    0.16       0  4999.6    0.07       0  5005.6    0.16       0
Bank Sta=4999.6,5005.6
Exp/Cntr=0.3,0.1

Type RM Length L Ch R = 1,1724,521,521,521
BEGIN DESCRIPTION:
UNT 208 IN UKCR 2.0
END DESCRIPTION:
XS GIS Cut Line= 2
      3721111.15     10493799.05      3720684.33     10493059.93
#Sta/Elev= 30
  4550.4  248.43  4595.3  247.23  4602.3  245.74  4618.0  246.77  4653.0  246.34
  4720.0  243.49  4747.3  241.19  4756.9  241.81  4778.9  240.60  4872.4  231.58
  4895.5  226.32  4902.4  222.29  4930.2  218.44  4945.4  219.50  4976.3  216.10
  4988.5  216.69  4995.5  212.65  4998.3  212.15  5001.5  212.65  5011.0  216.79
  5020.1  218.41  5025.9  217.16  5041.6  219.49  5084.7  220.92  5143.6  225.50
  5149.6  227.09  5165.1  227.99  5298.6  243.71  5341.7  247.74  5403.9  251.51
#Mann=3,-1,0
  4550.4    0.16       0  4995.5    0.07       0  5001.5    0.16       0
Bank Sta=4995.5,5001.5
Exp/Cntr=0.3,0.1

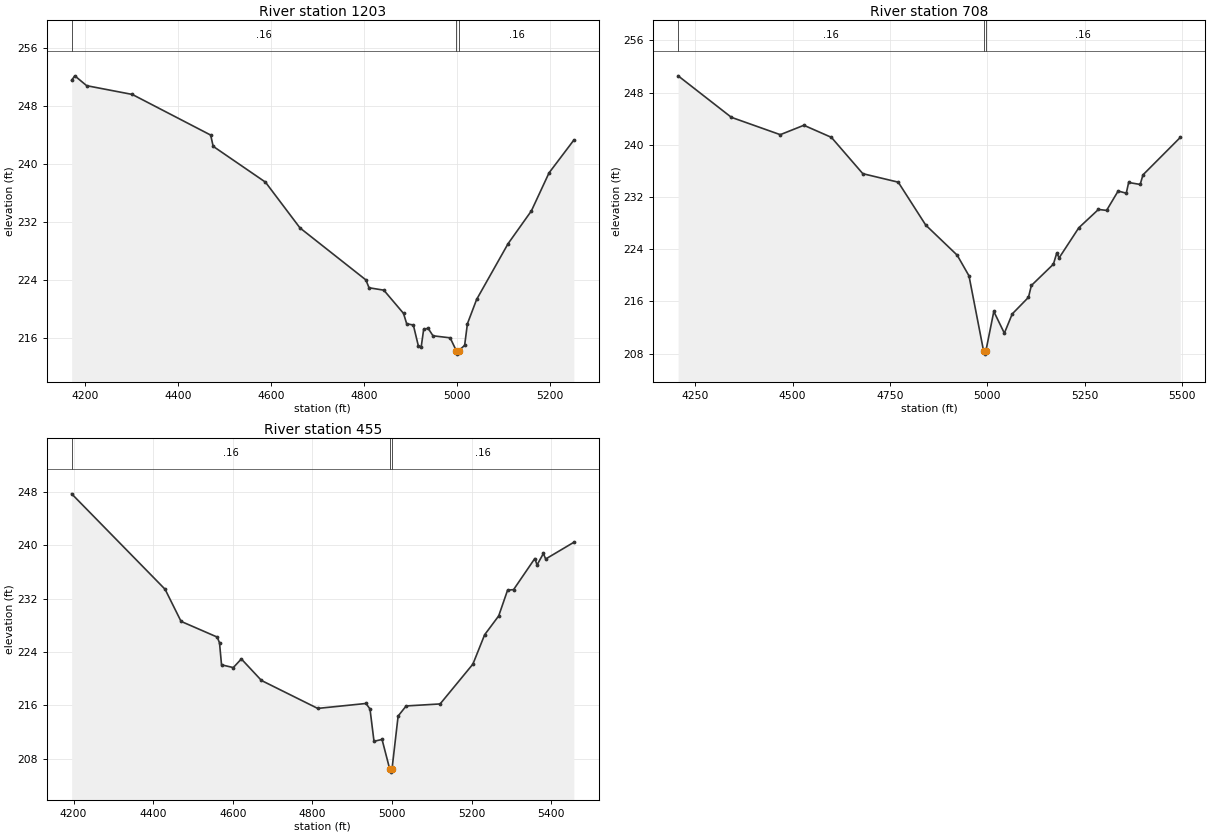
Type RM Length L Ch R = 1,1203,495,495,495
BEGIN DESCRIPTION:
Mapping XS 9d26bd2d
END DESCRIPTION:
XS GIS Cut Line= 3
      3721366.34     10493903.17      3721147.59     10493288.61
      3721007.47     10492883.81
#Sta/Elev= 30
  4170.7  251.61  4177.5  252.21  4203.0  250.85  4301.2  249.64  4469.9  244.03
  4475.2  242.48  4587.8  237.53  4662.1  231.21  4803.8  224.04  4810.7  222.95
  4842.5  222.62  4884.9  219.41  4891.7  217.98  4906.0  217.81  4916.6  214.98
  4922.9  214.77  4928.2  217.20  4937.8  217.36  4948.3  216.32  4985.2  216.04
  4998.3  214.29  5001.0  213.79  5004.3  214.29  5016.4  215.01  5022.4  217.99
  5042.2  221.34  5109.8  229.03  5160.0  233.56  5198.0  238.81  5251.4  243.34
#Mann=3,-1,0
  4170.7    0.16       0  4998.3    0.07       0  5004.3    0.16       0
Bank Sta=4998.3,5004.3
Exp/Cntr=0.3,0.1

Type RM Length L Ch R = 1,708,253,253,253
BEGIN DESCRIPTION:
Mapping XS 55540406
END DESCRIPTION:
XS GIS Cut Line= 3
      3721533.01     10493950.05      3721413.22     10493064.65
      3721184.30     10492742.09
#Sta/Elev= 30
  4206.1  250.57  4342.8  244.21  4468.3  241.55  4528.9  242.99  4599.5  241.14
  4680.2  235.57  4771.1  234.27  4841.7  227.69  4922.4  223.08  4952.7  219.91
  4990.1  208.41  4992.8  207.91  4996.1  208.41  5016.4  214.45  5043.5  211.12
  5063.7  214.07  5105.4  216.62  5112.8  218.43  5169.4  221.70  5178.0  223.41
  5184.1  222.67  5234.6  227.28  5285.0  230.09  5305.9  229.94  5335.5  232.91
  5356.4  232.58  5362.5  234.22  5392.1  233.92  5399.3  235.39  5495.1  241.13
#Mann=3,-1,0
  4206.1    0.16       0  4990.1    0.07       0  4996.1    0.16       0
Bank Sta=4990.1,4996.1
Exp/Cntr=0.3,0.1

Type RM Length L Ch R = 1,455,0,0,0
BEGIN DESCRIPTION:
UNT 208 IN UKCR 1.0
END DESCRIPTION:
XS GIS Cut Line= 3
      3721756.96     10493882.32      3721626.76     10492965.69
      3721335.06     10492799.01
#Sta/Elev= 30
  4195.3  247.66  4430.1  233.38  4470.2  228.58  4561.1  226.23  4566.8  225.37
  4571.9  222.08  4601.5  221.67  4621.7  222.96  4672.2  219.74  4813.6  215.56
  4934.8  216.30  4944.9  215.48  4955.0  210.64  4975.2  210.92  4994.3  206.53
  4997.1  206.03  5000.3  206.53  5015.6  214.42  5035.8  215.93  5121.1  216.23
  5203.5  222.19  5233.0  226.58  5268.3  229.40  5290.6  233.25  5305.7  233.33
  5359.0  237.98  5364.7  237.02  5380.6  238.74  5386.3  237.91  5457.1  240.41
#Mann=3,-1,0
  4195.3    0.16       0  4994.3    0.07       0  5000.3    0.16       0
Bank Sta=4994.3,5000.3
Exp/Cntr=0.3,0.1

Chan Stop Cuts=-1