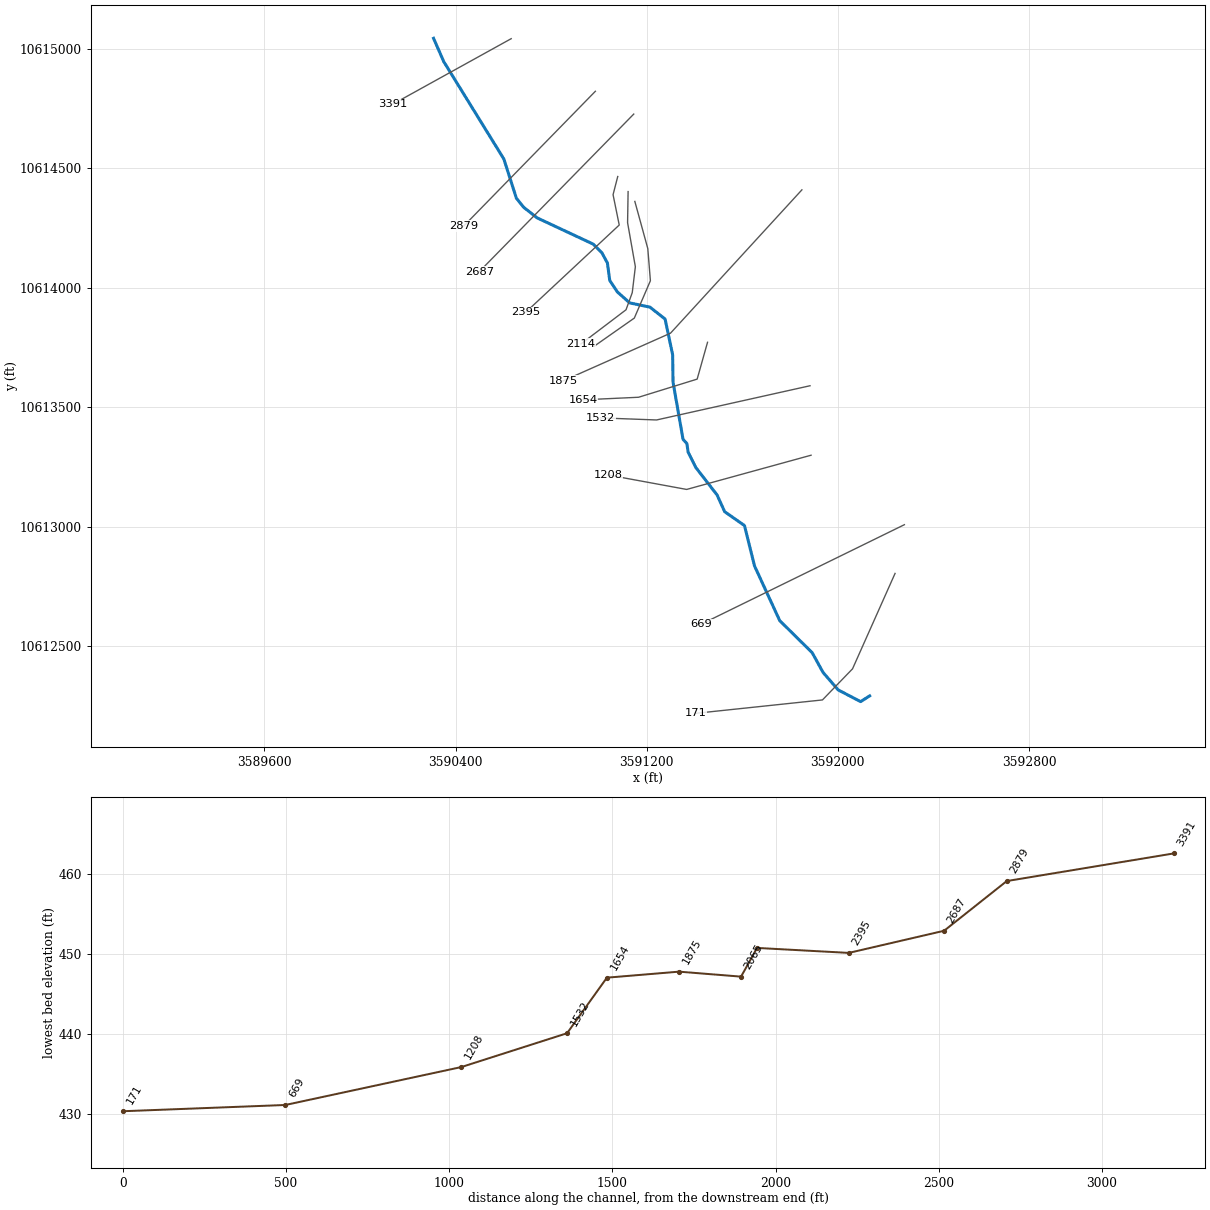
--- UNT 209 IN UKCR.prj (project) ---

Proj Title=UNT 209 IN UKCR Base Level Engineering
Current Plan=p01
Default Exp/Contr=0.3,0.1
English Units
Geom File=g01
Flow File=f01
Plan File=p01
Y Axis Title=Elevation
X Axis Title(PF)=Main Channel Distance
X Axis Title(XS)=Station
BEGIN DESCRIPTION:
UNT 209 IN UKCR
END DESCRIPTION:
DSS Export Rating Curves= 0
DSS Export Rating Curve Sorted= 0
DSS Export Volume Flow Curves= 0
DXF OffsetX= 0
DXF OffsetY= 0
DXF ScaleX= 1
DXF ScaleY= 10

--- UNT 209 IN UKCR.p01 (plan) ---

Plan Title=Multiple Run
Short Identifier=Multiple
Geom File=g01
Flow File=f01
Subcritical Flow
K Sum by GR= 0
Std Step Tol= 0.01
Critical Tol= 0.01
Num of Std Step Trials= 20
Max Error Tol= 0.3
Flow Tol Ratio= 0.001
Split Flow NTrial= 30
Split Flow Tol= 0.02
Split Flow Ratio= 0.02
Log Output Level= 0
Friction Slope Method= 1
Unsteady Friction Slope Method= 2
Unsteady Bridges Friction Slope Method= 1
Parabolic Critical Depth
Global Vel Dist=  1 , 1 , 1
Global Log Level= 0
CheckData=True
Encroach Param= -1, 0, 0, 0
BEGIN DESCRIPTION:
Multiple Run
END DESCRIPTION:

--- UNT 209 IN UKCR.f01 (steady flow) ---

Flow Title=Multiple
Number of Profiles=7
Profile Names=10-year,25-year,50-year,1pct_min,100-year,1pct_plu,500-year
River Rch & RM= UNT 209 IN UKCR,Reach-1,3391
     222     274     311     260     352     476     446
River Rch & RM= UNT 209 IN UKCR,Reach-1,1208
     423     543     635     544     736     995     981
Boundary for River Rch & Prof#=UNT 209 IN UKCR,Reach-1,1
Up Type=0
Dn Type=3
Dn Slope=0.005
Boundary for River Rch & Prof#=UNT 209 IN UKCR,Reach-1,2
Up Type=0
Dn Type=3
Dn Slope=0.005
Boundary for River Rch & Prof#=UNT 209 IN UKCR,Reach-1,3
Up Type=0
Dn Type=3
Dn Slope=0.005
Boundary for River Rch & Prof#=UNT 209 IN UKCR,Reach-1,4
Up Type=0
Dn Type=3
Dn Slope=0.005
Boundary for River Rch & Prof#=UNT 209 IN UKCR,Reach-1,5
Up Type=0
Dn Type=3
Dn Slope=0.005
Boundary for River Rch & Prof#=UNT 209 IN UKCR,Reach-1,6
Up Type=0
Dn Type=3
Dn Slope=0.005
Boundary for River Rch & Prof#=UNT 209 IN UKCR,Reach-1,7
Up Type=0
Dn Type=3
Dn Slope=0.005

--- UNT 209 IN UKCR.g01 (geometry) ---

Geom Title=Existing Conditions
Program Version=4.10

River Reach=UNT 209 IN UKCR ,Reach-1
Reach XY= 30
      3590307.81     10615044.34      3590350.56     10614946.67
      3590602.08     10614539.13       3590654.5       10614375.
      3590685.25       10614337.        3590741.       10614293.
        3590976.       10614183.      3591012.25       10614147.
       3591035.5       10614104.      3591045.25       10614031.
        3591077.       10613983.      3591128.75       10613937.
        3591214.       10613919.        3591277.       10613869.
       3591308.5       10613720.      3591310.25       10613605.
        3591352.       10613366.        3591368.     10613348.31
       3591373.5       10613312.       3591405.5       10613248.
       3591494.5       10613133.      3591526.25       10613063.
      3591609.25       10613005.      3591651.25       10612836.
      3591756.75       10612607.       3591892.5       10612473.
      3591938.25       10612390.       3592001.5       10612317.
      3592095.25       10612268.      3592133.25       10612292.

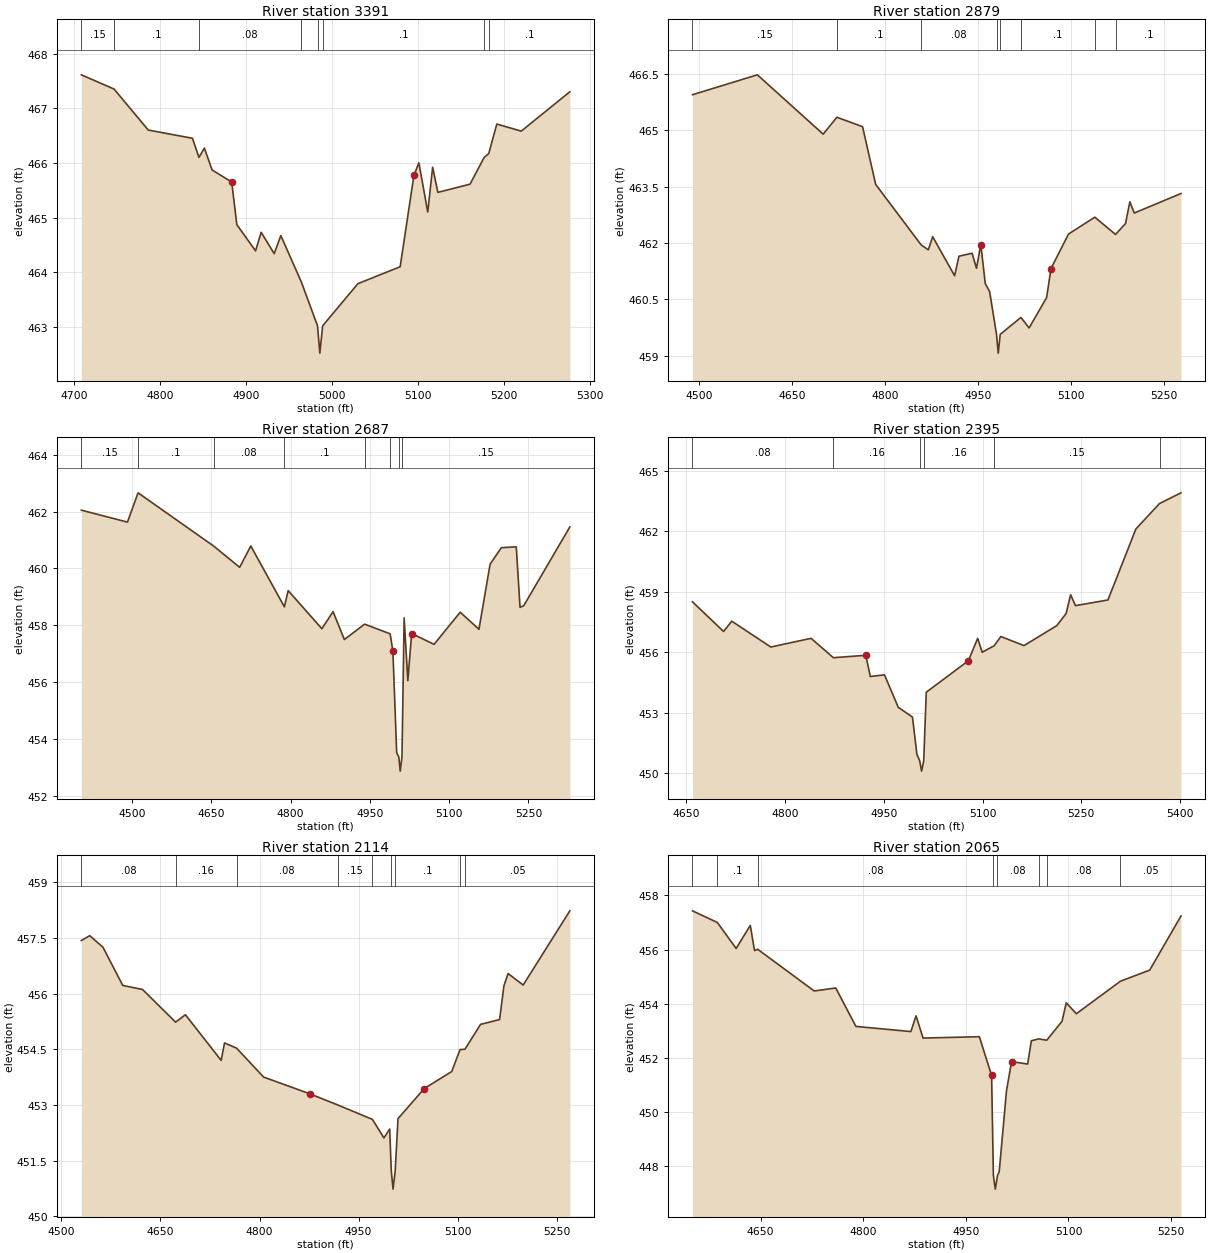
Type RM Length L Ch R = 1 ,3391    ,512,512,512
BEGIN DESCRIPTION:
UNT 209 IN UKCR 7.0
END DESCRIPTION:
XS GIS Cut Line= 2
      3590632.76     10615042.92      3590135.22     10614767.69
#Sta/Elev= 30
  4708.1  467.61  4746.2  467.35    4786   466.6  4837.4  466.45    4845   466.1
  4851.3  466.27  4860.3  465.87  4883.1  465.65  4889.1  464.87  4910.9  464.39
  4917.4  464.73  4932.6  464.34  4940.3  464.67  4964.2  463.82    4983  463.02
  4985.7  462.52    4989  463.02    5030  463.79  5079.2   464.1  5095.2  465.77
    5101     466  5111.3   465.1    5117  465.92  5123.1  465.46  5160.5  465.61
    5177   466.1  5182.3  466.17  5191.7  466.71  5220.1  466.58  5276.7   467.3
#Mann= 8 ,-1 , 0
  4708.1     .15       0  4746.2      .1       0    4845     .08       0
  4964.2      .1       0    4983     .07       0    4989      .1       0
    5177     .15       0  5182.3      .1       0
Bank Sta=4883.1,5095.2
XS Rating Curve= 0 ,0
Exp/Cntr=0.3,0.1

Type RM Length L Ch R = 1 ,2879    ,192,192,192
BEGIN DESCRIPTION:
Mapping XS 9a7324a6
END DESCRIPTION:
XS GIS Cut Line= 2
      3590985.14     10614822.78      3590434.27      10614258.9
#Sta/Elev= 30
  4489.2  465.95  4593.9  466.48  4700.1   464.9  4722.2  465.35  4763.6   465.1
  4784.9  463.56  4858.3  461.95  4869.8  461.82  4876.8  462.17  4912.2  461.13
  4919.2  461.65  4940.4  461.73  4947.5  461.33  4954.5  461.96  4961.7  460.92
  4968.7  460.71  4979.8  459.57  4982.6  459.07  4985.8  459.57  5019.2  460.02
  5032.4  459.74  5060.7  460.55  5067.7  461.32    5096  462.24  5138.4  462.69
  5171.9  462.23    5188  462.52    5195   463.1  5202.1   462.8  5277.5  463.32
#Mann= 8 ,-1 , 0
  4489.2     .15       0  4722.2      .1       0  4858.3     .08       0
  4979.8     .07       0  4985.8     .08       0  5019.2      .1       0
  5138.4     .15       0  5171.9      .1       0
Bank Sta=4954.5,5067.7
XS Rating Curve= 0 ,0
Exp/Cntr=0.3,0.1

Type RM Length L Ch R = 1 ,2687    ,292,292,292
BEGIN DESCRIPTION:
UNT 209 IN UKCR 6.0
END DESCRIPTION:
XS GIS Cut Line= 2
      3591145.76     10614727.33      3590499.01     10614067.56
#Sta/Elev= 30
  4404.4  462.05  4491.6  461.63  4511.7  462.66  4654.5  460.79  4703.8  460.04
  4724.9  460.79  4788.4  458.65  4795.6  459.22  4859.3  457.88  4880.5  458.48
  4901.8   457.5  4940.2  458.04  4988.4   457.7  4993.6   457.1  5000.8  453.52
  5004.8  453.37  5007.5  452.87  5010.8  453.37  5014.9  458.26  5021.9  456.05
  5029.1  457.71  5071.5  457.33  5120.9  458.46  5156.4  457.86  5177.5  460.15
  5198.7  460.73    5227  460.76  5234.1  458.63  5241.1  458.69  5328.3  461.46
#Mann= 8 ,-1 , 0
  4404.4     .15       0  4511.7      .1       0  4654.5     .08       0
  4788.4      .1       0  4940.2     .08       0  4988.4     .15       0
  5004.8     .07       0  5010.8     .15       0
Bank Sta=4993.6,5029.1
XS Rating Curve= 0 ,0
Exp/Cntr=0.3,0.1

Type RM Length L Ch R = 1 ,2395    ,281,281,281
BEGIN DESCRIPTION:
UNT 209 IN UKCR 5.0
END DESCRIPTION:
XS GIS Cut Line= 4
      3591078.73     10614465.92      3591059.19     10614389.92
      3591084.98      10614262.9      3590694.51     10613898.46
#Sta/Elev= 30
  4659.3   458.5  4706.5  457.03    4719  457.54  4778.3  456.26  4839.5  456.69
  4873.4  455.73  4922.6  455.85  4929.5   454.8    4951  454.88    4972  453.27
  4993.5  452.79  5000.3  450.94  5004.6  450.61  5007.4  450.11  5010.6  450.61
  5014.5  454.02  5078.5  455.58  5092.6  456.69  5099.5     456  5117.6  456.32
  5127.8  456.78    5163  456.33  5212.8  457.32    5227  457.92  5233.8  458.85
  5241.2  458.31  5290.5  458.59    5333  462.11  5368.9  463.37  5401.5   463.9
#Mann= 6 ,-1 , 0
  4659.3     .08       0  4873.4     .16       0  5004.6     .07       0
  5010.6     .16       0  5117.6     .15       0  5368.9      .1       0
Bank Sta=4922.6,5078.5
XS Rating Curve= 0 ,0
Exp/Cntr=0.3,0.1

Type RM Length L Ch R = 1 ,2114    ,49,49,49
BEGIN DESCRIPTION:
Mapping XS e13cb177
END DESCRIPTION:
XS GIS Cut Line= 6
      3591122.12      10614402.9      3591119.95     10614272.74
      3591152.51     10614088.27      3591139.49     10613979.77
      3591113.44     10613908.15      3590924.85     10613765.08
#Sta/Elev= 30
  4530.2  457.43  4542.9  457.56  4562.9  457.25  4592.9  456.22  4622.9  456.11
  4672.9  455.23  4687.8  455.43  4741.9   454.2    4747  454.67  4765.2  454.53
  4806.2  453.75    4876   453.3  4918.2     453  4970.9  452.61  4988.4  452.11
  4997.1  452.35  4999.5  451.23  5002.2  450.73  5005.5  451.23  5009.7  452.63
  5049.4  453.44  5091.1   453.9  5103.6  454.49  5111.1   454.5  5134.7  455.17
  5163.5   455.3  5170.1  456.21  5176.4  456.54  5199.2  456.23  5269.9  458.23
#Mann= 9 ,-1 , 0
  4530.2     .08       0  4672.9     .16       0  4765.2     .08       0
  4918.2     .15       0  4970.9      .1       0  4999.5     .07       0
  5005.5      .1       0  5103.6     .08       0  5111.1     .05       0
Bank Sta=4876,5049.4
XS Rating Curve= 0 ,0
Exp/Cntr=0.3,0.1

Type RM Length L Ch R = 1 ,2065    ,190,190,190
BEGIN DESCRIPTION:
Mapping XS 666e32af
END DESCRIPTION:
XS GIS Cut Line= 5
      3591150.34     10614361.69      3591204.59     10614164.23
      3591215.44     10614029.68      3591148.17     10613873.43
      3590981.04     10613756.23
#Sta/Elev= 30
  4550.5  457.43  4586.8     457  4614.3  456.04    4635  456.89  4641.2  455.96
  4645.8  456.01  4728.4  454.47  4759.9  454.58  4789.4  453.16  4869.7  452.97
  4877.3  453.55  4887.5  452.73  4969.8  452.78  4987.7  451.35  4990.3  447.65
  4993.1  447.15  4996.3  447.65  4998.8  447.79  5009.5  450.79  5016.9  451.86
  5040.4  451.77  5045.8  452.63  5056.6   452.7  5068.3  452.65  5090.6  453.35
  5096.8  454.03  5111.6  453.63    5176  454.83  5218.8  455.24  5264.5  457.24
#Mann= 8 ,-1 , 0
  4550.5     .08       0  4586.8      .1       0  4645.8     .08       0
  4990.3     .07       0  4996.3     .08       0  5056.6      .1       0
  5068.3     .08       0    5176     .05       0
Bank Sta=4987.7,5016.9
XS Rating Curve= 0 ,0
Exp/Cntr=0.3,0.1

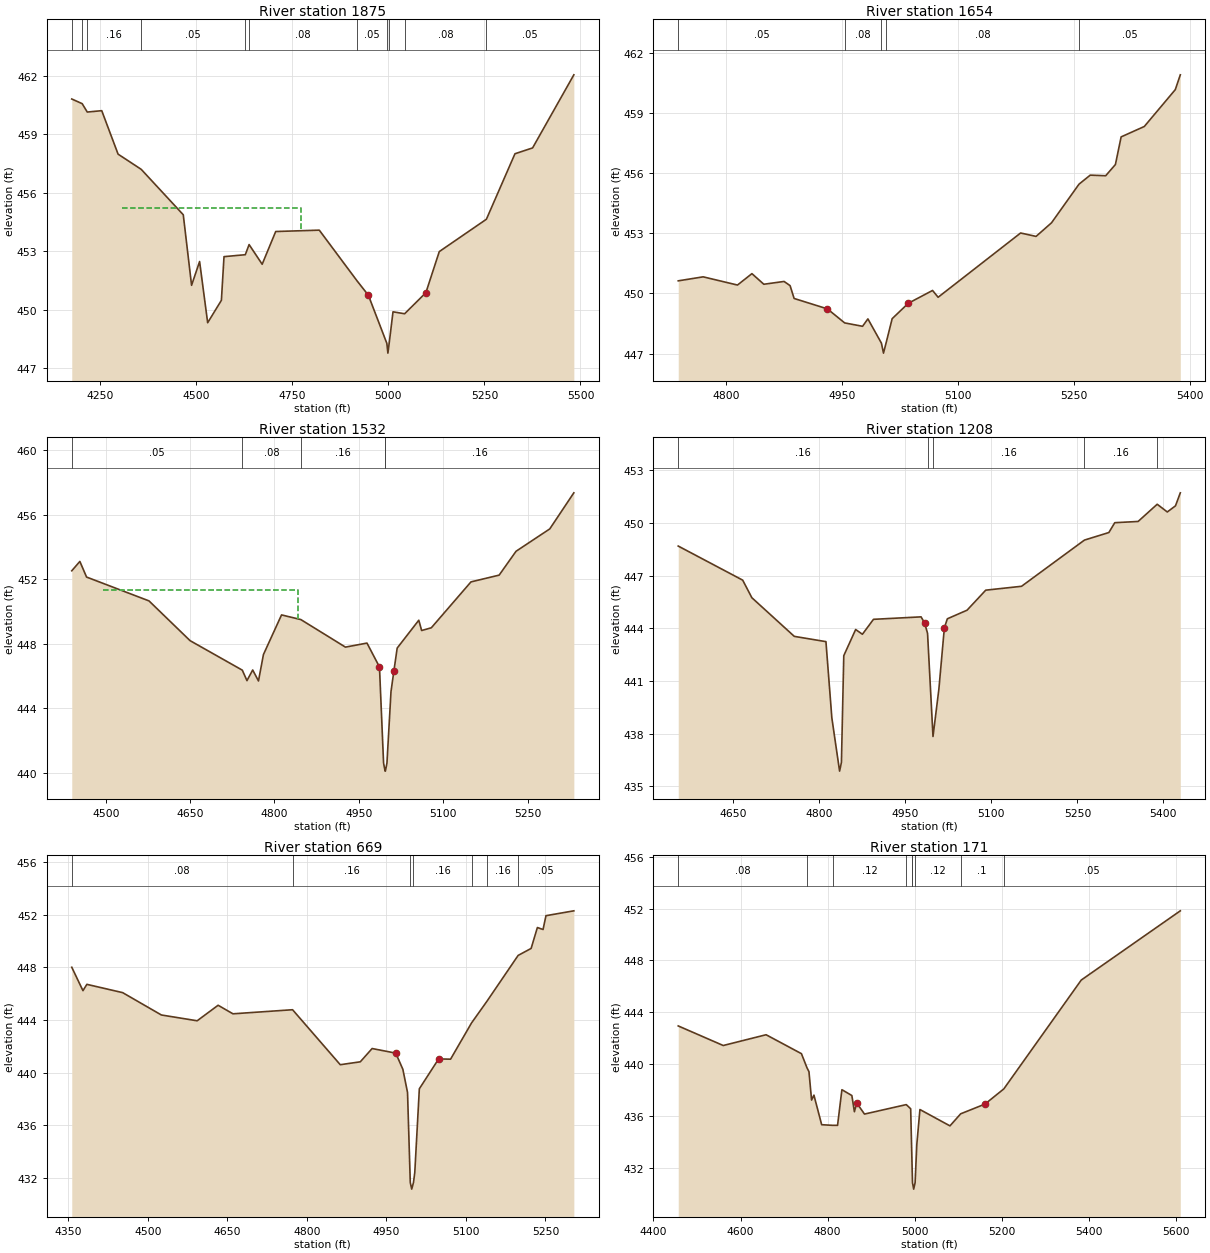
Type RM Length L Ch R = 1 ,1875    ,221,221,221
BEGIN DESCRIPTION:
UNT 209 IN UKCR 4.0
END DESCRIPTION:
XS GIS Cut Line= 3
      3591849.58     10614410.15      3591299.61     10613810.19
      3590849.64      10613610.2
#Sta/Elev= 30
  4176.4  460.81  4203.5  460.57  4216.7  460.14  4254.4  460.21  4296.9  457.98
  4357.1   457.2  4466.5  454.87  4488.1  451.25    4509  452.47    4530  449.33
  4565.7  450.48  4572.5  452.72  4627.9  452.82  4637.8  453.34  4671.8  452.33
    4707  454.01  4820.4  454.08  4918.6  451.48  4948.1  450.74  4996.2  448.27
  4998.9  447.77  5002.2  448.27  5012.2  449.89  5042.4  449.79  5097.7  450.87
  5132.6  452.98  5255.2  454.64  5329.5     458  5375.4   458.3  5482.7  462.05
#Mann= 11 ,-1 , 0
  4176.4     .08       0  4203.5     .05       0  4216.7     .16       0
  4357.1     .05       0  4627.9     .16       0  4637.8     .08       0
  4918.6     .05       0  4996.2     .04       0  5002.2     .05       0
  5042.4     .08       0  5255.2     .05       0
#XS Ineff= 1 ,-1
 4306.36 4771.82  455.21
Permanent Ineff=
       F
Bank Sta=4948.1,5097.7
XS Rating Curve= 0 ,0
Exp/Cntr=0.3,0.1

Type RM Length L Ch R = 1 ,1654    ,122,122,122
BEGIN DESCRIPTION:
Mapping XS 084d1f16
END DESCRIPTION:
XS GIS Cut Line= 4
      3591454.58     10613772.02      3591411.18     10613617.93
      3591165.95     10613541.98       3590933.1      10613531.2
#Sta/Elev= 30
  4737.7  450.63    4770  450.83  4814.4  450.42  4833.1  450.99  4848.5  450.46
  4874.7   450.6  4882.5  450.39  4887.7  449.75  4930.8  449.23  4953.1  448.53
  4976.3  448.36  4983.2  448.73  5000.7  447.52  5003.4  447.02  5006.7  447.52
  5014.6  448.74  5035.5  449.51  5066.9  450.15  5074.1  449.81  5180.9  453.02
  5200.9  452.85  5220.9  453.53  5256.5  455.46    5271  455.91    5291  455.88
  5303.6  456.44    5311  457.82    5341  458.34  5381.1  460.18  5387.6  460.92
#Mann= 5 ,-1 , 0
  4737.7     .05       0  4953.1     .08       0  5000.7     .07       0
  5006.7     .08       0  5256.5     .05       0
Bank Sta=4930.8,5035.5
XS Rating Curve= 0 ,0
Exp/Cntr=0.3,0.1

Type RM Length L Ch R = 1 ,1532    ,324,324,324
BEGIN DESCRIPTION:
UNT 209 IN UKCR 3.0
END DESCRIPTION:
XS GIS Cut Line= 3
      3591883.63     10613590.17      3591241.23     10613446.93
      3591006.86     10613455.61
#Sta/Elev= 30
  4439.6  452.53    4454  453.11  4465.9  452.14  4576.9  450.66    4650  448.19
  4742.8  446.36  4751.1  445.71  4761.3  446.37  4771.6  445.69  4780.4  447.33
  4812.6  449.79  4846.9   449.5  4926.2  447.79  4964.5  448.04  4986.7  446.56
    4994  440.59  4996.7  440.09  4997.2  440.09    5000  440.59  5007.2  445.03
  5012.3   446.3  5018.2  447.73  5056.6  449.46  5061.7  448.82  5078.9  448.99
  5149.4  451.84  5199.5  452.26  5229.5  453.74  5289.5  455.13  5332.3  457.37
#Mann= 5 ,-1 , 0
  4439.6     .05       0  4742.8     .08       0  4846.9     .16       0
  4996.7     .07       0  4997.2     .16       0
#XS Ineff= 1 ,-1
 4494.89 4841.48  451.33
Permanent Ineff=
       F
Bank Sta=4986.7,5012.3
XS Rating Curve= 0 ,0
Exp/Cntr=0.3,0.1

Type RM Length L Ch R = 1 ,1208    ,539,539,539
BEGIN DESCRIPTION:
UNT 209 IN UKCR 2.0
END DESCRIPTION:
XS GIS Cut Line= 3
      3591887.96     10613299.37       3591367.1     10613156.13
      3591037.25     10613216.89
#Sta/Elev= 30
  4553.9  448.68  4666.3  446.74  4682.3  445.74  4756.3  443.54  4811.5  443.24
  4821.8   438.9  4835.3  435.87  4838.5  436.37  4842.6  442.44  4863.3  443.93
  4875.1  443.66  4894.4  444.51  4977.4  444.65  4983.6   444.3  4988.7  443.71
  4998.2  437.84  5008.5  440.55    5018  444.02  5023.2  444.54  5057.6  445.03
  5090.2  446.17  5152.6  446.39  5262.3  449.02  5304.9  449.45  5315.2  450.01
  5355.9  450.08  5389.2  451.06  5406.8  450.62  5421.1  450.97  5429.5  451.71
#Mann= 5 ,-1 , 0
  4553.9     .16       0  4988.7     .07       0  4998.2     .16       0
  5262.3     .16       0  5389.2     .05       0
Bank Sta=4983.6,5018
XS Rating Curve= 0 ,0
Exp/Cntr=0.3,0.1

Type RM Length L Ch R = 1 ,669     ,498,498,498
BEGIN DESCRIPTION:
Mapping XS 27e5efb5
END DESCRIPTION:
XS GIS Cut Line= 2
      3592278.55     10613008.56      3591427.82     10612591.87
#Sta/Elev= 30
  4356.3  448.01  4377.4  446.23  4384.8  446.71  4452.3  446.08  4525.4  444.38
  4592.9  443.94  4632.4  445.12  4660.4  444.47  4772.9  444.78  4862.9   440.6
  4900.7  440.82    4923  441.83  4967.6  441.48    4981  440.25  4989.8  438.49
    4995  431.64  4997.7  431.14    5001  431.64  5003.5  432.41  5012.1  438.77
  5048.5  441.04    5071  441.02  5110.5  443.77  5139.4  445.41  5198.5  448.91
    5223  449.44  5234.8  451.03  5245.5  450.88    5251  451.93  5303.6   452.3
#Mann= 7 ,-1 , 0
  4356.3     .08       0  4772.9     .16       0    4995     .07       0
    5001     .16       0  5110.5     .05       0  5139.4     .16       0
  5198.5     .05       0
Bank Sta=4967.6,5048.5
XS Rating Curve= 0 ,0
Exp/Cntr=0.3,0.1

Type RM Length L Ch R = 1 ,171     ,0,0,0
BEGIN DESCRIPTION:
UNT 209 IN UKCR 1.0
END DESCRIPTION:
XS GIS Cut Line= 4
      3592239.51      10612804.6      3592061.54     10612405.26
      3591935.67     10612275.05      3591403.24     10612218.78
#Sta/Elev= 30
  4456.9  442.95  4560.3  441.44  4658.8  442.27    4740  440.81  4752.9  439.71
  4757.3  439.42  4763.3  437.23  4768.7  437.61  4786.5  435.33  4812.4  435.28
    4823  435.28    4833  438.03  4855.9  437.58  4861.7  436.33  4867.1     437
  4884.9  436.15  4980.9  436.88    4991  436.56  4994.5  431.81  4995.2  430.86
  4997.9  430.36  5001.2  430.86  5005.1   433.8  5012.3   436.5  5081.3  435.24
  5105.9  436.17  5161.7  436.92    5205  438.09    5383  446.49  5610.6  451.83
#Mann= 9 ,-1 , 0
  4456.9     .08       0  4752.9     .05       0  4812.4     .12       0
  4980.9     .16       0  4994.5     .12       0  4995.2     .07       0
  5001.2     .12       0  5105.9      .1       0    5205     .05       0
Bank Sta=4867.1,5161.7
XS Rating Curve= 0 ,0
Exp/Cntr=0.3,0.1

Chan Stop Cuts=-1
Use User Specified Reach Order=0
Composite Channel Slope=5