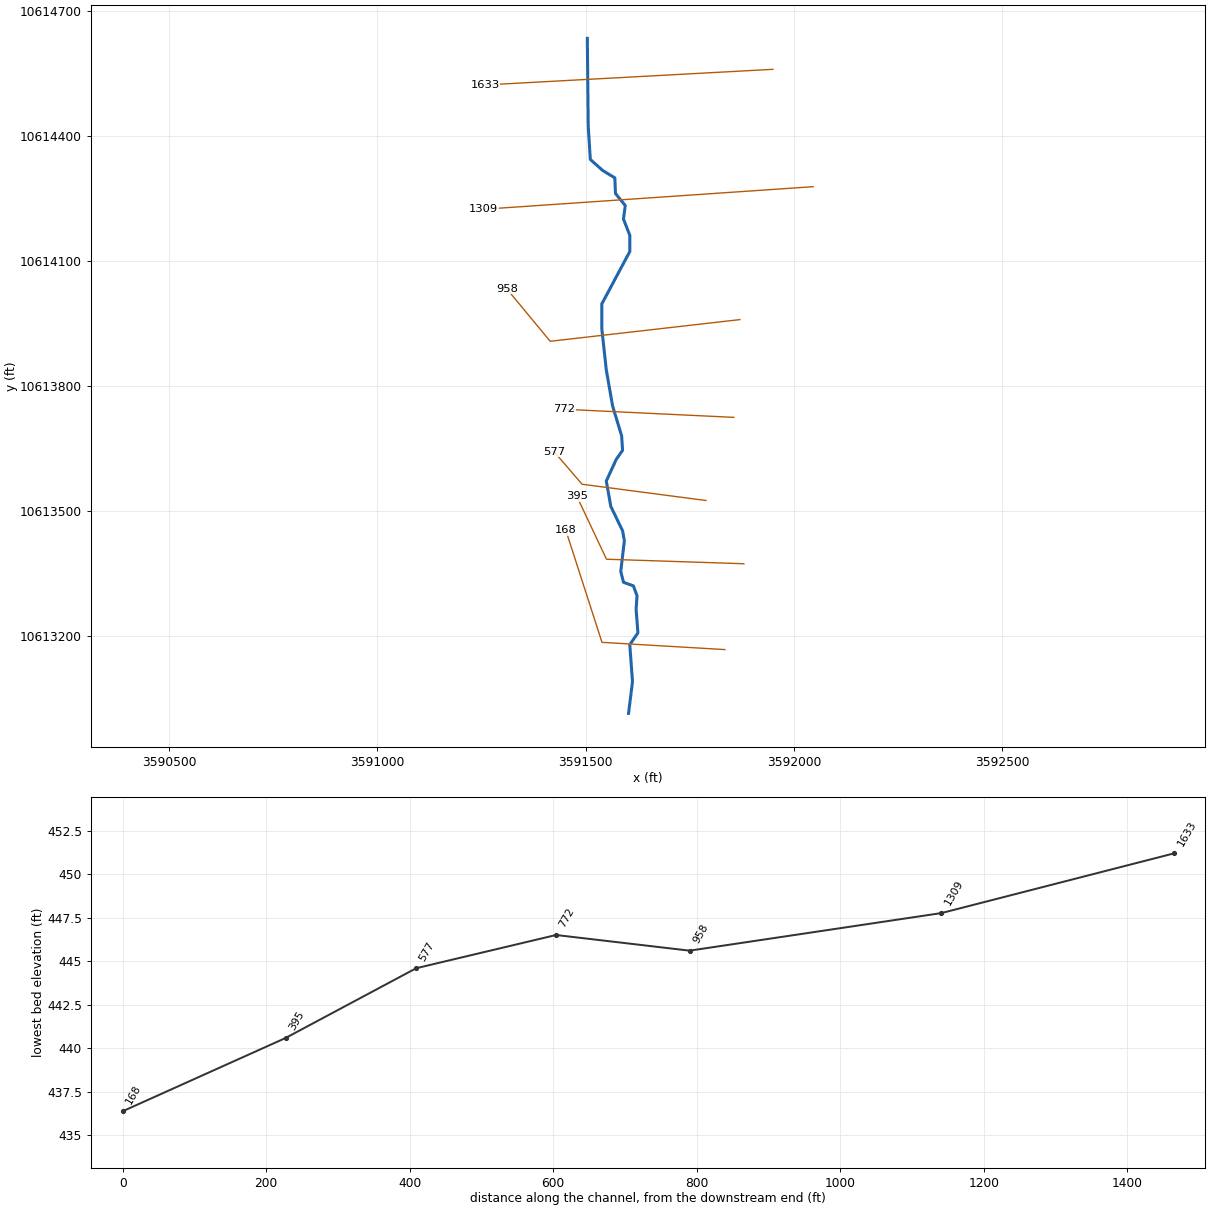
--- UNT 210 IN UKCR.prj (project) ---

Proj Title=UNT 210 IN UKCR Base Level Engineering
Current Plan=p01
Default Exp/Contr=0.3,0.1
English Units
Geom File=g01
Flow File=f01
Plan File=p01
BEGIN DESCRIPTION:
UNT 210 IN UKCR
END DESCRIPTION:

--- UNT 210 IN UKCR.p01 (plan) ---

Plan Title=Multiple Run
Short Identifier=Multiple
Geom File=g01
Flow File=f01
Subcritical Flow
K Sum by GR= 0
Std Step Tol= 0.01
Critical Tol= 0.01
Num of Std Step Trials= 20
Max Error Tol= 0.3
Flow Tol Ratio= 0.001
Split Flow NTrial= 30
Split Flow Tol= 0.02
Split Flow Ratio= 0.02
Log Output Level= 0
Friction Slope Method= 1
Unsteady Friction Slope Method= 2
Unsteady Bridges Friction Slope Method= 1
Parabolic Critical Depth
Global Vel Dist=  1 , 1 , 1
Global Log Level= 0
CheckData=True
Encroach Param= -1, 0, 0, 0
BEGIN DESCRIPTION:
Multiple Run
END DESCRIPTION:

--- UNT 210 IN UKCR.f01 (steady flow) ---

Flow Title=Multiple
Number of Profiles=7
Profile Names=10-year,25-year,50-year,1pct_min,100-year,1pct_plu,500-year
River Rch & RM= UNT 210 IN UKCR,Reach-1,1633
     175     211     236     194     262     355     322
Boundary for River Rch & Prof#=UNT 210 IN UKCR,Reach-1,1
Up Type=0
Dn Type=3
Dn Slope=0.005
Boundary for River Rch & Prof#=UNT 210 IN UKCR,Reach-1,2
Up Type=0
Dn Type=3
Dn Slope=0.005
Boundary for River Rch & Prof#=UNT 210 IN UKCR,Reach-1,3
Up Type=0
Dn Type=3
Dn Slope=0.005
Boundary for River Rch & Prof#=UNT 210 IN UKCR,Reach-1,4
Up Type=0
Dn Type=3
Dn Slope=0.005
Boundary for River Rch & Prof#=UNT 210 IN UKCR,Reach-1,5
Up Type=0
Dn Type=3
Dn Slope=0.005
Boundary for River Rch & Prof#=UNT 210 IN UKCR,Reach-1,6
Up Type=0
Dn Type=3
Dn Slope=0.005
Boundary for River Rch & Prof#=UNT 210 IN UKCR,Reach-1,7
Up Type=0
Dn Type=3
Dn Slope=0.005

--- UNT 210 IN UKCR.g01 (geometry) ---

Geom Title=Existing Conditions

River Reach=UNT 210 IN UKCR,Reach-1
Reach XY= 30
      3591503.99     10614634.62      3591506.16     10614424.11
      3591511.20     10614343.72      3591540.63     10614317.46
      3591570.05     10614299.45      3591571.61     10614261.95
      3591595.14     10614233.14      3591590.80     10614200.59
      3591605.99     10614161.53      3591605.99     10614122.46
      3591538.71     10613996.59      3591538.71     10613938.00
      3591549.57     10613838.17      3591564.76     10613751.37
      3591586.46     10613679.75      3591588.63     10613645.03
      3591573.44     10613623.33      3591549.57     10613571.25
      3591560.42     10613510.48      3591588.63     10613451.89
      3591592.97     10613428.02      3591584.29     10613354.23
      3591590.80     10613328.19      3591614.67     10613319.51
      3591623.35     10613295.64      3591621.18     10613263.09
      3591625.52     10613206.66      3591605.99     10613178.45
      3591612.50     10613089.48      3591603.03     10613013.33

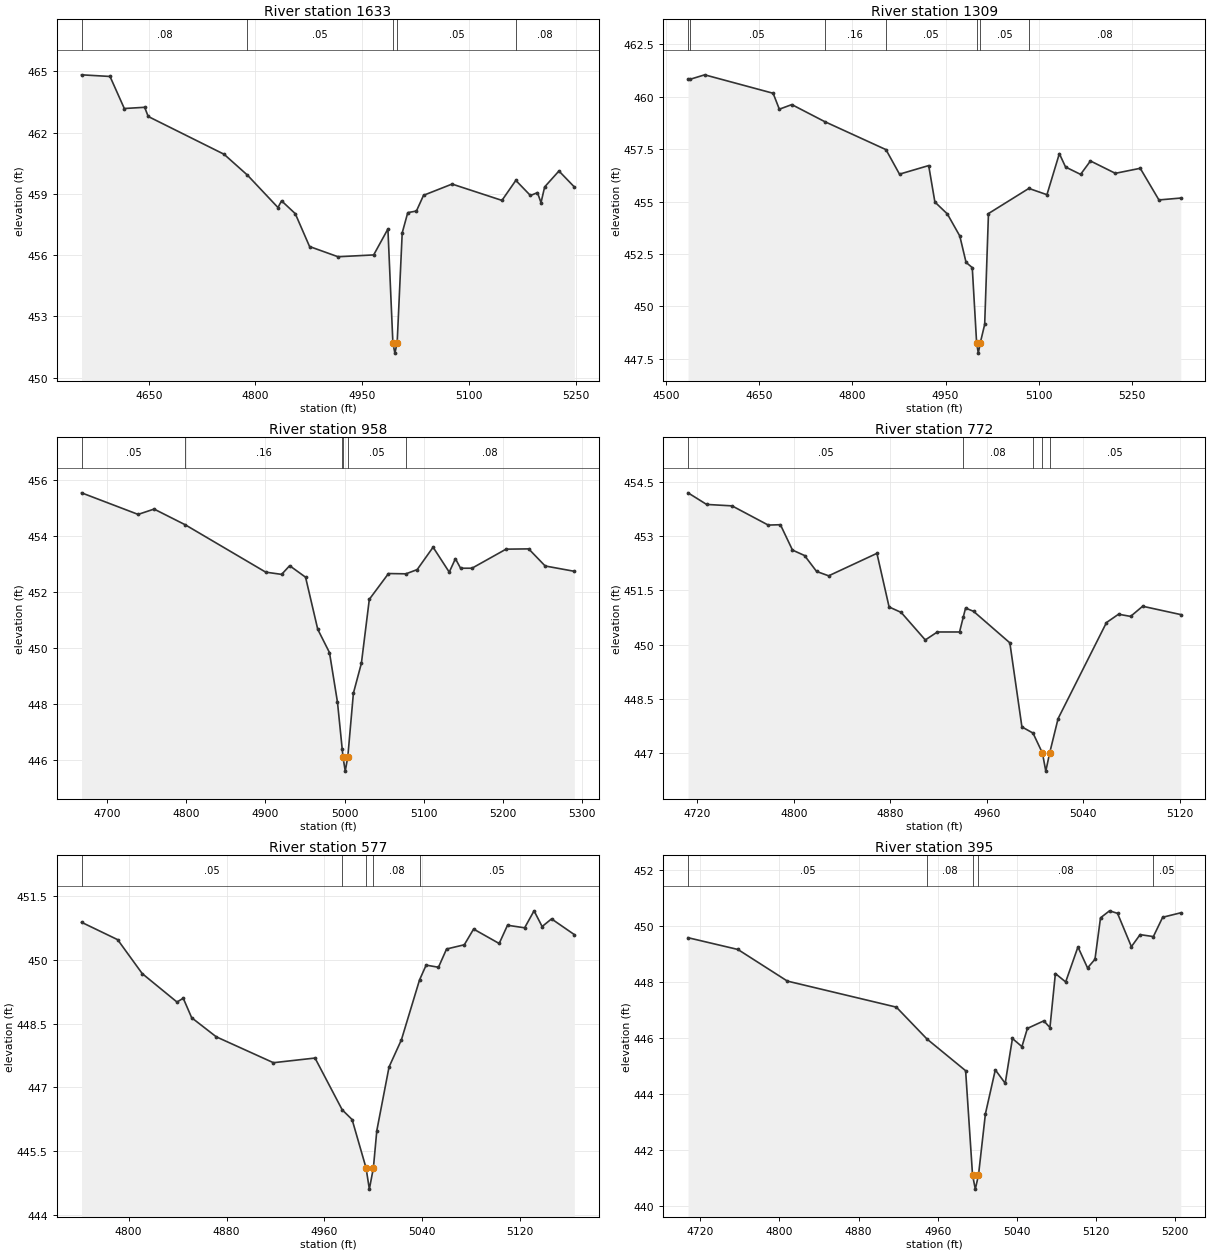
Type RM Length L Ch R = 1,1633,324,324,324
BEGIN DESCRIPTION:
UNT 210 IN UKCR 3.0
END DESCRIPTION:
XS GIS Cut Line= 2
      3591949.60     10614560.19      3591258.02     10614522.65
#Sta/Elev= 30
  4555.6  464.83  4595.6  464.75  4615.7  463.18  4644.3  463.24  4649.3  462.79
  4755.9  460.94  4788.7  459.92  4831.7  458.33  4836.7  458.66  4856.0  458.03
  4876.1  456.42  4916.1  455.92  4966.2  456.01  4986.2  457.28  4993.2  451.70
  4996.0  451.20  4999.2  451.70  5006.3  457.09  5014.1  458.08  5026.3  458.16
  5036.3  458.93  5076.4  459.48  5146.5  458.68  5166.0  459.66  5186.5  458.92
  5196.4  459.06  5201.4  458.57  5206.5  459.34  5226.6  460.12  5248.2  459.34
#Mann=5,-1,0
  4555.6    0.08       0  4788.7    0.05       0  4993.2    0.04       0
  4999.2    0.05       0  5166.0    0.08       0
Bank Sta=4993.2,4999.2
Exp/Cntr=0.3,0.1

Type RM Length L Ch R = 1,1309,351,351,351
BEGIN DESCRIPTION:
Mapping XS c26455fc
END DESCRIPTION:
XS GIS Cut Line= 2
      3592046.41     10614278.34      3591254.47     10614224.09
#Sta/Elev= 30
  4535.1  460.83  4537.6  460.83  4562.0  461.05  4672.2  460.17  4682.2  459.41
  4702.3  459.63  4755.1  458.82  4854.0  457.48  4875.8  456.31  4922.8  456.72
  4932.8  454.98  4952.9  454.41  4972.9  453.36  4983.0  452.10  4993.0  451.85
  5000.0  448.27  5002.7  447.77  5006.0  448.27  5013.0  449.14  5019.1  454.43
  5084.2  455.63  5113.3  455.33  5133.3  457.29  5143.3  456.65  5167.5  456.30
  5183.4  456.94  5223.5  456.35  5263.6  456.59  5293.7  455.08  5328.9  455.17
#Mann=7,-1,0
  4535.1    0.08       0  4537.6    0.05       0  4755.1    0.16       0
  4854.0    0.05       0  5000.0    0.04       0  5006.0    0.05       0
  5084.2    0.08       0
Bank Sta=5000,5006
Exp/Cntr=0.3,0.1

Type RM Length L Ch R = 1,958,186,186,186
BEGIN DESCRIPTION:
UNT 210 IN UKCR 2.0
END DESCRIPTION:
XS GIS Cut Line= 3
      3591870.58     10613959.08      3591414.84     10613907.00
      3591310.66     10614032.88
#Sta/Elev= 30
  4667.8  455.54  4739.2  454.77  4759.4  454.96  4798.7  454.40  4900.3  452.71
  4920.4  452.63  4930.5  452.94  4950.6  452.53  4966.0  450.67  4980.8  449.84
  4990.9  448.07  4996.9  446.39  4997.9  446.11  5000.7  445.61  5003.9  446.11
  5011.0  448.39  5021.1  449.46  5031.1  451.74  5055.3  452.66  5077.3  452.65
  5091.5  452.80  5111.6  453.60  5132.0  452.71  5139.8  453.19  5146.3  452.85
  5160.7  452.85  5203.7  453.53  5232.3  453.54  5253.1  452.93  5289.9  452.74
#Mann=6,-1,0
  4667.8    0.05       0  4798.7    0.16       0  4996.9    0.05       0
  4997.9    0.04       0  5003.9    0.05       0  5077.3    0.08       0
Bank Sta=4997.9,5003.9
Exp/Cntr=0.3,0.1

Type RM Length L Ch R = 1,772,195,195,195
BEGIN DESCRIPTION:
Mapping XS 1f2d5a8a
END DESCRIPTION:
XS GIS Cut Line= 2
      3591856.07     10613724.27      3591448.04     10613743.80
#Sta/Elev= 30
  4712.4  454.19  4727.8  453.87  4748.9  453.83  4778.9  453.30  4789.0  453.31
  4799.0  452.61  4809.0  452.46  4819.0  452.02  4829.0  451.90  4869.0  452.52
  4879.1  451.04  4889.1  450.89  4909.1  450.13  4919.1  450.35  4937.5  450.35
  4940.5  450.75  4942.5  451.01  4949.1  450.92  4979.2  450.05  4989.2  447.73
  4998.4  447.56  5006.2  447.01  5009.0  446.51  5012.2  447.01  5019.2  447.96
  5059.3  450.61  5069.3  450.84  5079.3  450.78  5089.3  451.06  5120.9  450.83
#Mann=5,-1,0
  4712.4    0.05       0  4940.5    0.08       0  4998.4    0.05       0
  5006.2    0.04       0  5012.2    0.05       0
Bank Sta=5006.2,5012.2
Exp/Cntr=0.3,0.1

Type RM Length L Ch R = 1,577,182,182,182
BEGIN DESCRIPTION:
Mapping XS 6e74b32b
END DESCRIPTION:
XS GIS Cut Line= 3
      3591788.81     10613524.61      3591491.47     10613563.68
      3591424.39     10613641.58
#Sta/Elev= 30
  4761.5  450.89  4791.0  450.48  4811.1  449.68  4839.5  449.01  4844.6  449.10
  4851.5  448.64  4871.6  448.19  4918.3  447.58  4952.3  447.69  4974.5  446.47
  4982.6  446.24  4994.0  445.10  4996.7  444.60  5000.0  445.10  5002.8  445.98
  5012.8  447.48  5022.9  448.12  5037.7  449.53  5043.1  449.88  5053.2  449.83
  5059.8  450.26  5074.3  450.36  5081.9  450.73  5102.8  450.39  5109.6  450.82
  5123.6  450.76  5131.3  451.16  5137.9  450.79  5145.6  450.97  5164.2  450.60
#Mann=5,-1,0
  4761.5    0.05       0  4974.5    0.08       0  4994.0    0.07       0
  5000.0    0.08       0  5037.7    0.05       0
Bank Sta=4994,5000
Exp/Cntr=0.3,0.1

Type RM Length L Ch R = 1,395,227,227,227
BEGIN DESCRIPTION:
Mapping XS c1e40559
END DESCRIPTION:
XS GIS Cut Line= 3
      3591879.96     10613372.70      3591550.07     10613383.56
      3591478.50     10613535.36
#Sta/Elev= 30
  4707.6  449.57  4758.0  449.15  4808.0  448.02  4918.1  447.09  4949.1  445.95
  4988.1  444.82  4995.1  441.09  4997.9  440.59  5001.1  441.09  5008.1  443.28
  5018.1  444.85  5028.1  444.37  5035.4  445.97  5045.0  445.68  5050.5  446.33
  5067.1  446.60  5073.3  446.36  5078.8  448.29  5089.2  447.99  5101.6  449.24
  5111.3  448.49  5118.8  448.80  5124.4  450.28  5133.5  450.53  5141.6  450.44
  5155.6  449.25  5164.4  449.68  5177.8  449.61  5187.2  450.30  5205.5  450.46
#Mann=5,-1,0
  4707.6    0.05       0  4949.1    0.08       0  4995.1    0.07       0
  5001.1    0.08       0  5177.8    0.05       0
Bank Sta=4995.1,5001.1
Exp/Cntr=0.3,0.1

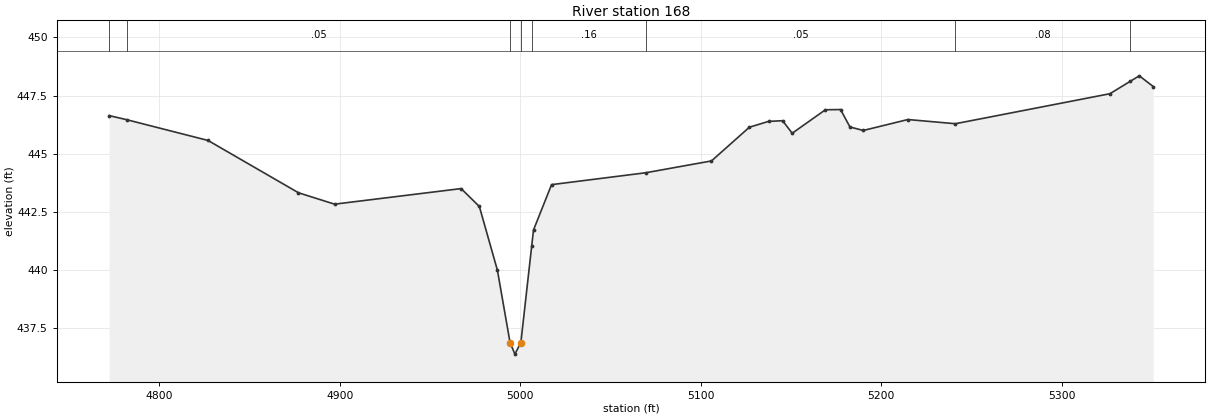
Type RM Length L Ch R = 1,168,0,0,0
BEGIN DESCRIPTION:
UNT 210 IN UKCR 1.0
END DESCRIPTION:
XS GIS Cut Line= 3
      3591834.31     10613166.54      3591539.21     10613183.90
      3591452.40     10613453.04
#Sta/Elev= 30
  4772.3  446.64  4782.2  446.46  4827.1  445.57  4877.2  443.32  4897.2  442.83
  4967.3  443.50  4977.4  442.73  4987.4  439.99  4994.4  436.88  4997.1  436.38
  5000.4  436.88  5006.4  441.03  5007.4  441.72  5017.4  443.67  5069.5  444.18
  5106.0  444.69  5127.0  446.14  5137.6  446.39  5145.4  446.42  5150.7  445.88
  5169.1  446.89  5177.5  446.90  5182.7  446.15  5190.1  446.00  5214.8  446.47
  5241.1  446.29  5326.7  447.58  5337.9  448.11  5343.0  448.35  5350.7  447.89
#Mann=8,-1,0
  4772.3    0.08       0  4782.2    0.05       0  4994.4    0.04       0
  5000.4    0.05       0  5006.4    0.16       0  5069.5    0.05       0
  5241.1    0.08       0  5337.9    0.05       0
Bank Sta=4994.4,5000.4
Exp/Cntr=0.3,0.1

Chan Stop Cuts=-1