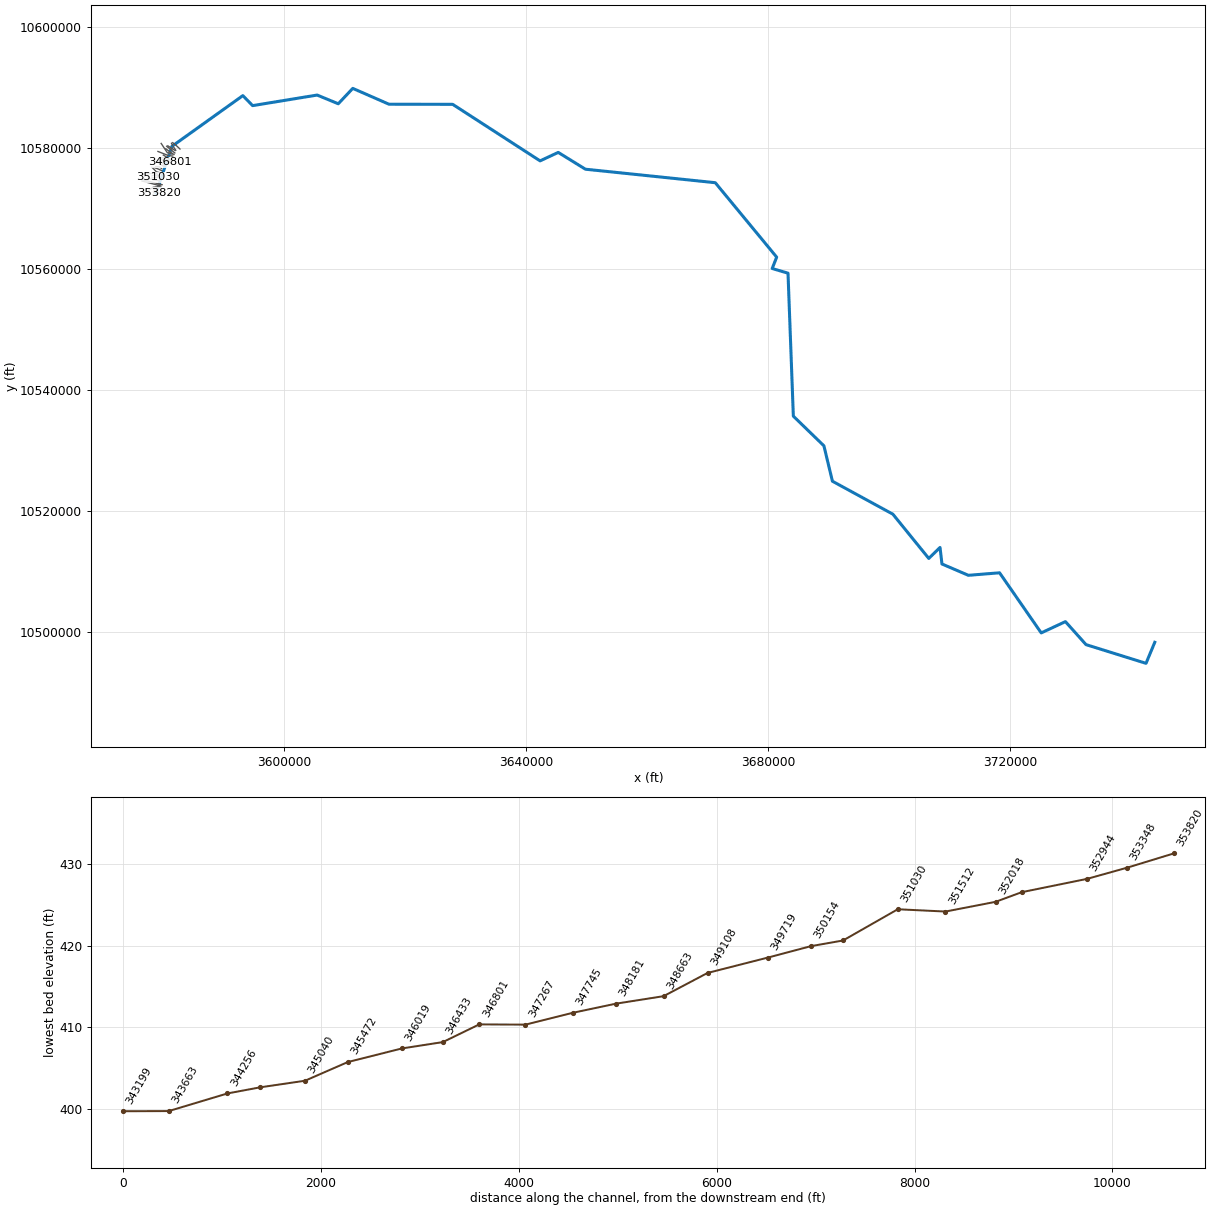
--- UPPER KEECHI CREEK.prj (project) ---

Proj Title=UPPER KEECHI CREEK Base Level Engineering
Current Plan=p01
Default Exp/Contr=0.3,0.1
English Units
Geom File=g01
Flow File=f01
Plan File=p01
Y Axis Title=Elevation
X Axis Title(PF)=Main Channel Distance
X Axis Title(XS)=Station
BEGIN DESCRIPTION:
UPPER KEECHI CREEK
END DESCRIPTION:
DSS Export Rating Curves= 0
DSS Export Rating Curve Sorted= 0
DSS Export Volume Flow Curves= 0
DXF OffsetX= 0
DXF OffsetY= 0
DXF ScaleX= 1
DXF ScaleY= 10

--- UPPER KEECHI CREEK.p01 (plan) ---

Plan Title=Multiple Run
Short Identifier=Multiple
Geom File=g01
Flow File=f01
Subcritical Flow
K Sum by GR= 0
Std Step Tol= 0.01
Critical Tol= 0.01
Num of Std Step Trials= 20
Max Error Tol= 0.3
Flow Tol Ratio= 0.001
Split Flow NTrial= 30
Split Flow Tol= 0.02
Split Flow Ratio= 0.02
Log Output Level= 0
Friction Slope Method= 1
Unsteady Friction Slope Method= 2
Unsteady Bridges Friction Slope Method= 1
Parabolic Critical Depth
Global Vel Dist=  1 , 1 , 1
Global Log Level= 0
CheckData=True
Encroach Param= -1, 0, 0, 0
BEGIN DESCRIPTION:
Multiple Run
END DESCRIPTION:

--- UPPER KEECHI CREEK.f01 (steady flow) ---

Flow Title=Multiple
Program Version=4.10
Number of Profiles= 7
Profile Names=10-year,25-year,50-year,1pct_min,100-year,1pct_plu,500-year
River Rch & RM=UPPER KEECHI CRE,Reach-1         ,353820
    1701    2402    2995    2722    3682    4979    5546
River Rch & RM=UPPER KEECHI CRE,Reach-1         ,352018
    2107    2999    3760    3432    4641    6277    7054
River Rch & RM=UPPER KEECHI CRE,Reach-1         ,347267
    2488    3559    4477    4097    5541    7493    8466
River Rch & RM=UPPER KEECHI CRE,Reach-1         ,341395
    2727    3904    4912    4493    6077    8218    9279
River Rch & RM=UPPER KEECHI CRE,Reach-1         ,337256
    4765    6973    8907    8258   11168   15103   17517
River Rch & RM=UPPER KEECHI CRE,Reach-1         ,334730
    4765    6973    8907    8258   11168   15103   17517
River Rch & RM=UPPER KEECHI CRE,Reach-1         ,331252
    6363    9377   12034   11199   15146   20483   23935
River Rch & RM=UPPER KEECHI CRE,Reach-1         ,329319
    6363    9377   12034   11199   15146   20483   23935
River Rch & RM=UPPER KEECHI CRE,Reach-1         ,321920
    8187   12167   15706   14696   19875   26878   31740
River Rch & RM=UPPER KEECHI CRE,Reach-1         ,320275
    8187   12167   15706   14696   19875   26878   31740
River Rch & RM=UPPER KEECHI CRE,Reach-1         ,319878
    8071   11962   15411   14392   19463   26321   30958
River Rch & RM=UPPER KEECHI CRE,Reach-1         ,315014
    7974   11799   15184   14162   19153   25902   30392
River Rch & RM=UPPER KEECHI CRE,Reach-1         ,314807
    9680   14409   18619   17431   23574   31881   37682
River Rch & RM=UPPER KEECHI CRE,Reach-1         ,313450
    9680   14409   18619   17431   23574   31881   37682
River Rch & RM=UPPER KEECHI CRE,Reach-1         ,310934
   10285   15300   19764   18492   25009   33821   39924
River Rch & RM=UPPER KEECHI CRE,Reach-1         ,309966
   10285   15300   19764   18492   25009   33821   39924
River Rch & RM=UPPER KEECHI CRE,Reach-1         ,305727
   10230   15195   19608   18326   24783   33517   39476
River Rch & RM=UPPER KEECHI CRE,Reach-1         ,301998
   11314   16820   21719   20306   27461   37138   43768
River Rch & RM=UPPER KEECHI CRE,Reach-1         ,299613
   11314   16820   21719   20306   27461   37138   43768
River Rch & RM=UPPER KEECHI CRE,Reach-1         ,296917
   14093   21043   27257   25554   34559   46737   55367
River Rch & RM=UPPER KEECHI CRE,Reach-1         ,293180
   14093   21043   27257   25554   34559   46737   55367
River Rch & RM=UPPER KEECHI CRE,Reach-1         ,290490
   13913   20736   26824   25115   33966   45935   54271
River Rch & RM=UPPER KEECHI CRE,Reach-1         ,286932
   14567   21730   28128   26350   35636   48193   56999
River Rch & RM=UPPER KEECHI CRE,Reach-1         ,286227
   14995   22347   28909   27063   36600   49497   58453
River Rch & RM=UPPER KEECHI CRE,Reach-1         ,284453
   14995   22347   28909   27063   36600   49497   58453
River Rch & RM=UPPER KEECHI CRE,Reach-1         ,279063
   14995   22347   28909   27063   36600   49497   58453
River Rch & RM=UPPER KEECHI CRE,Reach-1         ,276730
   15925   23731   30697   28732   38856   52548   62027
River Rch & RM=UPPER KEECHI CRE,Reach-1         ,275929
   15925   23731   30697   28732   38856   52548   62027
River Rch & RM=UPPER KEECHI CRE,Reach-1         ,269417
   16536   24654   31906   29874   40401   54638   64538
River Rch & RM=UPPER KEECHI CRE,Reach-1         ,268267
   16489   24567   31777   29738   40217   54389   64178
River Rch & RM=UPPER KEECHI CRE,Reach-1         ,262978
   16414   24415   31546   29487   39878   53930   63486
River Rch & RM=UPPER KEECHI CRE,Reach-1         ,261188
   16414   24415   31546   29487   39878   53930   63486
River Rch & RM=UPPER KEECHI CRE,Reach-1         ,260746
   16441   24405   31489   29389   39746   53751   63082
River Rch & RM=UPPER KEECHI CRE,Reach-1         ,259444
   16441   24405   31489   29389   39746   53751   63082
River Rch & RM=UPPER KEECHI CRE,Reach-1         ,251229
   17281   25664   33125   30924   41821   56559   66407
River Rch & RM=UPPER KEECHI CRE,Reach-1         ,248446
   17281   25664   33125   30924   41821   56559   66407
River Rch & RM=UPPER KEECHI CRE,Reach-1         ,247247
   17281   25664   33125   30924   41821   56559   66407
River Rch & RM=UPPER KEECHI CRE,Reach-1         ,244873
   16939   25093   32331   30131   40749   55108   64481
River Rch & RM=UPPER KEECHI CRE,Reach-1         ,234014
   17062   25255   32526   30302   40980   55420   64811
River Rch & RM=UPPER KEECHI CRE,Reach-1         ,228263
   17087   25242   32472   30232   40886   55293   64612
River Rch & RM=UPPER KEECHI CRE,Reach-1         ,224290
   17087   25242   32472   30232   40886   55293   64612
River Rch & RM=UPPER KEECHI CRE,Reach-1         ,219190
   16880   24902   32006   29772   40263   54450   63514
River Rch & RM=UPPER KEECHI CRE,Reach-1         ,213330
   16775   24729   31768   29539   39948   54025   62974
River Rch & RM=UPPER KEECHI CRE,Reach-1         ,212115
   16771   24715   31745   29515   39916   53982   62924
River Rch & RM=UPPER KEECHI CRE,Reach-1         ,209961
   16590   24419   31340   29116   39377   53252   61980
River Rch & RM=UPPER KEECHI CRE,Reach-1         ,203067
   16708   24571   31525   29292   39613   53573   62397
River Rch & RM=UPPER KEECHI CRE,Reach-1         ,198612
   16747   24629   31599   29362   39709   53701   62552
River Rch & RM=UPPER KEECHI CRE,Reach-1         ,196719
   16467   24171   30971   28742   38871   52568   61082
River Rch & RM=UPPER KEECHI CRE,Reach-1         ,190638
   16336   23923   30612   28379   38379   51903   60199
River Rch & RM=UPPER KEECHI CRE,Reach-1         ,181846
   16336   23923   30612   28379   38379   51903   60199
River Rch & RM=UPPER KEECHI CRE,Reach-1         ,173238
   16080   23508   30046   27820   37624   50882   58874
River Rch & RM=UPPER KEECHI CRE,Reach-1         ,161359
   16045   23436   29937   27707   37470   50674   58591
River Rch & RM=UPPER KEECHI CRE,Reach-1         ,156729
   15937   23250   29675   27445   37116   50195   57958
River Rch & RM=UPPER KEECHI CRE,Reach-1         ,150389
   15942   23256   29682   27451   37125   50207   57971
River Rch & RM=UPPER KEECHI CRE,Reach-1         ,146683
   15826   23056   29402   27170   36745   49693   57294
River Rch & RM=UPPER KEECHI CRE,Reach-1         ,139017
   15843   23074   29421   27186   36766   49721   57322
River Rch & RM=UPPER KEECHI CRE,Reach-1         ,134479
   15760   22934   29225   26992   36503   49366   56857
River Rch & RM=UPPER KEECHI CRE,Reach-1         ,133270
   15777   22952   29244   27006   36522   49392   56875
River Rch & RM=UPPER KEECHI CRE,Reach-1         ,130008
   15667   22766   28985   26747   36172   48919   56252
River Rch & RM=UPPER KEECHI CRE,Reach-1         ,127637
   15667   22766   28985   26747   36172   48919   56252
River Rch & RM=UPPER KEECHI CRE,Reach-1         ,118650
   15536   22554   28696   26462   35787   48397   55578
River Rch & RM=UPPER KEECHI CRE,Reach-1         ,111322
   15638   22710   28903   26662   36057   48763   56037
River Rch & RM=UPPER KEECHI CRE,Reach-1         ,106365
   15400   22321   28370   26135   35345   47800   54788
River Rch & RM=UPPER KEECHI CRE,Reach-1         ,96606
   15426   22356   28412   26173   35396   47869   54861
River Rch & RM=UPPER KEECHI CRE,Reach-1         ,93512
   15595   22593   28709   26448   35768   48372   55454
River Rch & RM=UPPER KEECHI CRE,Reach-1         ,88793
   15595   22593   28709   26448   35768   48372   55454
River Rch & RM=UPPER KEECHI CRE,Reach-1         ,85405
   29721   43413   55529   51456   69588   94110  108982
River Rch & RM=UPPER KEECHI CRE,Reach-1         ,80260
   29372   42851   54766   50707   68575   92740  107219
River Rch & RM=UPPER KEECHI CRE,Reach-1         ,74043
   29372   42851   54766   50707   68575   92740  107219
River Rch & RM=UPPER KEECHI CRE,Reach-1         ,64938
   29205   42556   54346   50280   67998   91959  106163
River Rch & RM=UPPER KEECHI CRE,Reach-1         ,57110
   28850   41978   53553   49495   66936   90523  104286
River Rch & RM=UPPER KEECHI CRE,Reach-1         ,46068
   28874   42008   53589   49527   66979   90581  104351
River Rch & RM=UPPER KEECHI CRE,Reach-1         ,43780
   28849   41940   53476   49403   66812   90356  104018
River Rch & RM=UPPER KEECHI CRE,Reach-1         ,39872
   28849   41940   53476   49403   66812   90356  104018
River Rch & RM=UPPER KEECHI CRE,Reach-1         ,39283
   28524   41400   52729   48660   65807   88996  102230
River Rch & RM=UPPER KEECHI CRE,Reach-1         ,28098
   28524   41400   52729   48660   65807   88996  102230
River Rch & RM=UPPER KEECHI CRE,Reach-1         ,24556
   28530   41403   52730   48657   65803   88991  102207
River Rch & RM=UPPER KEECHI CRE,Reach-1         ,21228
   28530   41403   52730   48657   65803   88991  102207
River Rch & RM=UPPER KEECHI CRE,Reach-1         ,15783
   28610   41509   52857   48771   65958   89200  102441
River Rch & RM=UPPER KEECHI CRE,Reach-1         ,8656
   28476   41252   52481   48382   65430   88487  101452
Boundary for River Rch & Prof#=UPPER KEECHI CRE,Reach-1         , 1
Up Type= 0
Dn Type= 3
Dn Slope=0.0002
Boundary for River Rch & Prof#=UPPER KEECHI CRE,Reach-1         , 2
Up Type= 0
Dn Type= 3
Dn Slope=0.0002
Boundary for River Rch & Prof#=UPPER KEECHI CRE,Reach-1         , 3
Up Type= 0
Dn Type= 3
Dn Slope=0.0002
Boundary for River Rch & Prof#=UPPER KEECHI CRE,Reach-1         , 4
Up Type= 0
Dn Type= 3
Dn Slope=0.0002
Boundary for River Rch & Prof#=UPPER KEECHI CRE,Reach-1         , 5
Up Type= 0
Dn Type= 3
Dn Slope=0.0002
Boundary for River Rch & Prof#=UPPER KEECHI CRE,Reach-1         , 6
Up Type= 0
Dn Type= 3
Dn Slope=0.0002
Boundary for River Rch & Prof#=UPPER KEECHI CRE,Reach-1         , 7
Up Type= 0
Dn Type= 3
Dn Slope=0.0002
DSS Import GetInterval= 0
DSS Import GetPeak= 0
DSS Import FillOption= 0

--- UPPER KEECHI CREEK.g01 (geometry) ---

Geom Title=Existing Conditions
Program Version=4.10

River Reach=UPPER KEECHI CRE,Reach-1
Reach XY= 30
       3578895.5       10572562.       3581507.5       10580297.
        3593235.       10588694.      3594850.25       10587040.
      3605510.75       10588787.      3609001.75       10587346.
      3611398.25       10589891.      3617382.75       10587271.
       3627905.5       10587253.      3642346.83     10577902.34
      3645344.75       10579301.      3649839.25       10576523.
       3671293.5       10574291.        3681438.       10561979.
      3680699.25       10560100.        3683312.       10559327.
      3684192.75       10535681.        3689242.       10530777.
        3690650.       10524920.        3700640.       10519466.
      3706570.75       10512149.      3708429.25       10513965.
      3708745.75       10511233.      3713112.25       10509357.
       3718266.5       10509773.      3725150.75       10499832.
      3729148.25       10501697.       3732555.5       10497892.
        3742464.       10494800.       3743911.2     10498280.72

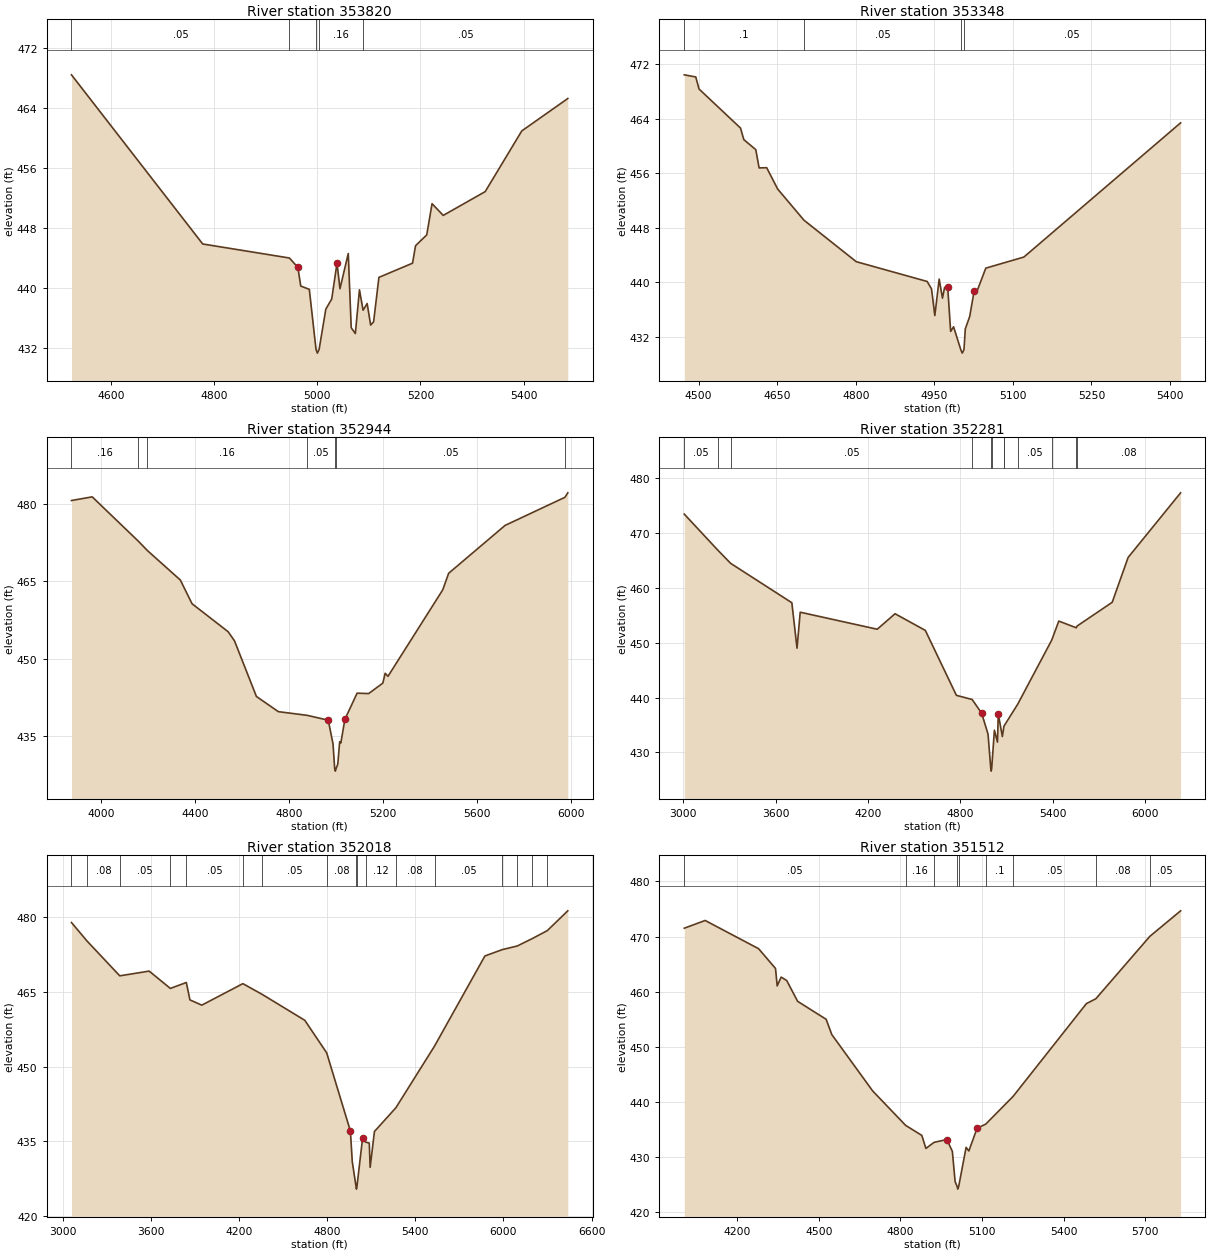
Type RM Length L Ch R = 1 ,353820  ,472,472,472
BEGIN DESCRIPTION:
UPPER KEECHI CREEK 173.0
END DESCRIPTION:
XS GIS Cut Line= 3
       3578499.6     10572660.18      3578899.61     10572860.19
       3579349.6     10572610.19
#Sta/Elev= 30
  4523.6  468.42    4778  445.87    4946     444  4962.4  442.75    4968  440.26
  4984.6  439.82  4997.6  431.82  5000.3  431.32  5003.6  431.82  5016.6  437.19
    5028  438.53  5038.3  443.32    5044   439.9  5060.1   444.6  5065.8  434.71
  5073.8  433.93  5081.8  439.76  5088.8  437.04  5096.7  437.93  5103.5  435.06
  5109.2  435.49  5119.5  441.42  5184.7  443.31  5190.5  445.64  5212.2  447.08
  5222.5  451.24  5244.2  449.68  5325.5  452.85  5396.4  460.94  5485.6  465.26
#Mann= 5 ,-1 , 0
  4523.6     .05       0    4946     .16       0  4997.6     .07       0
  5003.6     .16       0  5088.8     .05       0
Bank Sta=4962.4,5038.3
XS Rating Curve= 0 ,0
Exp/Cntr=0.3,0.1

Type RM Length L Ch R = 1 ,353348  ,404,404,404
BEGIN DESCRIPTION:
UPPER KEECHI CREEK 172.0
END DESCRIPTION:
XS GIS Cut Line= 3
      3578449.58     10572810.15      3578749.61     10573210.19
      3579149.65     10573410.21
#Sta/Elev= 30
  4472.8  470.47  4494.7  470.16    4501  468.38  4580.1  462.65  4586.4  460.95
  4609.3  459.47  4615.6  456.79  4630.1  456.82    4651  453.69  4701.2  449.11
    4801  443.01  4936.4   440.1  4944.7  439.01    4951  435.09  4959.3  440.45
  4965.6  437.65  4969.7  439.23  4975.6  439.23  4981.2  432.76  4986.8  433.44
  5000.6  430.07  5003.3  429.57  5006.6  430.07  5009.2  433.14  5017.6  434.96
    5026  438.69  5031.5  438.67  5048.3  442.06    5121  443.69  5420.1  463.41
#Mann= 4 ,-1 , 0
  4472.8      .1       0  4701.2     .05       0  5000.6     .03       0
  5006.6     .05       0
Bank Sta=4975.6,5026
XS Rating Curve= 0 ,0
Exp/Cntr=0.3,0.1

Type RM Length L Ch R = 1 ,352944  ,663,663,663
BEGIN DESCRIPTION:
UPPER KEECHI CREEK 171.0
END DESCRIPTION:
XS GIS Cut Line= 4
      3577672.43     10573045.66      3578401.57     10573524.81
      3578818.24     10573587.31      3579636.19     10573552.66
#Sta/Elev= 30
  3872.9  480.62  3961.2  481.33    4158  472.72  4196.3  470.92  4336.2  465.22
    4386  460.63  4539.6  455.21  4566.8  453.44  4660.1  442.66  4753.5  439.72
  4875.6  439.01  4965.9  438.07  4986.1  433.47  4993.2   428.7  4995.9   428.2
  4999.2   428.7  5006.3  429.53  5014.5  433.89  5019.5  433.67  5036.6  438.22
  5088.6   443.3  5137.8  443.22  5198.1  445.25  5208.1  447.16    5220  446.56
  5453.2  463.32  5478.4  466.53  5718.6   475.8  5973.1  481.24  5985.4  482.11
#Mann= 7 ,-1 , 0
  3872.9     .16       0    4158     .05       0  4196.3     .16       0
  4875.6     .05       0  4993.2     .03       0  4999.2     .05       0
  5973.1     .08       0
Bank Sta=4965.9,5036.6
XS Rating Curve= 0 ,0
Exp/Cntr=0.3,0.1

Type RM Length L Ch R = 1 ,352281  ,263,263,263
BEGIN DESCRIPTION:
UPPER KEECHI CREEK 170.0
END DESCRIPTION:
XS GIS Cut Line= 2
      3576561.33     10574573.42      3579679.35     10573753.98
#Sta/Elev= 30
  3007.5  473.49  3224.3  466.94  3308.3  464.51  3706.2  457.31  3739.8  449.01
  3760.5  455.58  4260.7  452.47  4376.6   455.3  4573.2  452.26    4775   440.4
  4877.5  439.64  4939.2  437.13  4980.6  433.31  4998.3  427.06    5001  426.56
  5004.3  427.06  5021.9  434.03  5041.9  431.86  5047.1  437.03  5073.6  432.88
  5084.2   434.8    5085  434.82  5173.9  438.81  5394.2  450.48  5440.2  453.96
  5553.6  452.74  5559.4  453.06  5787.1  457.39  5890.5  465.58  6231.4  477.38
#Mann= 12 ,-1 , 0
  3007.5     .05       0  3224.3     .08       0  3308.3     .05       0
  4877.5     .12       0  4998.3     .07       0  5004.3     .12       0
  5084.2      .1       0    5085     .12       0  5173.9     .05       0
  5394.2     .08       0  5553.6     .05       0  5559.4     .08       0
Bank Sta=4939.2,5047.1
XS Rating Curve= 0 ,0
Exp/Cntr=0.3,0.1

Type RM Length L Ch R = 1 ,352018  ,506,506,506
BEGIN DESCRIPTION:
UPPER KEECHI CREEK 169.0
END DESCRIPTION:
XS GIS Cut Line= 3
      3576623.81     10574809.53      3579401.57     10574080.37
      3579894.64     10573969.26
#Sta/Elev= 30
  3061.1  478.94  3167.4  475.21  3389.7  468.23  3589.7  469.18  3733.9   465.7
  3842.7  466.89  3867.1   463.4  3947.9  462.34  4227.4  466.66  4360.6  464.47
  4648.7   459.3  4797.7  452.76  4959.1  437.05  4971.7  430.94  4997.5  425.88
  5000.2  425.38  5003.5  425.88  5041.8  435.56  5062.7  434.82  5087.6  434.62
  5093.5  429.76  5122.8  436.96  5268.9  441.74  5531.7  454.12  5874.3  472.22
  5991.9  473.49  6094.2  474.22  6196.5  475.71  6298.8  477.31  6438.4  481.29
#Mann= 17 ,-1 , 0
  3061.1     .05       0  3167.4     .08       0  3389.7     .05       0
  3733.9     .08       0  3842.7     .05       0  4227.4     .08       0
  4360.6     .05       0  4797.7     .08       0  4997.5     .07       0
  5003.5     .08       0  5062.7     .12       0  5268.9     .08       0
  5531.7     .05       0  5991.9     .16       0  6094.2     .05       0
  6196.5     .16       0  6298.8      .1       0
Bank Sta=4959.1,5041.8
XS Rating Curve= 0 ,0
Exp/Cntr=0.3,0.1

Type RM Length L Ch R = 1 ,351512  ,482,482,482
BEGIN DESCRIPTION:
UPPER KEECHI CREEK 168.0
END DESCRIPTION:
XS GIS Cut Line= 3
      3577665.47     10574983.14      3578554.35     10574747.04
      3579449.89     10574615.14
#Sta/Elev= 30
  4005.4  471.51  4082.1  472.91  4278.7  467.79  4340.8  464.21    4347  461.05
  4361.5  462.64    4382  462.02  4422.1  458.25    4527  454.99  4547.8  452.22
  4698.2  441.99  4819.3  435.75  4878.8  433.93  4893.8  431.57  4923.7  432.67
  4970.8  433.19  4991.1  431.03  5001.2  425.57  5008.4  424.69  5011.1  424.19
  5014.4  424.69  5041.6  431.76  5051.7  431.11    5082  435.23  5113.9  435.98
  5214.5  441.01    5484  457.84  5518.6  458.71  5717.2  470.03  5830.3  474.66
#Mann= 9 ,-1 , 0
  4005.4     .05       0  4819.3     .16       0  4923.7     .12       0
  5008.4     .07       0  5014.4     .12       0  5113.9      .1       0
  5214.5     .05       0  5518.6     .08       0  5717.2     .05       0
Bank Sta=4970.8,5082
XS Rating Curve= 0 ,0
Exp/Cntr=0.3,0.1

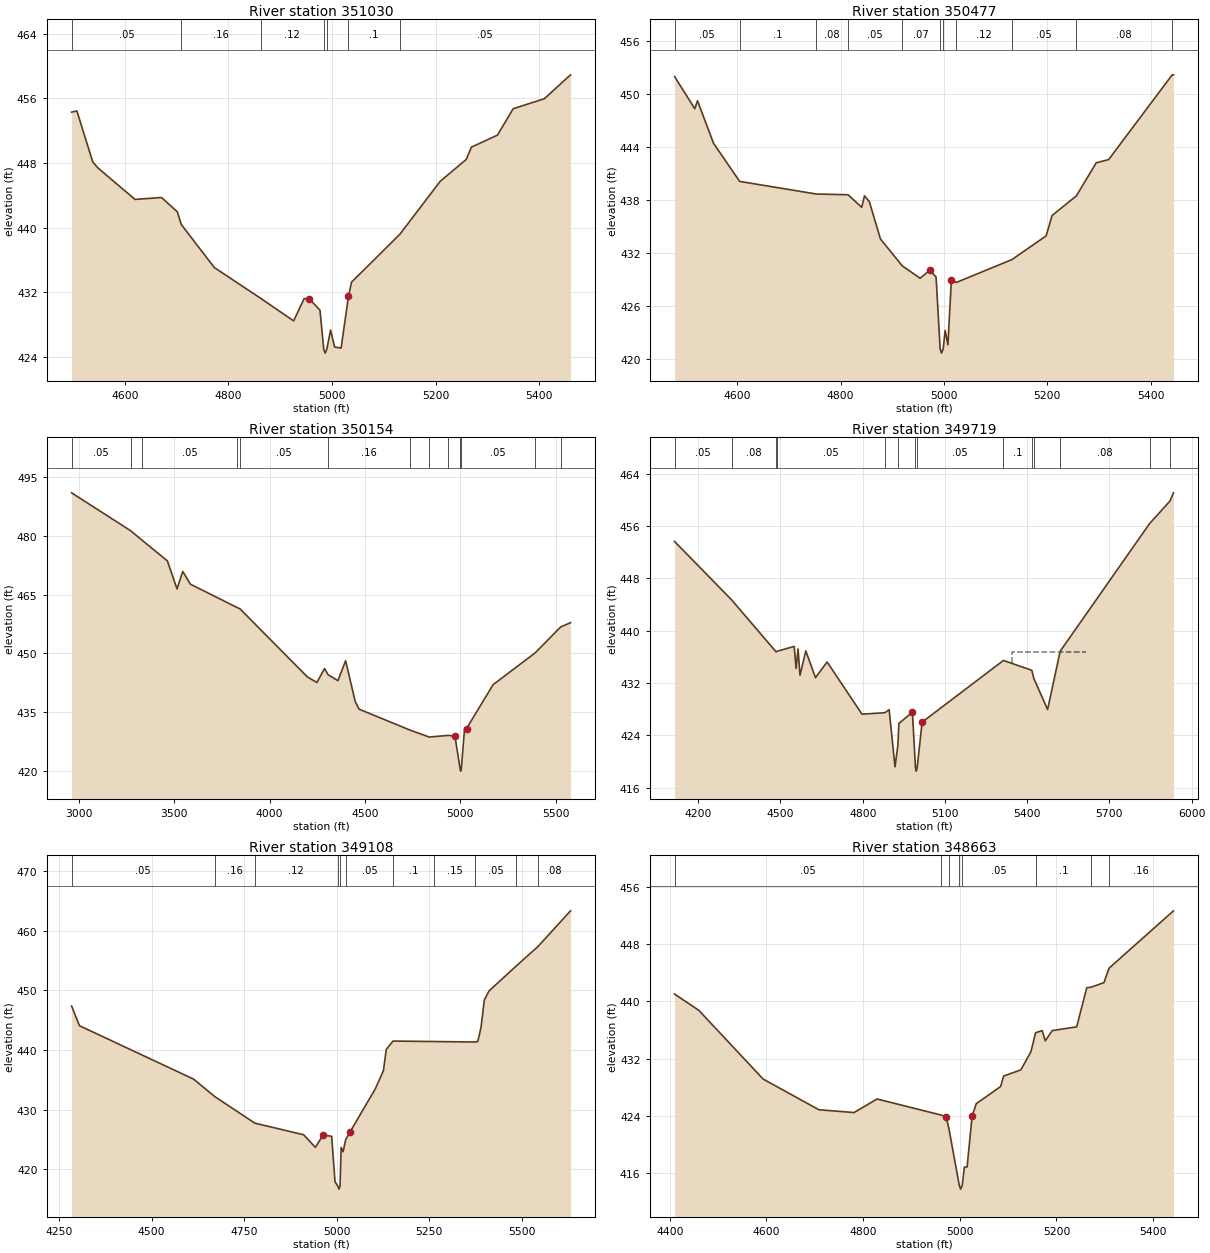
Type RM Length L Ch R = 1 ,351030  ,553,553,553
BEGIN DESCRIPTION:
UPPER KEECHI CREEK 167.0
END DESCRIPTION:
XS GIS Cut Line= 3
      3578199.57     10575060.18      3578699.61     10575160.19
       3579149.6     10575210.19
#Sta/Elev= 30
  4497.3  454.29  4507.5  454.44  4538.1  448.13  4548.3  447.38  4619.7  443.49
  4670.7  443.73  4701.3  441.96  4708.9  440.39  4772.7  435.06  4862.2  431.25
  4925.7  428.46    4946  431.22  4956.2  431.17  4976.6  429.78  4983.8  424.97
  4986.6  424.47  4989.8  424.97    4997  427.33  5004.7  425.23  5017.3  425.09
  5031.5  431.48  5037.4  433.25  5130.6  439.17  5208.5  445.73  5258.8  448.44
  5268.8  449.96  5319.1  451.45  5349.3  454.71  5409.7  455.96    5460  458.91
#Mann= 7 ,-1 , 0
  4497.3     .05       0  4708.9     .16       0  4862.2     .12       0
  4983.8     .07       0  4989.8     .12       0  5031.5      .1       0
  5130.6     .05       0
Bank Sta=4956.2,5031.5
XS Rating Curve= 0 ,0
Exp/Cntr=0.3,0.1

Type RM Length L Ch R = 1 ,350477  ,323,323,323
BEGIN DESCRIPTION:
UPPER KEECHI CREEK 166.0
END DESCRIPTION:
XS GIS Cut Line= 3
      3578199.59     10575410.18      3578699.61     10575610.19
      3579099.57      10575460.2
#Sta/Elev= 30
  4478.6  451.96  4517.7  448.32    4523  449.22    4554  444.41  4604.5  440.09
  4753.1  438.66  4814.3  438.58  4840.8  437.16  4846.2  438.46  4855.6  437.79
  4877.1  433.57  4919.2  430.53  4953.9  429.12  4972.7  430.04  4984.8  429.25
  4992.6  421.14  4995.3  420.64  4998.6  421.14  5002.3  423.21  5007.7  421.59
  5014.4  428.97  5024.2  428.65  5131.4  431.23  5197.8  433.92  5209.4  436.23
  5256.3  438.45  5294.8   442.2  5318.8  442.56  5441.8  452.16  5444.3  452.16
#Mann= 11 ,-1 , 0
  4478.6     .05       0  4604.5      .1       0  4753.1     .08       0
  4814.3     .05       0  4919.2     .07       0  4992.6     .07       0
  4998.6     .07       0  5024.2     .12       0  5131.4     .05       0
  5256.3     .08       0  5441.8     .05       0
Bank Sta=4972.7,5014.4
XS Rating Curve= 0 ,0
Exp/Cntr=0.3,0.1

Type RM Length L Ch R = 1 ,350154  ,435,435,435
BEGIN DESCRIPTION:
UPPER KEECHI CREEK 165.0
END DESCRIPTION:
XS GIS Cut Line= 4
      3576829.64     10575702.95      3578704.67     10575869.62
      3579031.06     10575827.96      3579224.69     10575475.27
#Sta/Elev= 30
  2963.2  491.03  3272.5  481.35  3330.9  478.99  3465.1  473.64  3515.3   466.5
  3545.5  470.95  3585.6   467.7  3829.2  461.76  3845.7  461.39    4198  444.03
  4248.2  442.59  4288.4  446.16  4306.9  444.57  4358.6  443.06  4398.8  448.15
    4449  437.75  4469.1  435.78  4737.9   430.4  4836.9  428.66    4937  429.08
  4971.6  428.89  4998.8  420.45  5001.6  419.95  5004.8  420.45    5022  430.88
  5032.1  430.81  5171.4  442.03  5392.5  450.18  5525.1  456.76    5577  457.87
#Mann= 13 ,-1 , 0
  2963.2     .05       0  3272.5     .16       0  3330.9     .05       0
  3829.2     .08       0  3845.7     .05       0  4306.9     .16       0
  4737.9     .12       0  4836.9     .07       0    4937     .05       0
  4998.8     .03       0  5004.8     .05       0  5392.5     .08       0
  5525.1     .05       0
Bank Sta=4971.6,5032.1
XS Rating Curve= 0 ,0
Exp/Cntr=0.3,0.1

Type RM Length L Ch R = 1 ,349719  ,611,611,611
BEGIN DESCRIPTION:
UPPER KEECHI CREEK 164.0
END DESCRIPTION:
XS GIS Cut Line= 3
      3578208.88      10576856.4      3578953.66     10576095.99
      3579682.79     10575898.09
#Sta/Elev= 30
  4113.8  453.62  4321.9   444.7  4484.4  436.75  4486.7  436.84  4550.1   437.6
  4557.1  434.23  4564.2  437.22  4571.2  433.18  4592.5  436.91  4627.8  432.82
  4670.2  435.22  4797.5  427.25    4881  427.47  4896.5  427.93  4917.8  419.21
  4928.4  422.47    4932  425.83  4981.4  427.55  4992.6  419.05  4995.3  418.55
  4998.6  419.05  5016.8  426.03  5313.3  435.45  5416.9  433.95  5424.3  432.71
  5474.5  427.96  5520.4  436.86  5846.5  456.35  5920.8  459.79  5933.7  461.05
#Mann= 14 ,-1 , 0
  4113.8     .05       0  4321.9     .08       0  4484.4      .1       0
  4486.7     .05       0    4881     .16       0  4928.4     .05       0
  4992.6     .03       0  4998.6     .05       0  5313.3      .1       0
  5416.9     .08       0  5424.3     .05       0  5520.4     .08       0
  5846.5     .05       0  5920.8     .08       0
#XS Ineff= 1 ,-1
 5343.18 5613.64  436.81
Permanent Ineff=
       F
Bank Sta=4981.4,5016.8
XS Rating Curve= 0 ,0
Exp/Cntr=0.3,0.1

Type RM Length L Ch R = 1 ,349108  ,445,445,445
BEGIN DESCRIPTION:
UPPER KEECHI CREEK 163.0
END DESCRIPTION:
XS GIS Cut Line= 3
      3578549.63     10576810.18      3579249.61     10576560.19
      3579799.58      10576310.2
#Sta/Elev= 30
    4284  447.35  4305.2  444.05  4613.2  435.11  4671.1  432.15  4778.9  427.72
  4910.5  425.78  4942.3  423.67  4963.6  425.74  4986.4  425.51  4995.4  417.89
    5003  417.16  5005.8  416.66    5009  417.16  5011.9  423.66  5017.2  422.93
  5024.3  424.96  5036.1  426.25  5104.2  433.47  5126.1  436.51  5133.8  440.07
    5152  441.48  5262.6   441.4  5373.2  441.32    5381   441.4  5389.8  443.78
  5398.6  448.36  5411.7   449.9  5483.8     454  5543.6  457.33  5631.4  463.31
#Mann= 11 ,-1 , 0
    4284     .05       0  4671.1     .16       0  4778.9     .12       0
    5003     .07       0    5009     .12       0  5024.3     .05       0
    5152      .1       0  5262.6     .15       0  5373.2     .05       0
  5483.8     .16       0  5543.6     .08       0
Bank Sta=4963.6,5036.1
XS Rating Curve= 0 ,0
Exp/Cntr=0.3,0.1

Type RM Length L Ch R = 1 ,348663  ,482,482,482
BEGIN DESCRIPTION:
UPPER KEECHI CREEK 162.0
END DESCRIPTION:
XS GIS Cut Line= 3
      3578849.58     10576960.19      3579449.61     10576910.19
      3579799.59      10576660.2
#Sta/Elev= 30
  4409.9  441.01  4460.1  438.74  4593.1  429.16  4708.5  424.88  4781.2  424.49
  4828.9  426.38  4960.8  424.15  4971.9  423.87  4977.8  422.14    4999  414.31
  5001.7  413.81    5005  414.31  5009.5  416.89  5015.1  416.89  5025.5     424
  5034.1  425.73  5084.5  428.12  5090.7  429.58  5126.3  430.44  5147.2  432.97
  5156.8  435.62  5170.5  435.92  5176.7  434.49  5191.4  435.92  5241.8  436.44
  5262.7   441.9  5272.1  441.98  5298.3  442.61  5308.7  444.61  5442.1  452.62
#Mann= 8 ,-1 , 0
  4409.9     .05       0  4960.8     .12       0  4977.8     .05       0
    4999     .03       0    5005     .05       0  5156.8      .1       0
  5272.1     .08       0  5308.7     .16       0
Bank Sta=4971.9,5025.5
XS Rating Curve= 0 ,0
Exp/Cntr=0.3,0.1

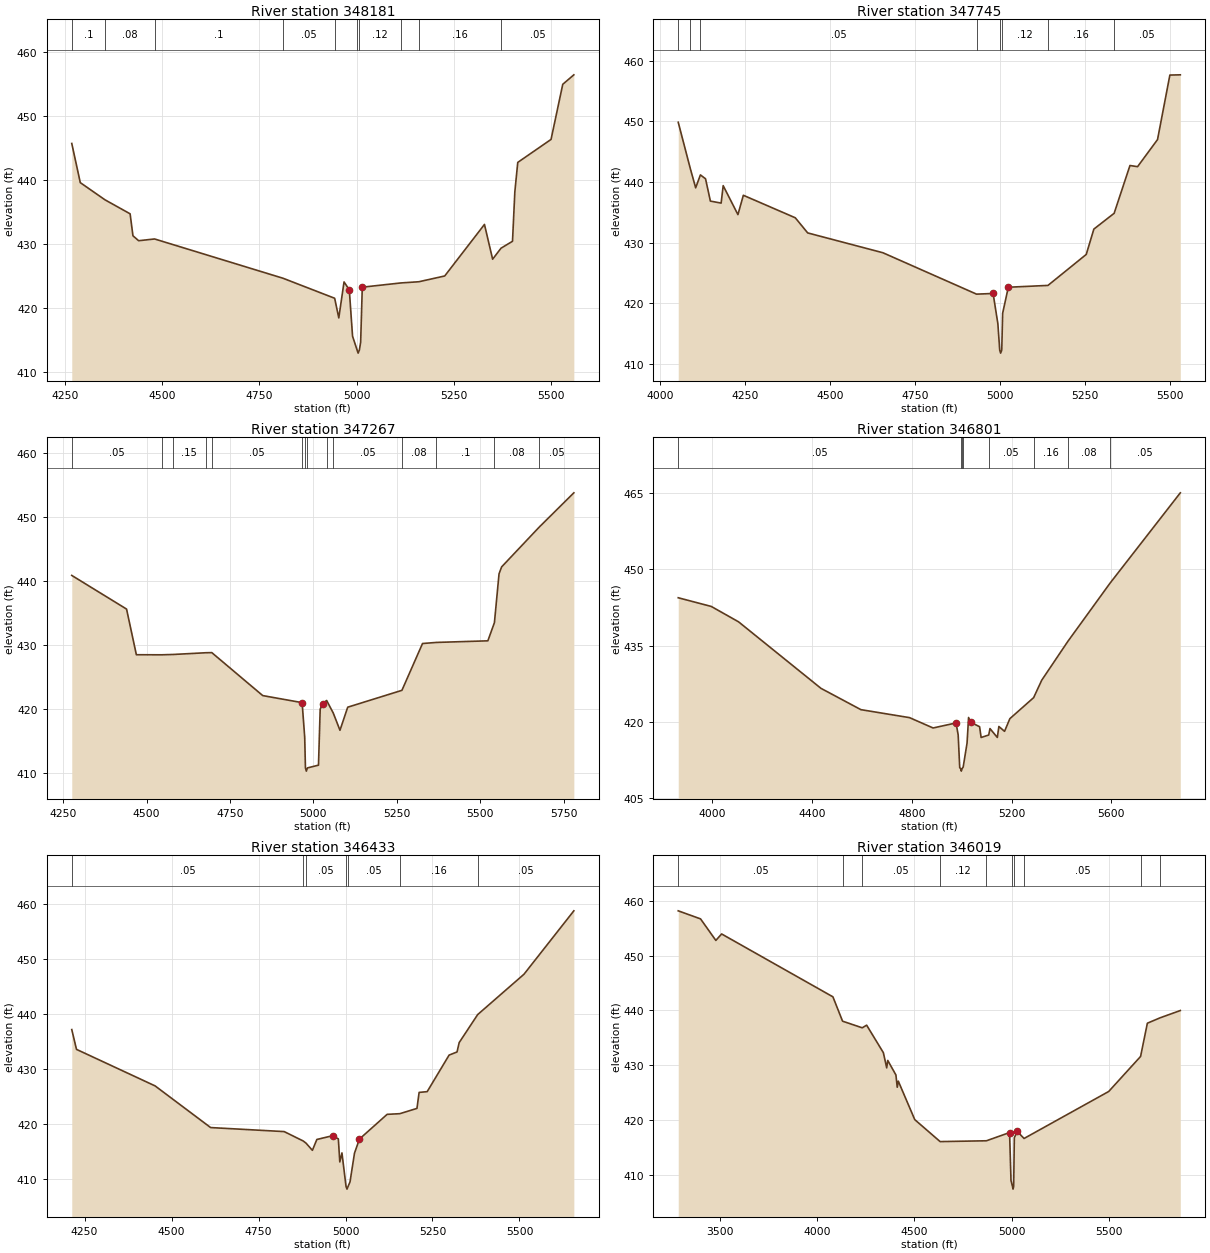
Type RM Length L Ch R = 1 ,348181  ,436,436,436
BEGIN DESCRIPTION:
UPPER KEECHI CREEK 161.0
END DESCRIPTION:
XS GIS Cut Line= 3
       3579049.6     10577760.19      3579649.61     10577310.19
      3580099.58     10577010.21
#Sta/Elev= 30
  4267.5  445.64  4289.4  439.52  4353.1  436.83  4417.5  434.65  4424.8  431.22
  4439.4  430.45  4480.5  430.72  4810.4  424.59  4943.4  421.46    4954  418.39
  4967.5  424.01    4981  422.78  4989.4  415.53    5001  413.39  5003.7  412.89
    5007  413.39  5010.2  414.61  5014.4  423.19  5113.3  423.85  5159.9  424.04
  5226.3  424.94  5328.5  432.99  5349.5  427.56  5371.1  429.28  5400.6  430.36
  5406.6  438.08  5414.1  442.68  5499.7  446.27  5529.8  454.88  5558.3  456.36
#Mann= 10 ,-1 , 0
  4267.5      .1       0  4353.1     .08       0  4480.5      .1       0
  4810.4     .05       0  4943.4     .12       0    5001     .07       0
    5007     .12       0  5113.3     .07       0  5159.9     .16       0
  5371.1     .05       0
Bank Sta=4981,5014.4
XS Rating Curve= 0 ,0
Exp/Cntr=0.3,0.1

Type RM Length L Ch R = 1 ,347745  ,478,478,478
BEGIN DESCRIPTION:
UPPER KEECHI CREEK 160.0
END DESCRIPTION:
XS GIS Cut Line= 3
      3579149.65     10578010.17      3579949.61     10577560.19
      3580199.59     10577060.23
#Sta/Elev= 30
  4053.9  449.85  4089.3  442.24  4105.2  439.04  4119.1  441.17  4134.2  440.53
  4148.5  436.85  4180.1  436.52  4186.1   439.4  4229.5  434.62  4245.4  437.81
  4398.1   434.1  4434.7   431.6  4655.9  428.33  4931.4   421.5  4980.1  421.61
  4994.1  416.61  4999.5  412.27  5002.2  411.77  5005.5  412.27  5008.1  418.34
  5024.8  422.64  5141.4  422.94    5254  428.05  5276.4  432.23  5336.1  434.84
  5382.6  442.72    5405  442.53  5463.7     447    5500  457.64  5530.7  457.68
#Mann= 8 ,-1 , 0
  4053.9      .1       0  4089.3     .08       0  4119.1     .05       0
  4931.4     .12       0  4999.5     .07       0  5005.5     .12       0
  5141.4     .16       0  5336.1     .05       0
Bank Sta=4980.1,5024.8
XS Rating Curve= 0 ,0
Exp/Cntr=0.3,0.1

Type RM Length L Ch R = 1 ,347267  ,466,466,466
BEGIN DESCRIPTION:
UPPER KEECHI CREEK 159.0
END DESCRIPTION:
XS GIS Cut Line= 3
      3579649.59      10578260.2      3580199.61     10577860.19
      3580999.59     10577660.19
#Sta/Elev= 30
  4275.8  440.84    4440  435.59  4469.4  428.47  4545.8  428.46  4578.9  428.51
  4677.4  428.78  4695.5   428.8  4848.1   422.1  4966.2     421  4967.2   420.3
  4973.9  415.61  4976.1  410.82  4978.8  410.32  4982.1  410.82  5015.2  411.25
  5020.3  419.99    5028  420.85  5039.6  421.34  5059.4  419.39  5079.6  416.69
  5102.8  420.29  5265.3  422.92    5327  430.22  5368.3  430.39  5522.8  430.64
  5542.5  433.48  5556.3  441.09  5564.1  442.17  5677.2   448.4  5780.5  453.72
#Mann= 14 ,-1 , 0
  4275.8     .05       0  4545.8      .1       0  4578.9     .15       0
  4677.4      .1       0  4695.5     .05       0  4967.2     .12       0
  4976.1     .07       0  4982.1     .12       0  5039.6     .08       0
  5059.4     .05       0  5265.3     .08       0  5368.3      .1       0
  5542.5     .08       0  5677.2     .05       0
Bank Sta=4966.2,5028
XS Rating Curve= 0 ,0
Exp/Cntr=0.3,0.1

Type RM Length L Ch R = 1 ,346801  ,368,368,368
BEGIN DESCRIPTION:
UPPER KEECHI CREEK 158.0
END DESCRIPTION:
XS GIS Cut Line= 3
      3579438.05     10578429.33      3580245.32     10578403.29
      3581219.13     10577695.06
#Sta/Elev= 30
  3864.4  444.42  3996.9  442.71  4106.1  439.69  4436.3  426.62  4596.3  422.43
  4791.4  420.86  4885.6  418.83  4977.6  419.82  4986.1  417.47  4992.3  411.04
  4995.9  410.85  4998.6  410.35  5001.9  410.85  5006.2  411.16  5021.7  415.87
  5027.8  420.89    5036  419.96  5071.9  419.08  5078.1  416.96  5108.5  417.45
  5113.6  418.71    5143  416.97  5149.2  419.12    5172  418.17  5193.2  420.66
  5288.5  424.79  5320.7   428.2  5424.9   435.8  5594.5  447.28  5876.2  465.04
#Mann= 8 ,-1 , 0
  3864.4     .05       0  4995.9     .03       0  5001.9     .05       0
  5006.2     .12       0  5108.5     .05       0  5288.5     .16       0
  5424.9     .08       0  5594.5     .05       0
Bank Sta=4977.6,5036
XS Rating Curve= 0 ,0
Exp/Cntr=0.3,0.1

Type RM Length L Ch R = 1 ,346433  ,414,414,414
BEGIN DESCRIPTION:
UPPER KEECHI CREEK 157.0
END DESCRIPTION:
XS GIS Cut Line= 3
      3580099.62     10578860.18      3580749.61     10578460.19
      3581299.63     10578060.18
#Sta/Elev= 30
  4213.1  437.13  4226.7  433.54  4452.7  426.91  4612.3  419.35  4823.7  418.62
  4878.6  416.91  4886.9   416.5  4904.8  415.22  4917.6  417.19  4962.7  417.87
  4979.4   417.3  4983.6  413.11  4989.8  414.75  5001.5  408.68  5004.3  408.18
  5007.5  408.68    5013   409.5  5025.8   414.7  5040.1  417.27  5119.7  421.75
  5156.1  421.87  5205.4  422.83  5211.6  425.73  5234.8  425.87  5297.8   432.5
  5320.6  433.07  5326.8  434.77  5379.9  439.85    5513  447.17  5656.4  458.68
#Mann= 7 ,-1 , 0
  4213.1     .05       0  4878.6     .16       0  4886.9     .05       0
  5001.5     .03       0  5007.5     .05       0  5156.1     .16       0
  5379.9     .05       0
Bank Sta=4962.7,5040.1
XS Rating Curve= 0 ,0
Exp/Cntr=0.3,0.1

Type RM Length L Ch R = 1 ,346019  ,547,547,547
BEGIN DESCRIPTION:
UPPER KEECHI CREEK 156.0
END DESCRIPTION:
XS GIS Cut Line= 3
      3579209.21     10579457.63      3580922.41     10578783.49
      3581654.74      10578695.2
#Sta/Elev= 30
  3287.7  458.17  3402.3   456.7  3480.9  452.77  3510.6  453.95  4082.2  442.48
  4131.7  438.04  4232.7  436.83  4255.4  437.31  4341.3  432.29  4358.4  429.52
  4363.8  430.88  4405.7  428.23  4412.6  425.99    4418   427.1  4502.5  420.08
  4632.8  416.07  4870.6  416.22  4989.5  417.72  4996.8  408.97  5004.5   407.9
  5007.3   407.4  5010.5   407.9  5013.9  416.78    5029  417.92  5063.9  416.64
  5498.6  425.21  5662.3   431.6  5697.2  437.67  5762.4  438.65  5866.4  439.98
#Mann= 10 ,-1 , 0
  3287.7     .05       0  4131.7      .1       0  4232.7     .05       0
  4632.8     .12       0  4870.6     .16       0  5004.5     .07       0
  5010.5     .16       0  5063.9     .05       0  5662.3      .1       0
  5762.4     .05       0
Bank Sta=4989.5,5029
XS Rating Curve= 0 ,0
Exp/Cntr=0.3,0.1

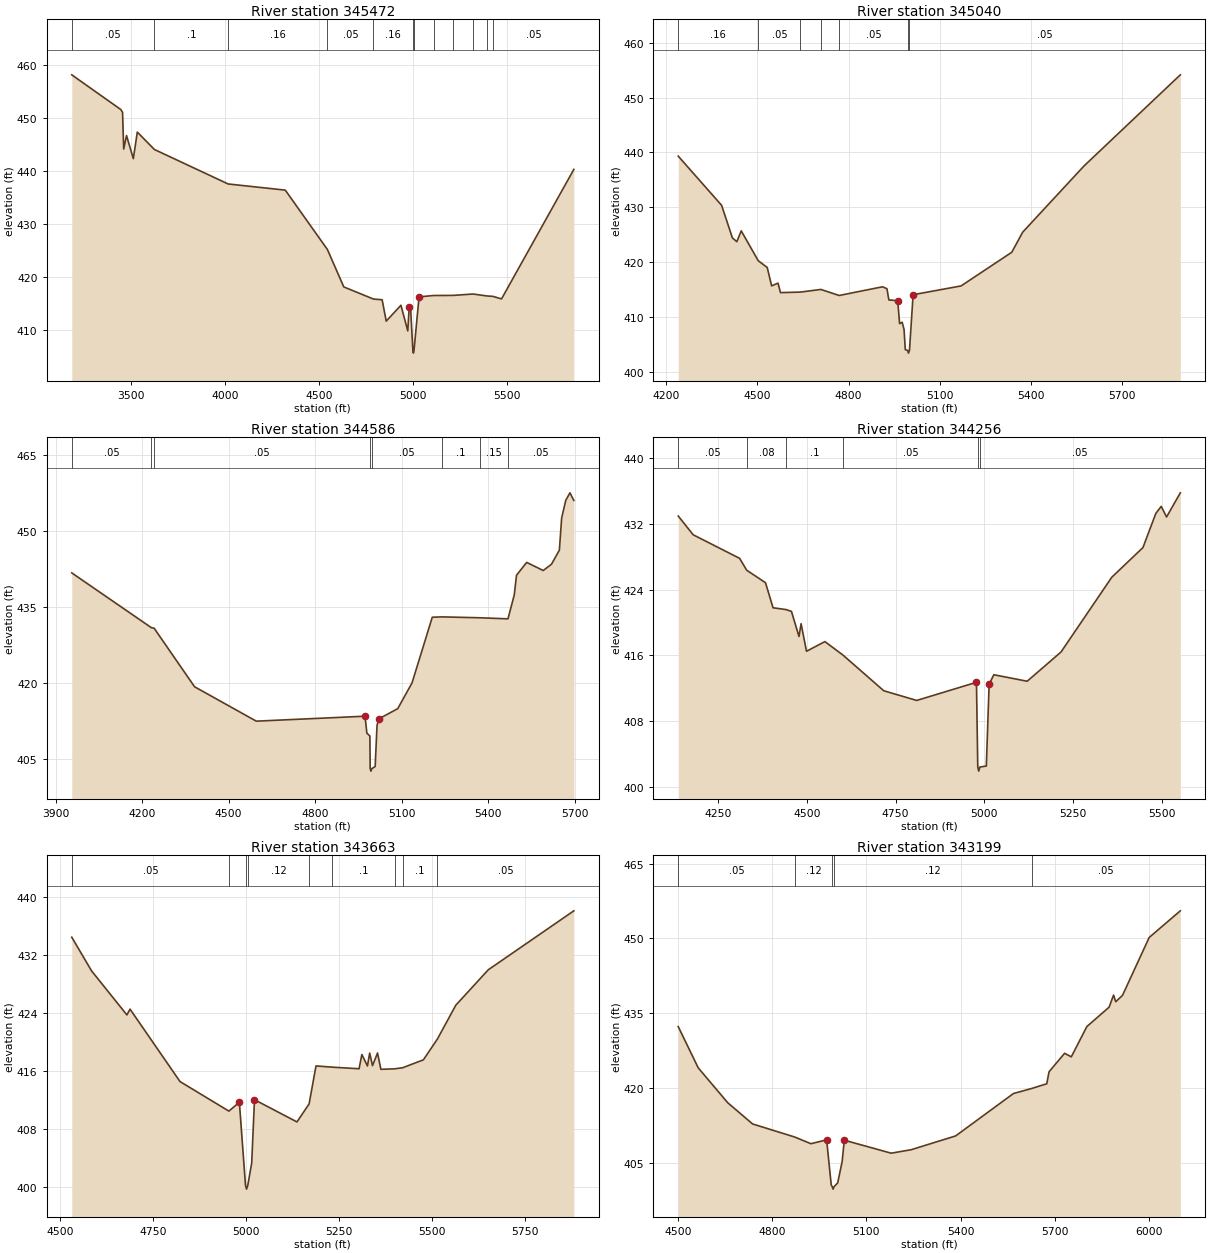
Type RM Length L Ch R = 1 ,345472  ,432,432,432
BEGIN DESCRIPTION:
UPPER KEECHI CREEK 155.0
END DESCRIPTION:
XS GIS Cut Line= 3
      3579743.04     10580785.77      3580749.61     10579260.19
      3581549.63     10579010.18
#Sta/Elev= 30
  3186.9  458.18  3447.6  451.63  3456.6  451.12  3462.6  444.19  3477.7  446.73
  3513.8  442.38  3534.9  447.39  3625.6  444.11  4017.2  437.61  4320.6  436.45
  4544.5  425.25  4631.2  418.21    4789  415.92  4834.9  415.79  4856.6  411.76
  4934.8  414.75    4971  409.92  4978.7   414.5    4986   414.2  4998.1  406.23
  5000.9  405.73  5004.1  406.23  5030.9  416.33  5107.8  416.59  5212.7  416.61
  5317.6  416.87  5392.2   416.5  5422.5  416.43  5468.8  415.95  5852.8  440.36
#Mann= 12 ,-1 , 0
  3186.9     .05       0  3625.6      .1       0  4017.2     .16       0
  4544.5     .05       0    4789     .16       0  4998.1     .07       0
  5004.1     .16       0  5107.8     .05       0  5212.7     .08       0
  5317.6      .1       0  5392.2     .15       0  5422.5     .05       0
Bank Sta=4978.7,5030.9
XS Rating Curve= 0 ,0
Exp/Cntr=0.3,0.1

Type RM Length L Ch R = 1 ,345040  ,454,454,454
BEGIN DESCRIPTION:
UPPER KEECHI CREEK 154.0
END DESCRIPTION:
XS GIS Cut Line= 3
      3580499.65     10579910.16      3581099.61     10579460.19
      3581849.58     10578960.21
#Sta/Elev= 30
  4239.4  439.32  4382.1  430.36  4417.5  424.44  4432.1  423.73  4446.6  425.71
  4502.6  420.27  4532.1  419.04  4546.6  415.69  4567.5  416.19  4575.8  414.46
  4641.5  414.56  4708.4  415.04  4768.9  413.94  4911.2  415.52  4925.8  415.18
  4932.1  413.13  4961.2  412.99  4967.5  408.81  4975.8  409.07  4982.1  407.76
  4986.2  404.07  4993.9  403.94  4996.6  403.44  4999.9  403.94  5011.9  414.08
  5169.6  415.68  5336.4  421.81  5372.4  425.48  5573.8  437.52  5890.7  454.13
#Mann= 7 ,-1 , 0
  4239.4     .16       0  4502.6     .05       0  4641.5      .1       0
  4708.4     .08       0  4768.9     .05       0  4993.9     .03       0
  4999.9     .05       0
Bank Sta=4961.2,5011.9
XS Rating Curve= 0 ,0
Exp/Cntr=0.3,0.1

Type RM Length L Ch R = 1 ,344586  ,330,330,330
BEGIN DESCRIPTION:
UPPER KEECHI CREEK 153.0
END DESCRIPTION:
XS GIS Cut Line= 3
      3580649.61     10580310.19      3581449.61     10579660.19
       3581999.6      10579210.2
#Sta/Elev= 30
    3956  441.75  4232.1  430.94  4241.6  430.84  4381.9  419.28    4596  412.49
  4973.2  413.47  4979.6  410.11    4990  409.57    4991  403.13  4993.7  402.63
    4997  403.13  5008.3  403.54  5014.8  411.71  5022.7  412.99  5086.6  414.96
  5136.1  420.03  5206.4     433  5240.3  433.07  5372.8  432.89  5468.9  432.68
  5490.7  437.39  5498.6  441.29  5533.8  443.82  5591.2  442.22  5619.9  443.46
  5647.2  446.24  5655.1  452.58  5669.4  456.07  5683.8  457.55  5697.4  456.05
#Mann= 8 ,-1 , 0
    3956     .05       0  4232.1     .08       0  4241.6     .05       0
    4991     .03       0    4997     .05       0  5240.3      .1       0
  5372.8     .15       0  5468.9     .05       0
Bank Sta=4973.2,5022.7
XS Rating Curve= 0 ,0
Exp/Cntr=0.3,0.1

Type RM Length L Ch R = 1 ,344256  ,593,593,593
BEGIN DESCRIPTION:
UPPER KEECHI CREEK 152.0
END DESCRIPTION:
XS GIS Cut Line= 3
      3580839.11     10580387.64      3581411.99     10580028.29
      3582031.79     10579627.24
#Sta/Elev= 30
  4137.5  432.95  4179.6  430.67  4310.4   427.8  4330.5  426.35  4383.4  424.83
  4404.6  421.78    4441  421.56  4456.5  421.34  4477.7  418.28  4483.6  419.84
  4498.9  416.48  4550.7  417.66  4601.5  416.02  4716.5  411.67  4809.4  410.49
  4977.7   412.7  4981.4  402.38  4984.1  401.88  4987.4  402.38  5005.5   402.5
  5013.4  412.47  5026.6  413.62  5120.6  412.83  5215.9  416.39    5359   425.5
  5446.7  429.11    5483  433.27  5498.2  434.13  5513.3  432.84    5552  435.78
#Mann= 6 ,-1 , 0
  4137.5     .05       0  4330.5     .08       0    4441      .1       0
  4601.5     .05       0  4981.4     .03       0  4987.4     .05       0
Bank Sta=4977.7,5013.4
XS Rating Curve= 0 ,0
Exp/Cntr=0.3,0.1

Type RM Length L Ch R = 1 ,343663  ,464,464,464
BEGIN DESCRIPTION:
UPPER KEECHI CREEK 151.0
END DESCRIPTION:
XS GIS Cut Line= 3
      3581449.62     10580810.17      3581649.61     10580410.19
      3582149.62     10579660.18
#Sta/Elev= 30
  4531.7   434.4  4584.8  429.77  4679.8   423.7  4688.2   424.5  4822.4  414.53
  4953.7  410.46  4981.9  411.68  4998.4  400.22  5001.2  399.72  5004.4  400.22
    5015  403.31  5022.5  412.03  5136.6  408.97  5169.2  411.45  5187.7  416.68
  5231.2  416.51  5303.4  416.29  5310.9  418.25  5325.9  416.68  5331.9  418.45
  5339.5  416.72    5353  418.46    5362  416.21    5399  416.28  5420.6  416.43
  5476.2  417.52  5513.8  420.38  5563.3  425.04  5650.4  429.91  5880.3  438.03
#Mann= 9 ,-1 , 0
  4531.7     .05       0  4953.7     .12       0  4998.4     .07       0
  5004.4     .12       0  5169.2     .05       0  5231.2      .1       0
    5399     .08       0  5420.6      .1       0  5513.8     .05       0
Bank Sta=4981.9,5022.5
XS Rating Curve= 0 ,0
Exp/Cntr=0.3,0.1

Type RM Length L Ch R = 1 ,343199  ,437,437,437
BEGIN DESCRIPTION:
UPPER KEECHI CREEK 150.0
END DESCRIPTION:
XS GIS Cut Line= 3
       3581649.6      10580910.2      3582049.61     10580610.19
      3582849.61     10579860.19
#Sta/Elev= 30
  4501.7  432.29  4565.3  424.02    4659  417.03  4738.2  412.77  4872.1  410.15
  4923.6  408.81  4973.6  409.58  4988.2  400.56  4991.4   400.2  4994.2   399.7
  4997.4   400.2  5008.8  400.95    5023  405.25  5029.8  409.51  5178.8  406.91
  5242.3   407.6  5383.9  410.37  5567.6  418.87    5626  419.89  5673.6  420.83
  5680.9  423.23  5730.3  426.94  5751.7  426.23  5801.1   432.3  5871.9  436.19
  5886.1  438.61  5892.9  437.28  5914.4  438.55  5999.4  450.17  6098.3  455.51
#Mann= 5 ,-1 , 0
  4501.7     .05       0  4872.1     .12       0  4991.4     .07       0
  4997.4     .12       0    5626     .05       0
Bank Sta=4973.6,5029.8
XS Rating Curve= 0 ,0
Exp/Cntr=0.3,0.1