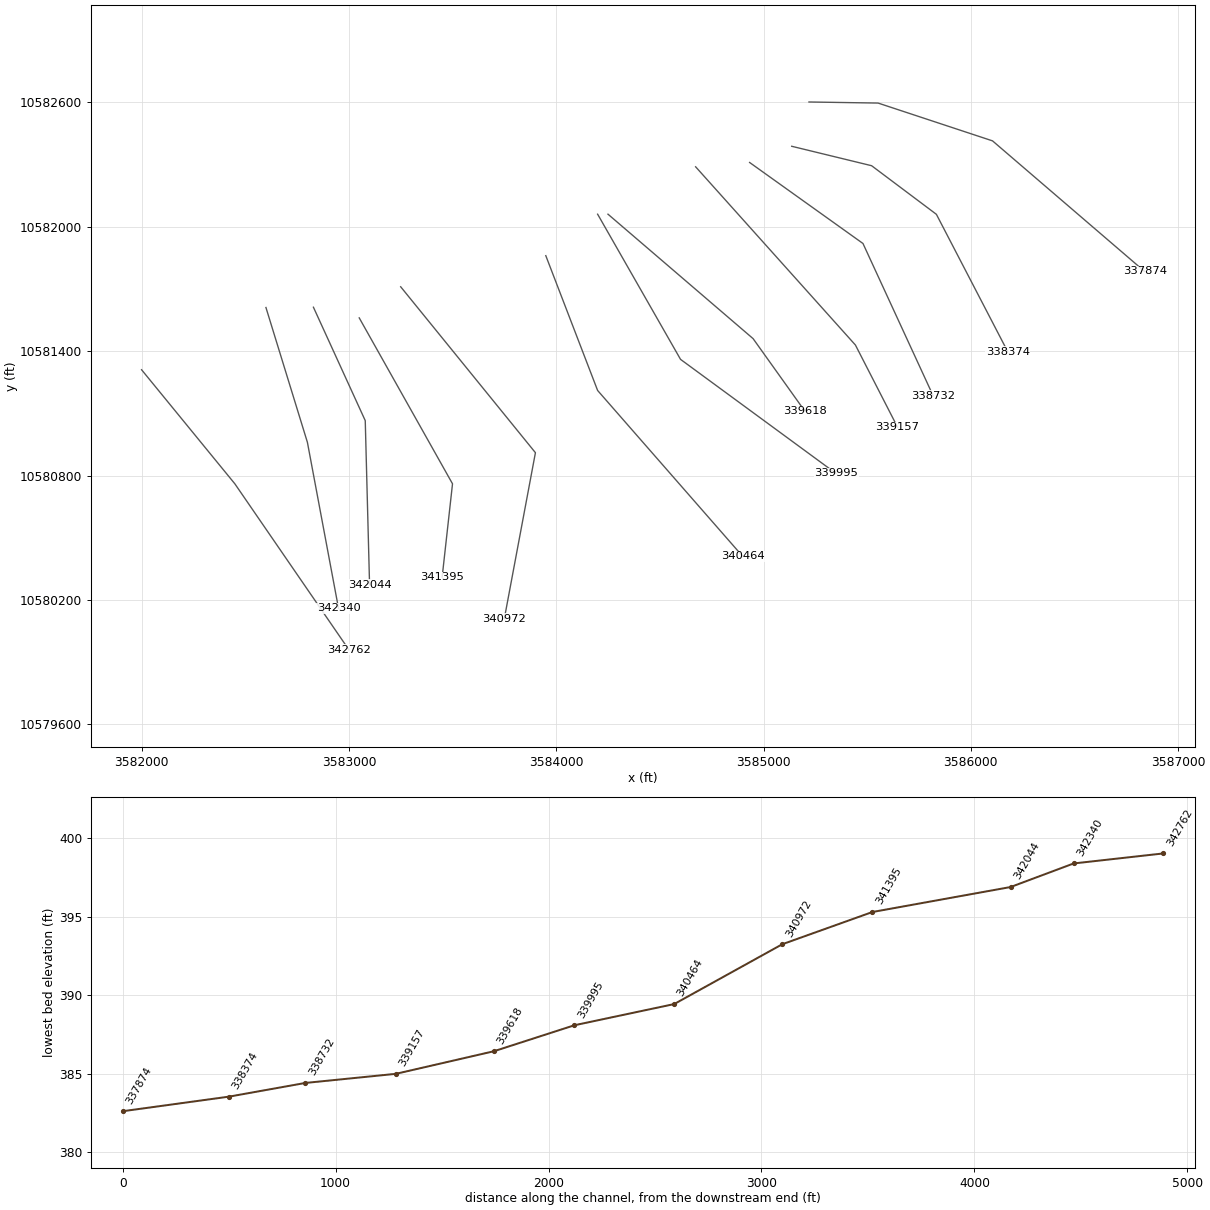
HEC-RAS study UPPER KEECHI CREEK.prj: UPPER KEECHI CREEK Base Level Engineering

--- UPPER KEECHI CREEK.g01 (geometry) --- (continued)

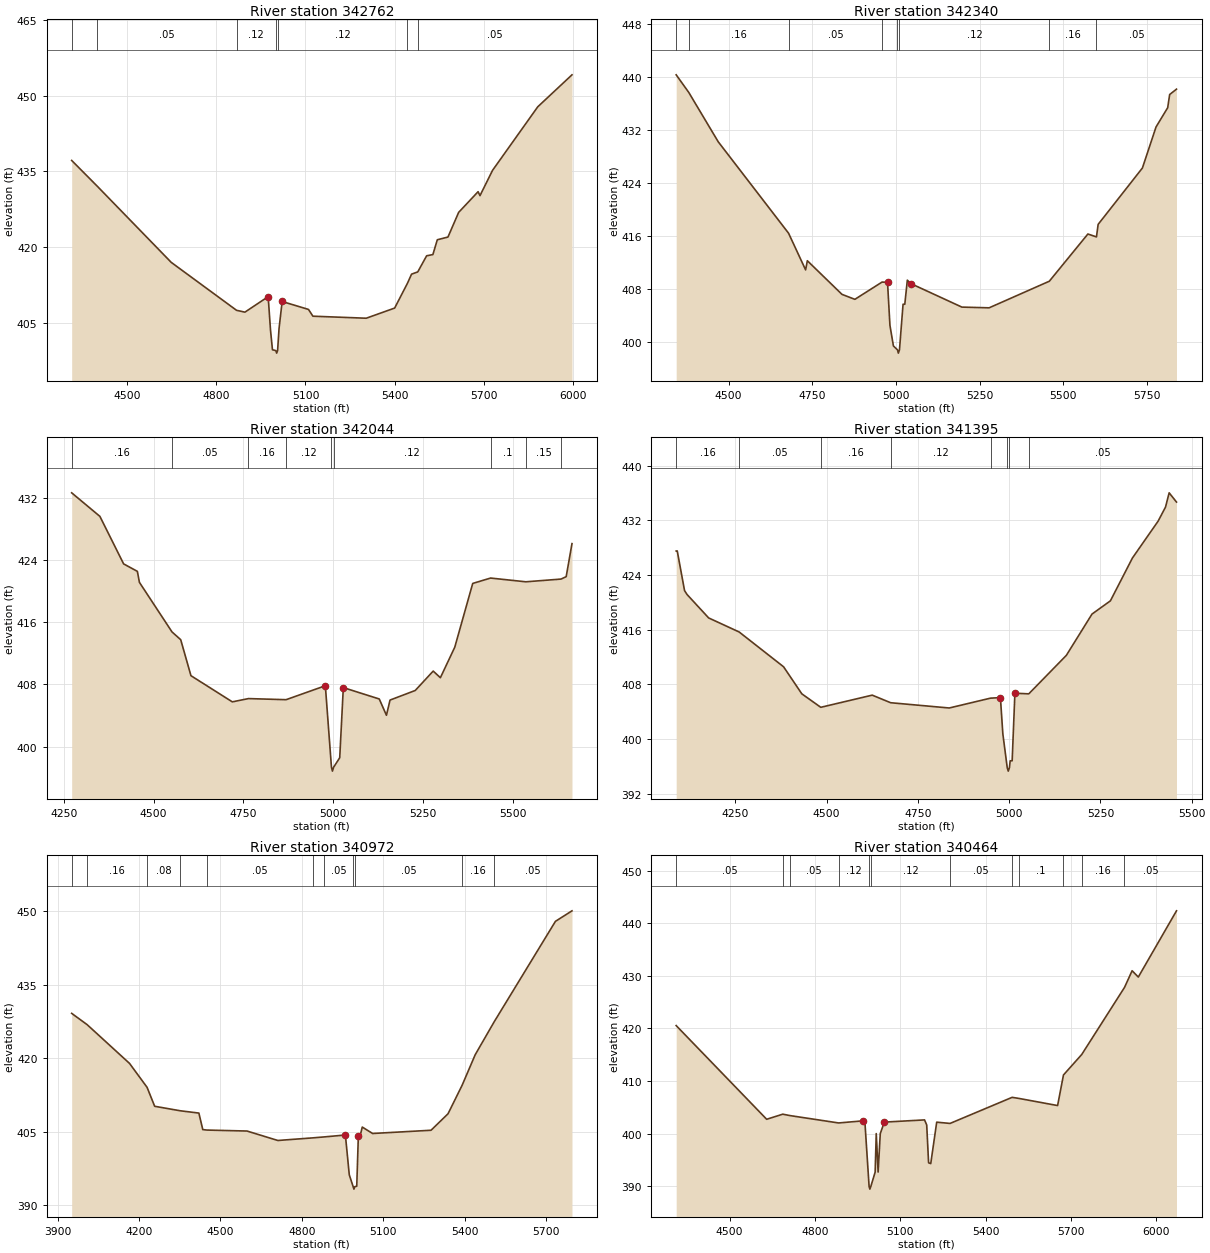
Type RM Length L Ch R = 1 ,342762  ,422,422,422
BEGIN DESCRIPTION:
UPPER KEECHI CREEK 149.0
END DESCRIPTION:
XS GIS Cut Line= 3
       3581999.6      10581310.2      3582449.61     10580760.19
      3582999.63     10579960.17
#Sta/Elev= 30
  4314.2  437.16  4399.2  432.12  4648.7  416.99  4868.2   407.5  4896.4  407.13
  4974.6   410.2  4982.5  403.55    4989  399.69  5000.3  399.52  5003.1  399.02
  5006.3  399.52  5011.2  403.92  5021.6  409.24  5110.1  407.67    5125  406.33
  5304.2  405.93  5399.7  407.94  5442.6  412.83  5456.5  414.65  5477.4   415.1
  5507.2  418.29  5528.2  418.53  5543.1  421.46  5578.9     422  5614.8  426.88
  5680.2  430.98  5686.5  430.19  5728.7   435.2  5880.7  447.78  5995.7  454.11
#Mann= 7 ,-1 , 0
  4314.2      .1       0  4399.2     .05       0  4868.2     .12       0
  5000.3     .07       0  5006.3     .12       0  5442.6     .16       0
  5477.4     .05       0
Bank Sta=4974.6,5021.6
XS Rating Curve= 0 ,0
Exp/Cntr=0.3,0.1

Type RM Length L Ch R = 1 ,342340  ,296,296,296
BEGIN DESCRIPTION:
UPPER KEECHI CREEK 148.0
END DESCRIPTION:
XS GIS Cut Line= 3
       3582599.6     10581610.23      3582799.61     10580960.19
      3582949.62     10580160.15
#Sta/Elev= 30
  4343.6  440.34  4381.1  437.69  4469.2  430.24  4679.3  416.45  4730.1  410.93
  4735.3  412.31  4838.7  407.24  4877.2  406.49  4958.3  409.09  4974.7  409.07
  4981.9  402.58  4992.3  399.46  5004.4  398.88  5007.1  398.38  5010.4  398.88
  5021.1  405.75  5026.3  405.75  5033.9  409.38  5044.1  408.87  5196.7  405.32
  5278.1  405.21  5457.9  409.22  5573.1  416.34  5598.7   415.9  5603.7  417.79
  5735.9  426.29  5776.6  432.48  5811.4  435.38  5817.3  437.37  5837.7  438.18
#Mann= 8 ,-1 , 0
  4343.6     .05       0  4381.1     .16       0  4679.3     .05       0
  4958.3     .12       0  5004.4     .07       0  5010.4     .12       0
  5457.9     .16       0  5598.7     .05       0
Bank Sta=4974.7,5044.1
XS Rating Curve= 0 ,0
Exp/Cntr=0.3,0.1

Type RM Length L Ch R = 1 ,342044  ,649,649,649
BEGIN DESCRIPTION:
UPPER KEECHI CREEK 147.0
END DESCRIPTION:
XS GIS Cut Line= 3
      3582828.67     10581611.59      3583078.66     10581064.74
      3583099.46      10580274.1
#Sta/Elev= 30
  4271.9   432.6  4350.4  429.58  4416.4  423.48  4454.7  422.52  4460.4  421.11
  4551.2  414.74  4575.3  413.75  4603.8  409.13  4718.9  405.77  4763.9  406.19
  4868.5  406.05  4977.8  407.84  4994.8  397.38  4997.5  396.88  5000.8  397.38
  5017.8   398.6  5027.8   407.6  5127.8  406.14  5147.8  404.05  5157.8     406
  5227.9  407.23  5277.9  409.72  5297.9  408.87  5337.9  412.78  5387.9  420.97
  5437.6  421.66  5535.6  421.18  5633.6  421.53    5648  421.84  5664.1  426.08
#Mann= 9 ,-1 , 0
  4271.9     .16       0  4551.2     .05       0  4763.9     .16       0
  4868.5     .12       0  4994.8     .07       0  5000.8     .12       0
  5437.6      .1       0  5535.6     .15       0  5633.6     .07       0
Bank Sta=4977.8,5027.8
XS Rating Curve= 0 ,0
Exp/Cntr=0.3,0.1

Type RM Length L Ch R = 1 ,341395  ,423,423,423
BEGIN DESCRIPTION:
UPPER KEECHI CREEK 146.0
END DESCRIPTION:
XS GIS Cut Line= 3
      3583049.61     10581560.18      3583499.61     10580760.19
      3583449.61     10580310.23
#Sta/Elev= 30
  4087.9  427.51  4090.8  427.51  4110.8  421.71  4117.5  421.15  4176.8  417.71
  4260.5  415.65  4382.1  410.56  4432.1   406.6    4484  404.63  4624.9  406.41
  4675.5   405.3  4835.9  404.53    4949  405.97  4976.1  406.05  4982.8  400.74
  4994.8  395.79  4997.6  395.29  5000.8  395.79  5002.9   396.8  5008.3   396.8
  5015.8  406.69  5053.8   406.6  5156.7  412.23  5227.1  418.28  5277.4  420.21
  5337.8  426.48  5408.2  431.88  5428.4  433.93  5438.4  436.02  5458.5  434.67
#Mann= 8 ,-1 , 0
  4087.9     .16       0  4260.5     .05       0    4484     .16       0
  4675.5     .12       0    4949     .16       0  4994.8     .07       0
  5000.8     .16       0  5053.8     .05       0
Bank Sta=4976.1,5015.8
XS Rating Curve= 0 ,0
Exp/Cntr=0.3,0.1

Type RM Length L Ch R = 1 ,340972  ,508,508,508
BEGIN DESCRIPTION:
UPPER KEECHI CREEK 145.0
END DESCRIPTION:
XS GIS Cut Line= 3
      3583249.62     10581710.18      3583899.61     10580910.19
      3583749.61     10580110.19
#Sta/Elev= 30
  3951.5  429.16  4008.7  426.84  4164.8  418.93  4229.5  414.04  4257.5  410.17
    4352  409.25  4420.5  408.78  4434.9  405.41  4449.7  405.31    4598  405.11
  4711.7  403.18  4841.9  403.72  4880.7   403.9  4960.7   404.3  4975.1  396.15
  4989.4  393.74  4992.2  393.24  4995.4  393.74  5002.6  393.83  5008.5  404.13
  5013.6  403.81    5023  405.92  5061.1  404.61  5276.5  405.27  5339.2  408.64
  5391.2  414.47  5439.3   420.7  5509.2  427.42  5735.2  447.96  5796.2  450.11
#Mann= 11 ,-1 , 0
  3951.5     .05       0  4008.7     .16       0  4229.5     .08       0
    4352      .1       0  4449.7     .05       0  4841.9     .16       0
  4880.7     .05       0  4989.4     .03       0  4995.4     .05       0
  5391.2     .16       0  5509.2     .05       0
Bank Sta=4960.7,5008.5
XS Rating Curve= 0 ,0
Exp/Cntr=0.3,0.1

Type RM Length L Ch R = 1 ,340464  ,469,469,469
BEGIN DESCRIPTION:
UPPER KEECHI CREEK 144.0
END DESCRIPTION:
XS GIS Cut Line= 3
      3583949.62     10581860.15      3584199.61     10581210.19
      3584899.61     10580410.18
#Sta/Elev= 30
  4312.1  420.52  4630.3  402.71    4687  403.68  4711.3  403.42  4883.4  402.01
  4968.8  402.41  4976.3   401.7  4990.5  389.93  4993.2  389.43  4996.5  389.93
  5011.8  392.67  5015.6  399.99  5022.2  392.67  5029.8  399.99  5044.1  402.17
  5185.5  402.59  5193.1  401.63  5199.7  394.44  5207.3  394.28  5228.2  402.16
  5275.2  401.92  5493.5  406.88  5516.7  406.68  5653.4  405.32    5674  411.13
  5738.3  415.03  5888.6  427.77  5915.4  430.95  5937.2  429.75  6071.5  442.34
#Mann= 12 ,-1 , 0
  4312.1     .05       0    4687      .1       0  4711.3     .05       0
  4883.4     .12       0  4990.5     .07       0  4996.5     .12       0
  5275.2     .05       0  5493.5     .08       0  5516.7      .1       0
    5674     .05       0  5738.3     .16       0  5888.6     .05       0
Bank Sta=4968.8,5044.1
XS Rating Curve= 0 ,0
Exp/Cntr=0.3,0.1

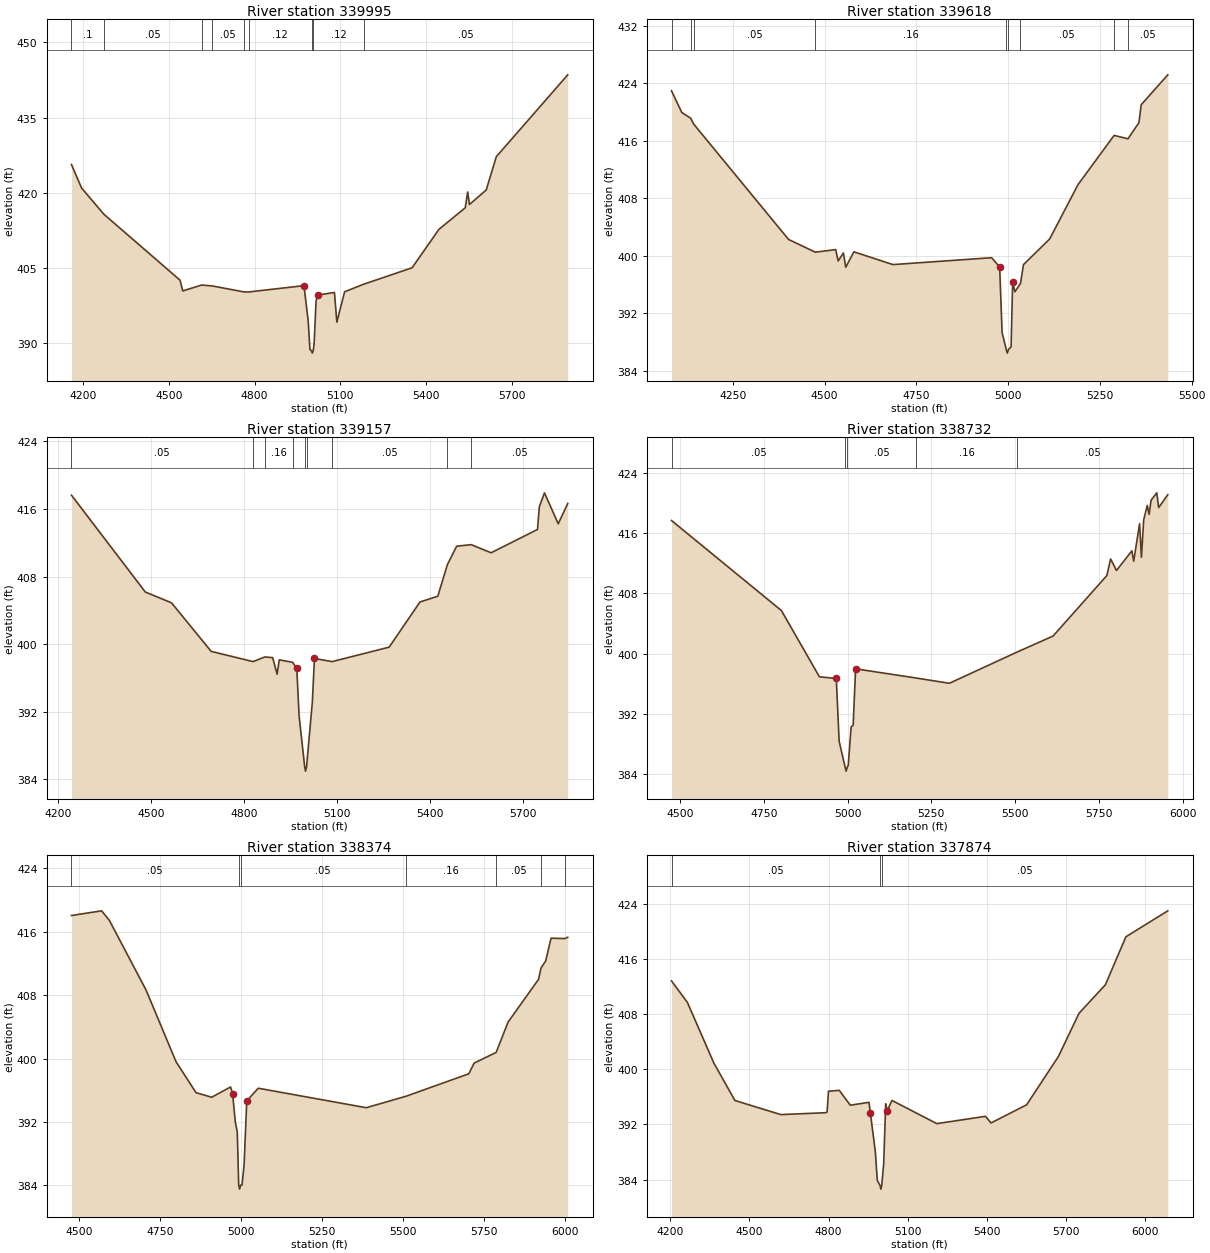
Type RM Length L Ch R = 1 ,339995  ,377,377,377
BEGIN DESCRIPTION:
UPPER KEECHI CREEK 143.0
END DESCRIPTION:
XS GIS Cut Line= 3
      3584199.62     10582060.16      3584599.61     10581360.19
      3585349.65     10580810.16
#Sta/Elev= 30
  4159.5  425.64  4194.7  420.98  4272.9  415.74  4539.5   402.6  4548.9  400.47
  4614.8  401.64    4652  401.46  4762.5  400.28    4779  400.26    4973  401.52
  4987.7  394.47  4993.9  388.75  4999.3  388.58  5002.1  388.08  5005.3  388.58
  5008.5  389.97  5015.3  398.53  5023.2  399.67  5079.6  400.16    5088  394.25
  5115.1   400.3  5181.7   401.8  5351.2  405.08  5445.4  412.75  5537.3  417.03
  5545.7  420.17  5551.9  417.68  5610.5  420.56    5646  427.21  5895.8  443.51
#Mann= 9 ,-1 , 0
  4159.5      .1       0  4272.9     .05       0  4614.8     .16       0
    4652     .05       0  4762.5     .07       0    4779     .12       0
  4999.3     .07       0  5005.3     .12       0  5181.7     .05       0
Bank Sta=4973,5023.2
XS Rating Curve= 0 ,0
Exp/Cntr=0.3,0.1

Type RM Length L Ch R = 1 ,339618  ,461,461,461
BEGIN DESCRIPTION:
UPPER KEECHI CREEK 142.0
END DESCRIPTION:
XS GIS Cut Line= 3
      3584249.58     10582060.21      3584949.61     10581460.19
       3585199.6      10581110.2
#Sta/Elev= 30
  4082.9  422.96  4110.9  419.94  4135.3  419.14  4142.9  418.35  4401.8  402.26
  4474.7  400.49  4530.2  400.85  4536.8  399.27  4551.1  400.38  4557.6   398.4
  4579.6  400.54  4686.1  398.76    4955  399.72  4976.9  398.42  4983.5   389.3
  4994.8  386.93  4997.5  386.43  5000.8  386.93    5008   387.3  5012.3  396.35
  5018.4  394.97  5033.5  396.12  5041.8  398.76    5113  402.32  5190.5  409.91
  5288.7  416.75  5326.5  416.28  5356.4  418.53  5362.5  421.02    5435  425.19
#Mann= 9 ,-1 , 0
  4082.9      .1       0  4135.3     .08       0  4142.9     .05       0
  4474.7     .16       0  4994.8     .07       0  5000.8     .16       0
  5033.5     .05       0  5288.7     .08       0  5326.5     .05       0
Bank Sta=4976.9,5012.3
XS Rating Curve= 0 ,0
Exp/Cntr=0.3,0.1

Type RM Length L Ch R = 1 ,339157  ,425,425,425
BEGIN DESCRIPTION:
UPPER KEECHI CREEK 141.0
END DESCRIPTION:
XS GIS Cut Line= 3
       3584672.4     10582288.71      3585443.24     10581429.33
      3585646.34     10581033.53
#Sta/Elev= 30
  4244.2  417.62  4482.2  406.17  4566.7  404.89  4694.5  399.15  4829.5  397.94
  4867.4  398.49  4892.6  398.41  4906.8  396.45  4913.9  398.15  4956.8  397.86
  4970.3  397.13  4977.8   391.5  4995.8  385.49  4998.5  384.99  5001.8  385.49
  5020.5  393.18  5027.2  398.31  5084.1  397.94  5267.9  399.65  5367.3  404.99
  5424.7  405.67  5455.8  409.42  5485.6  411.59  5532.6  411.77  5596.6  410.81
  5746.1  413.57  5751.9  416.24  5768.5   417.9  5812.9  414.24  5843.5  416.64
#Mann= 9 ,-1 , 0
  4244.2     .05       0  4829.5     .12       0  4867.4     .16       0
  4956.8     .12       0  4995.8     .07       0  5001.8     .12       0
  5084.1     .05       0  5455.8      .1       0  5532.6     .05       0
Bank Sta=4970.3,5027.2
XS Rating Curve= 0 ,0
Exp/Cntr=0.3,0.1

Type RM Length L Ch R = 1 ,338732  ,358,358,358
BEGIN DESCRIPTION:
UPPER KEECHI CREEK 140.0
END DESCRIPTION:
XS GIS Cut Line= 3
      3584932.86     10582309.51       3585479.7     10581918.91
      3585818.09     10581184.87
#Sta/Elev= 30
  4475.1  417.67  4802.9  405.72  4916.2  396.93  4966.5  396.71    4975  388.39
    4993  384.91  4995.8  384.41    4999  384.91  5002.2   385.2  5010.8  390.27
  5016.9  390.52  5024.1  397.99  5202.9  396.78  5303.8  396.07  5506.2  400.22
  5613.2  402.34  5773.4  410.36  5784.9  412.57  5802.3  411.04  5848.2  413.65
  5853.7  412.28  5871.2  417.25  5876.7   412.8  5883.5  417.77  5894.1  419.67
  5899.7  418.49  5905.5  420.37  5922.6  421.35  5928.1  419.39  5955.4   421.1
#Mann= 5 ,-1 , 0
  4475.1     .05       0    4993     .03       0    4999     .05       0
  5202.9     .16       0  5506.2     .05       0
Bank Sta=4966.5,5024.1
XS Rating Curve= 0 ,0
Exp/Cntr=0.3,0.1

Type RM Length L Ch R = 1 ,338374  ,500,500,500
BEGIN DESCRIPTION:
UPPER KEECHI CREEK 139.0
END DESCRIPTION:
XS GIS Cut Line= 4
       3585135.9     10582387.67      3585521.36     10582293.91
      3585833.86     10582059.54      3586177.63     10581398.05
#Sta/Elev= 30
  4477.2  418.06  4570.4  418.65  4594.2  417.45  4707.4  408.67  4800.1  399.62
  4861.8  395.71  4910.3  395.13  4968.6  396.43  4974.9  395.59  4983.2  392.02
  4989.4  390.72  4993.7  384.04  4996.5  383.54  4999.7  384.04    5004  384.06
  5010.3  386.55  5018.6  394.67    5054  396.27  5387.8  393.81    5510  395.25
  5704.4  398.09  5720.9  399.44  5788.9  400.79  5825.8  404.62  5919.9  410.01
  5927.4  411.42    5942  412.34  5958.5   415.2  6000.9  415.15    6010  415.31
#Mann= 7 ,-1 , 0
  4477.2     .05       0  4993.7     .03       0  4999.7     .05       0
    5510     .16       0  5788.9     .05       0  5927.4     .08       0
  6000.9     .15       0
Bank Sta=4974.9,5018.6
XS Rating Curve= 0 ,0
Exp/Cntr=0.3,0.1

Type RM Length L Ch R = 1 ,337874  ,618,618,618
BEGIN DESCRIPTION:
UPPER KEECHI CREEK 138.0
END DESCRIPTION:
XS GIS Cut Line= 4
       3585219.3      10582601.2      3585552.61     10582595.99
       3586104.7      10582413.7      3586838.11     10581784.32
#Sta/Elev= 30
  4204.9  412.78  4265.2  409.65  4365.2  400.89  4445.2  395.45  4619.3  393.41
  4787.8  393.68  4794.5  393.78  4799.8  396.79  4840.5  396.93  4882.6  394.77
  4953.3  395.19  4958.5  393.67  4977.4  388.05    4985  383.86  4995.5  383.11
  4998.2  382.61  5001.5  383.11    5009  386.24  5016.7  394.98    5022  393.96
  5040.6  395.46  5210.6   392.1    5395  393.16    5416   392.2  5550.9  394.83
  5671.6  401.84  5749.5  408.09  5849.4  412.22  5927.3  419.18  6086.1  422.94
#Mann= 3 ,-1 , 0
  4204.9     .05       0  4995.5     .03       0  5001.5     .05       0
Bank Sta=4958.5,5022
XS Rating Curve= 0 ,0
Exp/Cntr=0.3,0.1