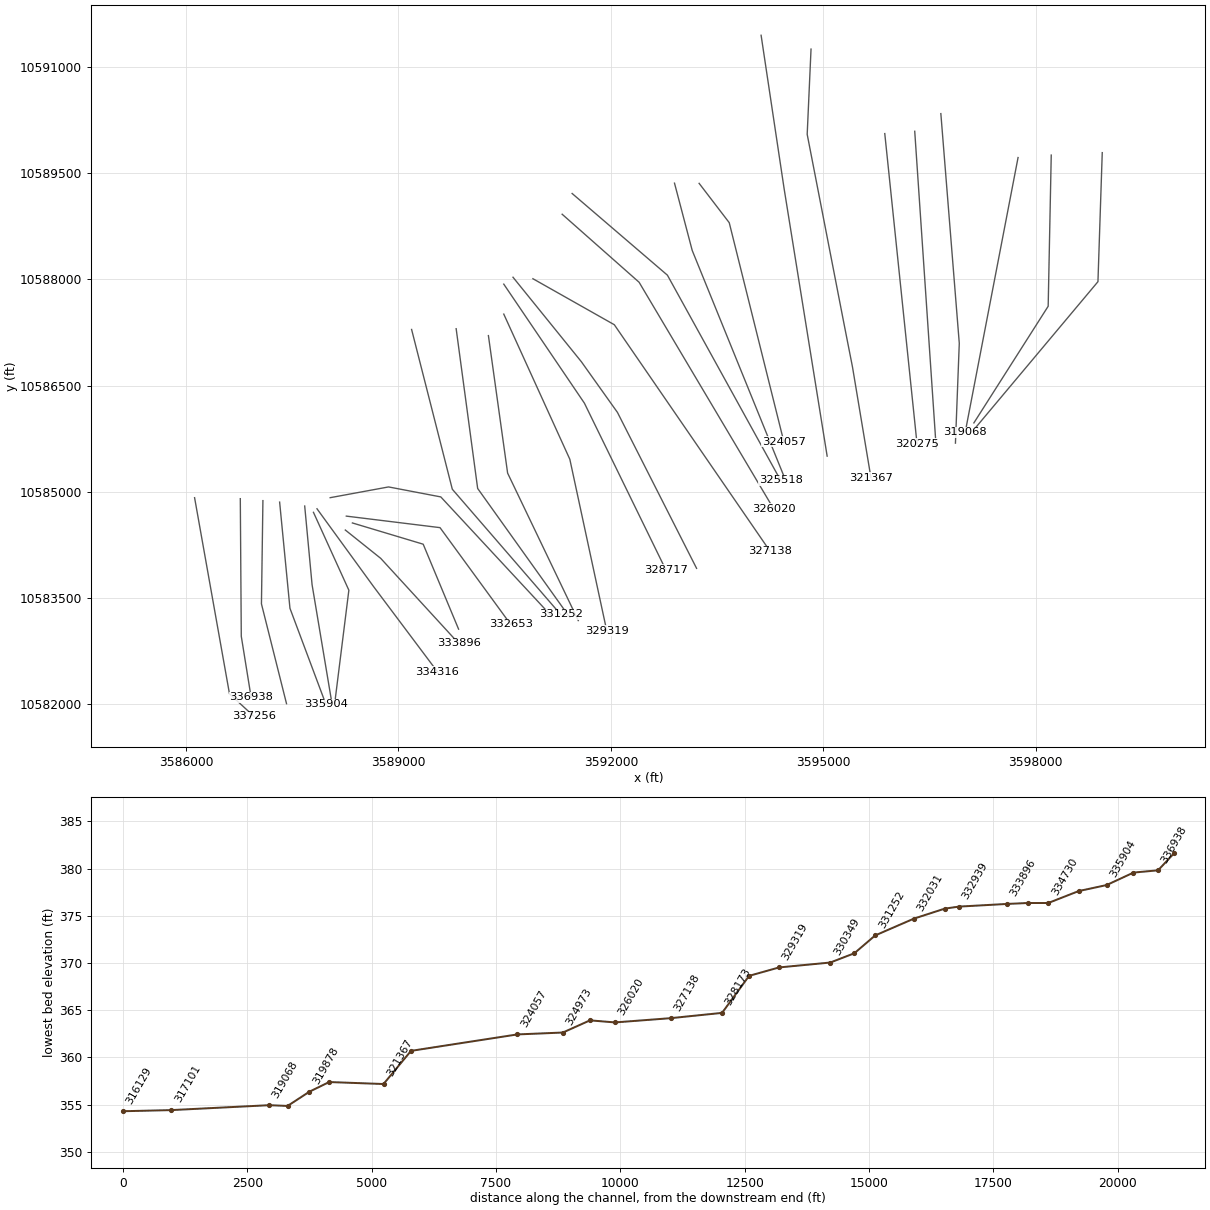
HEC-RAS study UPPER KEECHI CREEK.prj: UPPER KEECHI CREEK Base Level Engineering

--- UPPER KEECHI CREEK.g01 (geometry) --- (continued)

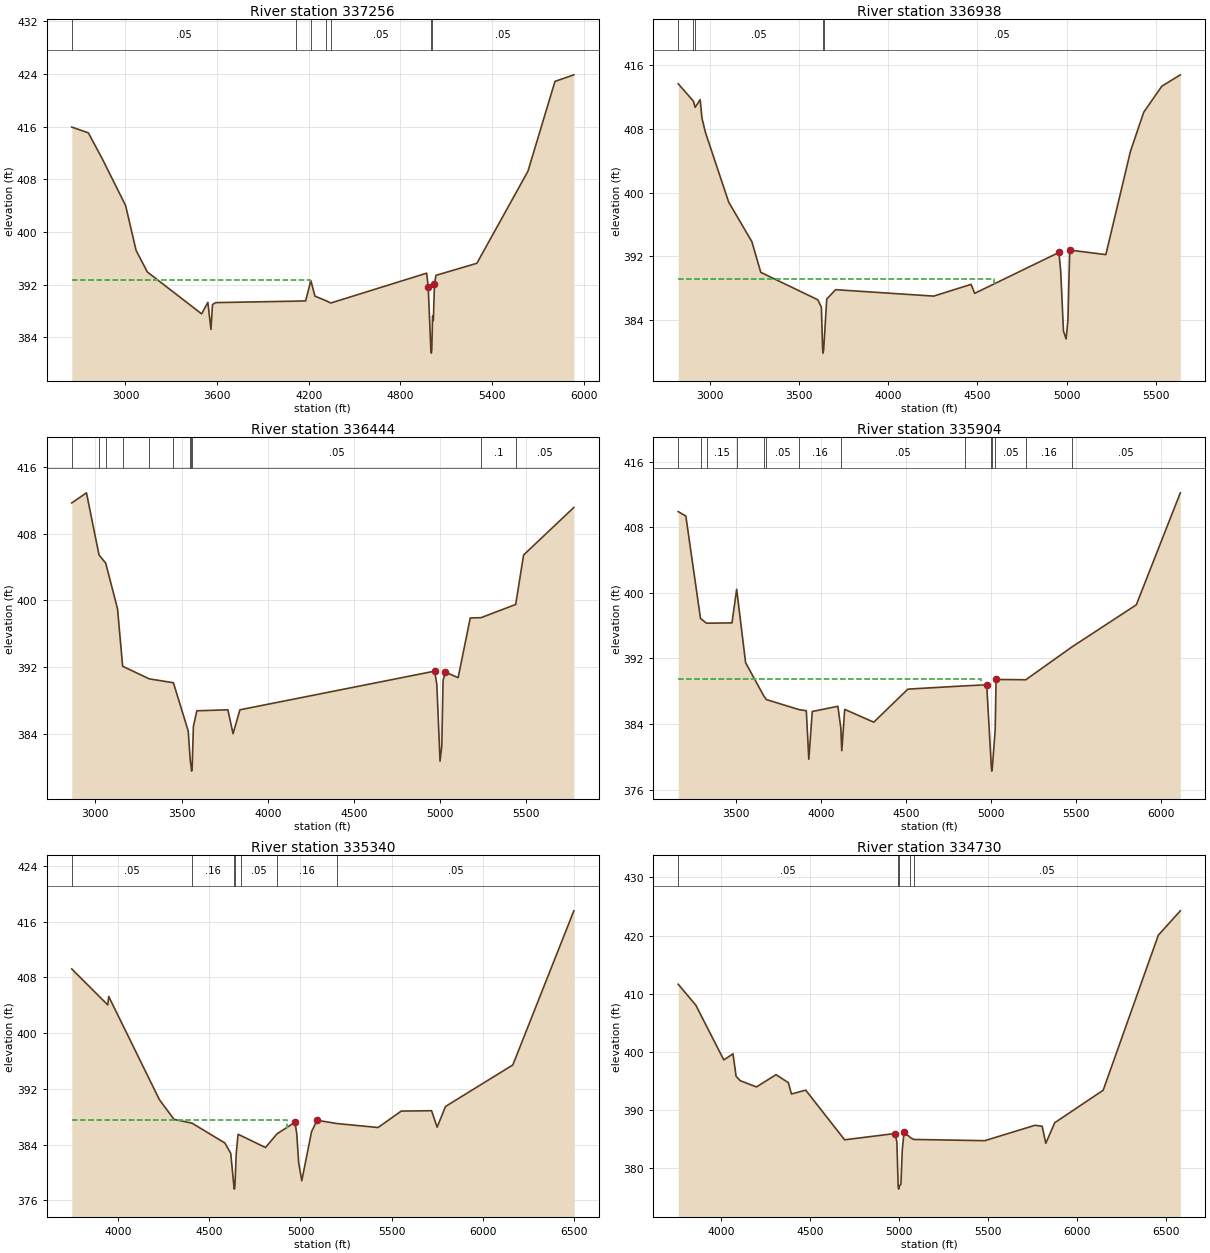
Type RM Length L Ch R = 1 ,337256  ,318,318,318
BEGIN DESCRIPTION:
Mapping XS b4d69acd
END DESCRIPTION:
XS GIS Cut Line= 3
      3586120.33     10584917.13      3586613.38     10582146.34
      3586960.58     10581826.92
#Sta/Elev= 30
  2648.5  415.92  2757.1  415.04  2848.9  411.07  3000.9  404.01  3069.7  397.18
  3143.1  393.92  3498.6  387.56  3539.2  389.31  3559.5   385.2  3569.7  388.98
  3590.6  389.27  4114.4  389.49  4179.1  389.53  4213.3  392.62  4240.1  390.25
  4312.3  389.56  4343.8  389.21  4971.4  393.74  4981.5  391.67  4998.8   382.1
  5001.6   381.6  5004.8   382.1  5010.1  387.24  5015.1  386.56  5022.2  392.05
  5032.3  393.41    5300  395.24  5634.3  409.22    5811  422.85  5934.6  423.85
#Mann= 7 ,-1 , 0
  2648.5     .05       0  4114.4     .08       0  4213.3      .1       0
  4312.3     .08       0  4343.8     .05       0  4998.8     .03       0
  5004.8     .05       0
#XS Ineff= 2 , 0
       0 4207.94  392.67               0
Permanent Ineff=
       T       F
Bank Sta=4981.5,5022.2
XS Rating Curve= 0 ,0
Exp/Cntr=0.3,0.1

Type RM Length L Ch R = 1 ,336938  ,494,494,494
BEGIN DESCRIPTION:
Mapping XS 33e085aa
END DESCRIPTION:
XS GIS Cut Line= 3
      3586766.16     10584903.27      3586780.05     10582958.84
      3586918.93     10582097.75
#Sta/Elev= 30
  2821.4  413.68  2906.6   411.5  2916.2  410.72  2944.5  411.69  2954.5  409.35
  2974.5  407.54  3104.5   398.8  3234.5  393.83  3284.5  389.97  3604.5  386.52
  3624.5  385.59  3631.5  380.31  3634.2  379.81  3637.5  380.31  3654.5  386.61
  3704.5  387.79  4254.5  386.98  4464.5  388.46  4484.5  387.33    4957  392.47
  4967.1  390.14  4982.6  382.58  4997.5   381.6  5007.6  383.97  5017.7  392.77
  5220.3   392.2  5358.4  405.19    5433  410.11  5534.3  413.38  5638.1  414.81
#Mann= 5 ,-1 , 0
  2821.4     .05       0  2906.6     .08       0  2916.2     .05       0
  3631.5     .03       0  3637.5     .05       0
#XS Ineff= 2 , 0
       0 4592.05  389.17               0
Permanent Ineff=
       T       F
Bank Sta=4957,5017.7
XS Rating Curve= 0 ,0
Exp/Cntr=0.3,0.1

Type RM Length L Ch R = 1 ,336444  ,540,540,540
BEGIN DESCRIPTION:
Mapping XS de302722
END DESCRIPTION:
XS GIS Cut Line= 3
       3587085.6     10584875.51      3587064.77     10583417.18
      3587418.93     10582007.47
#Sta/Elev= 30
  2863.2  411.67  2948.5  412.88  3021.2  405.45  3060.1  404.46  3128.6     399
  3158.3  392.12    3313  390.61  3452.7  390.15  3538.6  384.38  3550.9  380.76
  3555.6  380.07  3558.3  379.57  3561.6  380.07  3568.6  384.92  3588.6  386.79
  3768.6  386.91  3798.6  384.05  3838.6  386.91  4968.2  391.54  4980.7  389.92
  4999.1  380.76  5009.4  382.58  5016.6  390.43    5030  391.41  5104.1  390.76
  5174.4   397.9  5237.6  397.94  5437.9  399.52  5483.7  405.44  5775.2  411.13
#Mann= 11 ,-1 , 0
  2863.2     .05       0  3021.2     .08       0  3060.1     .05       0
  3158.3      .1       0    3313     .15       0  3452.7      .1       0
  3550.9     .05       0  3555.6     .03       0  3561.6     .05       0
  5237.6      .1       0  5437.9     .05       0
#XS Ineff= 2 , 0
       0 4892.33  391.22               0
Permanent Ineff=
       T       F
Bank Sta=4968.2,5030
XS Rating Curve= 0 ,0
Exp/Cntr=0.3,0.1

Type RM Length L Ch R = 1 ,335904  ,564,564,564
BEGIN DESCRIPTION:
Mapping XS 7c09373a
END DESCRIPTION:
XS GIS Cut Line= 3
      3587321.71     10584854.67      3587467.55     10583354.68
      3587974.49     10582000.52
#Sta/Elev= 30
  3159.7   409.9  3204.4  409.36  3290.8  396.86  3326.5  396.29  3475.7  396.33
  3503.4  400.42    3556  391.47  3662.2  387.45  3677.7  386.98  3872.4  385.74
  3912.9  385.62  3927.8   379.7  3947.9  385.52  4098.6  386.16  4115.9  383.52
  4121.7  380.74  4138.8  385.78  4309.6  384.22  4510.5  388.25    4846  388.65
    4974  388.78  5001.3  378.75    5004  378.25  5007.3  378.75  5023.9   383.3
  5029.2  389.43  5203.8  389.39  5475.5   393.4  5853.9  398.53  6112.7  412.19
#Mann= 14 ,-1 , 0
  3159.7     .08       0  3290.8      .1       0  3326.5     .15       0
  3503.4     .05       0  3662.2     .08       0  3677.7     .05       0
  3872.4     .16       0  4115.9     .05       0    4846     .16       0
  5001.3     .07       0  5007.3     .16       0  5023.9     .05       0
  5203.8     .16       0  5475.5     .05       0
#XS Ineff= 2 , 0
       0  4942.9  389.47               0
Permanent Ineff=
       T       F
Bank Sta=4974,5029.2
XS Rating Curve= 0 ,0
Exp/Cntr=0.3,0.1

Type RM Length L Ch R = 1 ,335340  ,610,610,610
BEGIN DESCRIPTION:
Mapping XS 5734fc34
END DESCRIPTION:
XS GIS Cut Line= 3
      3587675.88     10584799.14      3587780.05     10583688.01
      3588050.88     10582069.93
#Sta/Elev= 30
  3744.4   409.2  3942.1  404.04  3947.2  405.25  4225.5  390.45  4305.8  387.62
    4405  387.07    4585  384.23  4617.2  382.75  4634.3  378.11    4637  377.61
  4640.3  378.11  4647.3  382.69  4657.3  385.47  4672.4   385.3    4808  383.58
  4871.1  385.54  4969.7   387.2  4979.9  385.54    4990  381.43  5007.2  378.81
    5061  385.86  5091.4  387.49  5199.9  387.02    5426  386.45  5553.6  388.81
    5720  388.86  5750.4   386.5  5796.4  389.47  6166.1  395.43    6501  417.54
#Mann= 7 ,-1 , 0
  3744.4     .05       0    4405     .16       0  4634.3     .07       0
  4640.3     .16       0  4672.4     .05       0  4871.1     .16       0
  5199.9     .05       0
#XS Ineff= 2 , 0
       0 4923.86  387.52               0
Permanent Ineff=
       T       F
Bank Sta=4969.7,5091.4
XS Rating Curve= 0 ,0
Exp/Cntr=0.3,0.1

Type RM Length L Ch R = 1 ,334730  ,414,414,414
BEGIN DESCRIPTION:
UPPER KEECHI CREEK 137.0
END DESCRIPTION:
XS GIS Cut Line= 3
      3587799.59     10584710.22      3588299.61     10583610.19
      3588099.61     10582010.18
#Sta/Elev= 30
  3757.7  411.61  3856.6  408.01  4013.7  398.59  4065.3  399.64  4082.9  395.76
  4105.9  395.02  4197.1  393.94    4307  396.05  4376.2  394.68  4393.7  392.72
  4473.9  393.39  4692.5  384.84  4976.1  385.92  4986.2  384.45  4993.3  376.85
    4996  376.35  4999.3  376.85  5008.9  377.19  5016.4  383.13  5026.5  386.18
  5062.4  385.21  5080.8   384.9    5480  384.69  5762.2  387.34  5802.5  387.16
  5822.7  384.23    5873  387.78  6145.1  393.37    6455  420.06  6578.5  424.25
#Mann= 5 ,-1 , 0
  3757.7     .05       0  4993.3     .03       0  4999.3     .05       0
  5062.4     .16       0  5080.8     .05       0
Bank Sta=4976.1,5026.5
XS Rating Curve= 0 ,0
Exp/Cntr=0.3,0.1

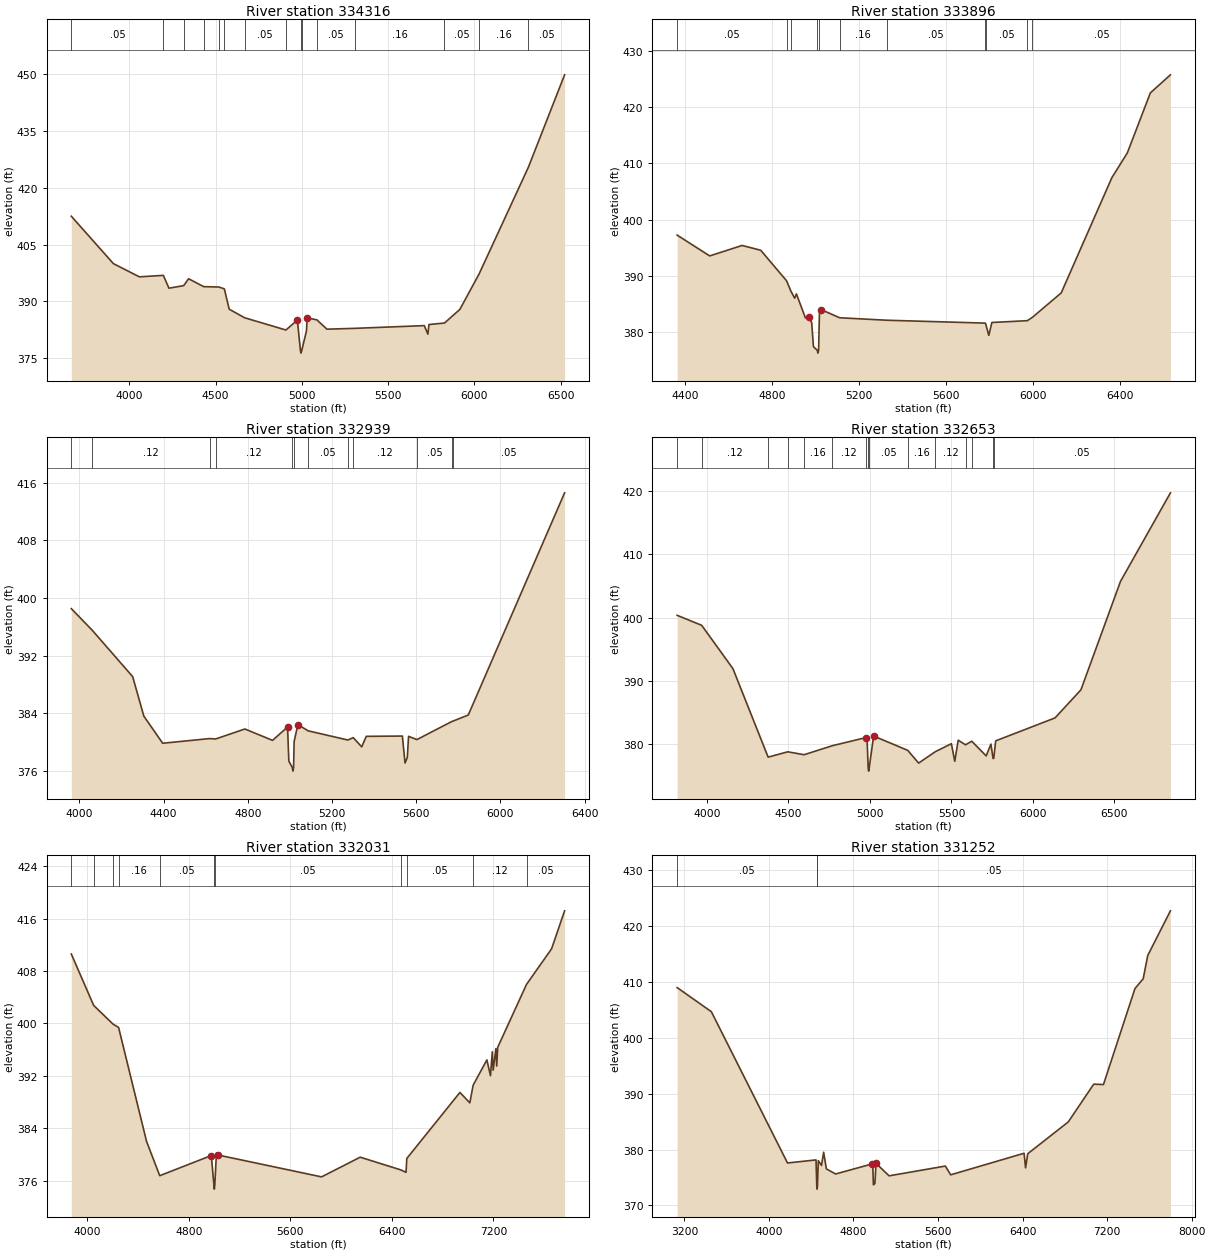
Type RM Length L Ch R = 1 ,334316  ,420,420,420
BEGIN DESCRIPTION:
UPPER KEECHI CREEK 136.0
END DESCRIPTION:
XS GIS Cut Line= 3
      3587849.59     10584760.21      3588649.61     10583660.19
      3589549.63     10582460.17
#Sta/Elev= 30
    3663  412.53  3906.8  400.01  4057.5  396.51  4196.6   396.9  4229.1  393.51
  4314.5  394.19  4343.1  396.01  4430.3  393.92  4518.9  393.82  4550.3  393.33
  4578.4  387.96  4668.2  385.69  4907.3  382.46  4973.7  385.08    4992  376.85
  4994.7  376.35    4998  376.85  5026.3  382.19  5030.5  385.64  5087.2  385.14
    5145  382.68  5306.9   382.9  5709.6  383.62  5730.5  381.36  5736.7  383.91
  5826.7   384.3  5915.9  387.91  6027.4  397.27  6313.2  425.48  6523.2   449.9
#Mann= 15 ,-1 , 0
    3663     .05       0  4196.6     .08       0  4314.5      .1       0
  4430.3     .15       0  4518.9      .1       0  4550.3     .08       0
  4668.2     .05       0  4907.3     .16       0    4992     .07       0
    4998     .16       0  5087.2     .05       0  5306.9     .16       0
  5826.7     .05       0  6027.4     .16       0  6313.2     .05       0
Bank Sta=4973.7,5030.5
XS Rating Curve= 0 ,0
Exp/Cntr=0.3,0.1

Type RM Length L Ch R = 1 ,333896  ,957,957,957
BEGIN DESCRIPTION:
UPPER KEECHI CREEK 135.0
END DESCRIPTION:
XS GIS Cut Line= 3
      3588249.59      10584460.2      3588749.61     10584060.19
       3589849.6      10582860.2
#Sta/Elev= 30
  4365.1  397.24  4514.8  393.54  4663.7   395.4  4749.3  394.55  4868.4  389.11
  4887.4  387.34  4905.4  386.02  4913.4  386.79    4955  382.51  4969.4  382.73
  4983.8  381.65  4991.8   377.4  5009.5  376.75  5012.3  376.25  5015.5  376.75
  5019.3  383.31  5026.7     384  5112.1  382.54    5330   382.1  5781.2  381.59
  5783.7  381.49  5798.1  379.41  5812.3   381.7  5975.3  382.02    5999  382.63
  6131.1  386.96  6364.2  407.47  6435.1  411.86  6541.1  422.54  6633.3  425.75
#Mann= 11 ,-1 , 0
  4365.1     .05       0  4868.4     .16       0  4887.4     .12       0
  5009.5     .07       0  5015.5     .12       0  5112.1     .16       0
    5330     .05       0  5781.2     .16       0  5783.7     .05       0
  5975.3     .16       0    5999     .05       0
Bank Sta=4969.4,5026.7
XS Rating Curve= 0 ,0
Exp/Cntr=0.3,0.1

Type RM Length L Ch R = 1 ,332939  ,286,286,286
BEGIN DESCRIPTION:
UPPER KEECHI CREEK 134.0
END DESCRIPTION:
XS GIS Cut Line= 3
      3588349.61     10584560.19      3589349.61     10584260.19
       3589849.6     10583060.22
#Sta/Elev= 30
  3961.2  398.53  4060.9  395.52  4252.7  389.09  4305.7  383.61  4395.3  379.84
  4618.6  380.49  4646.5  380.43    4786  381.82  4917.4  380.24  4988.7   382.1
  4994.8  377.35  5011.4  376.47  5014.2  375.97  5017.4  376.47  5019.9  380.08
  5037.7  382.43  5086.9  381.56  5275.4  380.29  5300.8  380.62  5341.1  379.34
  5362.7   380.8  5534.4  380.84  5546.9  377.09  5557.7  377.86  5563.7   380.8
  5603.5  380.35    5772   382.9  5772.7  382.89  5847.5  383.76  6305.2  414.61
#Mann= 12 ,-1 , 0
  3961.2     .05       0  4060.9     .12       0  4618.6     .16       0
  4646.5     .12       0  5011.4     .07       0  5017.4     .12       0
  5086.9     .05       0  5275.4     .16       0  5300.8     .12       0
  5603.5     .05       0    5772     .16       0  5772.7     .05       0
Bank Sta=4988.7,5037.7
XS Rating Curve= 0 ,0
Exp/Cntr=0.3,0.1

Type RM Length L Ch R = 1 ,332653  ,622,622,622
BEGIN DESCRIPTION:
UPPER KEECHI CREEK 133.0
END DESCRIPTION:
XS GIS Cut Line= 3
      3588263.52     10584656.76      3589587.34       10584494.
      3590585.11     10583127.49
#Sta/Elev= 30
  3817.3  400.36  3967.9  398.78  4159.5  391.94  4375.4  377.97  4495.7  378.81
  4595.9  378.35  4768.8  379.77  4973.1  381.04  4982.3  380.72  4989.2  376.26
  4991.9  375.76  4995.2  376.26  5022.4   381.3  5231.8  379.04  5298.6  377.03
  5400.9  378.83  5499.4  380.09  5520.3  377.31  5541.2  380.64  5586.3  379.92
  5624.4  380.48    5713  378.16    5742  380.03  5755.1  377.76  5759.3  377.78
  5771.3  380.54  6135.1  384.16  6294.2   388.6  6536.7  405.71  6843.1   419.7
#Mann= 15 ,-1 , 0
  3817.3     .05       0  3967.9     .12       0  4375.4     .16       0
  4495.7     .12       0  4595.9     .16       0  4768.8     .12       0
  4973.1     .05       0  4989.2     .03       0  4995.2     .05       0
  5231.8     .16       0  5400.9     .12       0  5586.3     .05       0
  5624.4     .16       0  5755.1     .12       0  5759.3     .05       0
Bank Sta=4973.1,5022.4
XS Rating Curve= 0 ,0
Exp/Cntr=0.3,0.1

Type RM Length L Ch R = 1 ,332031  ,779,779,779
BEGIN DESCRIPTION:
UPPER KEECHI CREEK 132.0
END DESCRIPTION:
XS GIS Cut Line= 4
      3588035.72     10584917.18      3588860.34     10585069.08
      3589598.19     10584928.03      3591160.71     10583246.14
#Sta/Elev= 30
  3875.5  410.61  4051.5  402.76  4203.3  399.92  4247.9  399.39  4467.9     382
  4571.9  376.75    4978  379.83  4999.2   375.2    5002   374.7  5005.2   375.2
  5018.7  380.24  5028.9  379.92  5846.6  376.57    6151  379.58  6473.7  377.62
  6512.1  377.26  6517.9  379.38  6936.4  389.47  7014.4  387.88  7040.6  390.58
  7148.8  394.44  7177.1  392.03  7191.3  395.68  7198.1  392.87  7219.6  396.17
  7226.4  393.51  7233.8  396.35  7460.9  405.97  7658.4  411.41  7760.9  417.21
#Mann= 11 ,-1 , 0
  3875.5     .05       0  4051.5     .16       0  4203.3     .12       0
  4247.9     .16       0  4571.9     .05       0  4999.2     .03       0
  5005.2     .05       0  6473.7     .16       0  6517.9     .05       0
  7040.6     .12       0  7460.9     .05       0
Bank Sta=4978,5028.9
XS Rating Curve= 0 ,0
Exp/Cntr=0.3,0.1

Type RM Length L Ch R = 1 ,331252  ,420,420,420
BEGIN DESCRIPTION:
Mapping XS 2bde7b68
END DESCRIPTION:
XS GIS Cut Line= 3
      3589185.86      10587293.5      3589760.95     10585036.53
      3591290.86     10583267.91
#Sta/Elev= 30
  3131.5     409  3455.2  404.68  4175.7   377.6  4445.5  378.15  4452.8  373.42
  4455.6  372.92  4458.8  373.42  4467.1  378.02  4497.1  377.16  4517.7  379.52
  4543.7  376.54  4631.2  375.63  4971.8  377.41  4982.1   377.6  4988.3   373.7
  5002.7  373.91  5013.1  377.54  5136.9   375.3  5669.4  377.05  5719.8  375.48
  6414.1  379.34  6428.4  376.73  6449.2  379.26    6832  384.94  7073.3  391.71
  7165.4  391.64  7463.7  408.83  7541.6  410.58  7584.4  414.74  7799.1  422.74
#Mann= 3 ,-1 , 0
  3131.5     .05       0  4452.8     .03       0  4458.8     .05       0
Bank Sta=4971.8,5013.1
XS Rating Curve= 0 ,0
Exp/Cntr=0.3,0.1

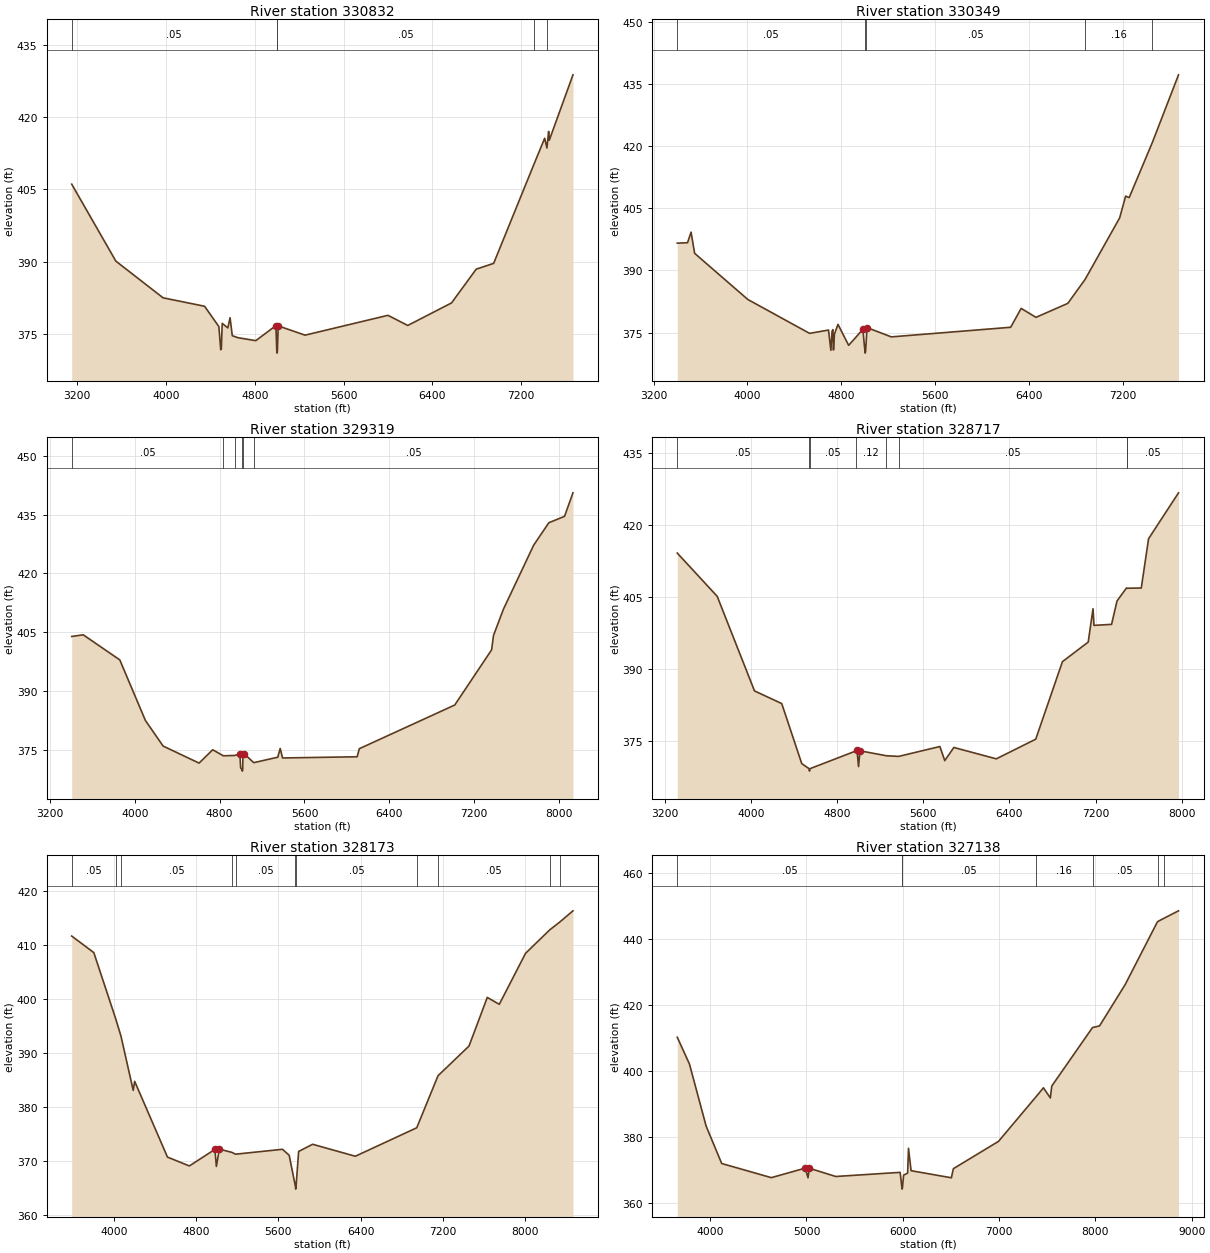
Type RM Length L Ch R = 1 ,330832  ,483,483,483
BEGIN DESCRIPTION:
Mapping XS 6f0a31d7
END DESCRIPTION:
XS GIS Cut Line= 3
      3589815.21     10587304.29      3590119.02     10585047.38
      3591420.84     10583224.84
#Sta/Elev= 30
  3150.1   406.1  3547.8  390.13  3973.4  382.51  4347.4  380.76  4476.1  376.54
    4493  371.74  4498.1  371.86  4506.3  377.21  4556.8  376.26    4577  378.38
  4597.1  374.64  4648.7  374.23    4809  373.62  4990.7  376.75  4997.7  371.53
  5000.5  371.03  5003.7  371.53  5010.8  376.69    5253  374.76    6000  378.88
  6178.2  376.77  6572.7  381.45  6795.1  388.46  6952.4  389.66  7315.3  410.22
  7412.1  415.64  7432.7  413.61  7447.7  417.05  7453.8  415.23  7667.1   428.8
#Mann= 5 ,-1 , 0
  3150.1     .05       0  4997.7     .03       0  5003.7     .05       0
  7315.3     .16       0  7432.7     .05       0
Bank Sta=4990.7,5010.8
XS Rating Curve= 0 ,0
Exp/Cntr=0.3,0.1

Type RM Length L Ch R = 1 ,330349  ,1030,1030,1030
BEGIN DESCRIPTION:
UPPER KEECHI CREEK 131.0
END DESCRIPTION:
XS GIS Cut Line= 3
      3590270.93     10587206.64       3590542.2      10585264.4
      3591540.48     10583181.02
#Sta/Elev= 30
  3402.1  396.59  3489.4  396.69  3519.7  399.25    3550  394.14  4003.2     383
  4529.4  374.82  4690.9  375.62  4711.1  370.73  4721.2  375.33  4728.1  375.72
  4733.2  370.81  4741.4  374.65  4771.7  376.99  4862.6  371.93  4983.8  375.79
    5001  370.55  5003.7  370.05    5007  370.55  5019.1  376.21  5226.1  373.97
  6243.2  376.29  6332.6  380.85  6458.3  378.68  6730.2  382.06  6877.3  387.84
  7171.8  402.68  7222.7  407.94    7253  407.58  7451.1  420.93  7673.4  437.21
#Mann= 5 ,-1 , 0
  3402.1     .05       0    5001     .03       0    5007     .05       0
  6877.3     .16       0  7451.1     .05       0
Bank Sta=4983.8,5019.1
XS Rating Curve= 0 ,0
Exp/Cntr=0.3,0.1

Type RM Length L Ch R = 1 ,329319  ,602,602,602
BEGIN DESCRIPTION:
UPPER KEECHI CREEK 130.0
END DESCRIPTION:
XS GIS Cut Line= 3
      3590487.95     10587510.47       3591421.1     10585459.71
      3591941.94     10583040.01
#Sta/Elev= 30
  3404.4  403.89  3513.1  404.31  3857.9  397.91  4099.4  382.46  4266.3  375.93
  4605.7  371.58  4734.1  374.98  4834.7  373.44  4940.6  373.53  4991.1  373.87
  4997.8  370.32  5011.1  370.03  5013.9  369.53  5017.1  370.03  5019.7  373.54
  5030.7  373.99  5121.4  371.69    5348  373.08    5371  375.31  5393.3  372.89
  6096.8  373.19  6117.3  375.25  7017.5   386.4  7365.2  400.48  7382.8  404.12
  7476.3  410.83  7762.1  427.19    7905  432.91    8053  434.54  8132.6  440.54
#Mann= 6 ,-1 , 0
  3404.4     .05       0  4834.7     .16       0  4940.6     .12       0
  5011.1     .07       0  5017.1     .12       0  5121.4     .05       0
Bank Sta=4991.1,5030.7
XS Rating Curve= 0 ,0
Exp/Cntr=0.3,0.1

Type RM Length L Ch R = 1 ,328717  ,544,544,544
BEGIN DESCRIPTION:
UPPER KEECHI CREEK 129.0
END DESCRIPTION:
XS GIS Cut Line= 3
      3590487.96     10587933.65      3591627.27     10586251.81
      3592777.44     10583897.22
#Sta/Elev= 30
    3318  414.09  3688.5  405.08  4034.8  385.36  4287.6  382.72  4473.3  370.21
  4542.2  369.14    4545  368.64  4548.2  369.14  4974.5  372.83  4985.5  373.04
  5000.5  369.58  5013.2  372.88  5259.6  371.84  5373.1  371.71  5755.4  373.77
  5800.5  370.83    5885  373.57    6279   371.2  6644.9   375.3  6892.6  391.46
  7131.9  395.54  7176.4  402.48  7185.4  399.02  7348.6  399.23  7399.2  404.11
  7487.5  406.83  7491.4  406.76  7624.4  406.81    7692  417.08  7969.9  426.65
#Mann= 8 ,-1 , 0
    3318     .05       0  4542.2     .07       0  4548.2     .05       0
  4974.5     .12       0  5259.6     .16       0  5373.1     .05       0
  7487.5      .1       0  7491.4     .05       0
Bank Sta=4985.5,5013.2
XS Rating Curve= 0 ,0
Exp/Cntr=0.3,0.1

Type RM Length L Ch R = 1 ,328173  ,1035,1035,1035
BEGIN DESCRIPTION:
UPPER KEECHI CREEK 128.0
END DESCRIPTION:
XS GIS Cut Line= 4
      3590618.18     10588031.29      3591583.86     10586837.75
      3592093.85      10586121.6      3593211.49     10583918.88
#Sta/Elev= 30
  3585.7  411.66    3801  408.59  4012.5  396.42  4065.9  393.08  4184.7  383.05
  4199.1  384.71  4518.9  370.66  4731.9  369.02  4980.9  372.09  4995.3  368.93
  5024.1  372.14  5145.9  371.54  5182.3   371.2  5639.6  372.11  5704.8     371
  5765.6  365.22  5768.4  364.72  5771.6  365.22    5797  371.71  5933.4  373.04
  6349.4  370.82  6947.9   376.1  7155.5  385.76  7457.2  391.26  7635.3  400.28
  7752.2     399  8008.2  408.46  8243.2   412.8  8341.1  414.25  8470.2  416.34
#Mann= 11 ,-1 , 0
  3585.7     .05       0  4012.5     .16       0  4065.9     .05       0
  5145.9     .16       0  5182.3     .05       0  5765.6     .03       0
  5771.6     .05       0  6947.9     .16       0  7155.5     .05       0
  8243.2     .08       0  8341.1      .1       0
Bank Sta=4980.9,5024.1
XS Rating Curve= 0 ,0
Exp/Cntr=0.3,0.1

Type RM Length L Ch R = 1 ,327138  ,1118,1118,1118
BEGIN DESCRIPTION:
UPPER KEECHI CREEK 127.0
END DESCRIPTION:
XS GIS Cut Line= 3
      3590899.62     10588010.18      3592049.61     10587360.19
      3594249.62     10584160.17
#Sta/Elev= 30
  3658.8  410.17  3785.1  402.08  3958.3  383.27    4120  371.92  4635.2  367.64
  4987.2  370.52  5016.2   367.6  5029.1   370.5  5303.8  367.99  5972.9  369.24
  5990.9  364.66  5993.6  364.16  5996.9  364.66  6008.8  368.41  6050.7  369.02
  6059.5  376.53  6086.6  369.74  6504.7   367.6  6525.6  370.35  6994.2  378.63
  7379.9  392.01  7460.6  394.85  7532.3  391.78  7547.2  395.39  7970.1   413.1
  8043.1   413.6    8309   426.1    8645  445.17  8708.9  446.16  8863.1  448.46
#Mann= 7 ,-1 , 0
  3658.8     .05       0  5990.9     .03       0  5996.9     .05       0
  7379.9     .16       0  7970.1     .05       0    8645      .1       0
  8708.9     .05       0
Bank Sta=4987.2,5029.1
XS Rating Curve= 0 ,0
Exp/Cntr=0.3,0.1

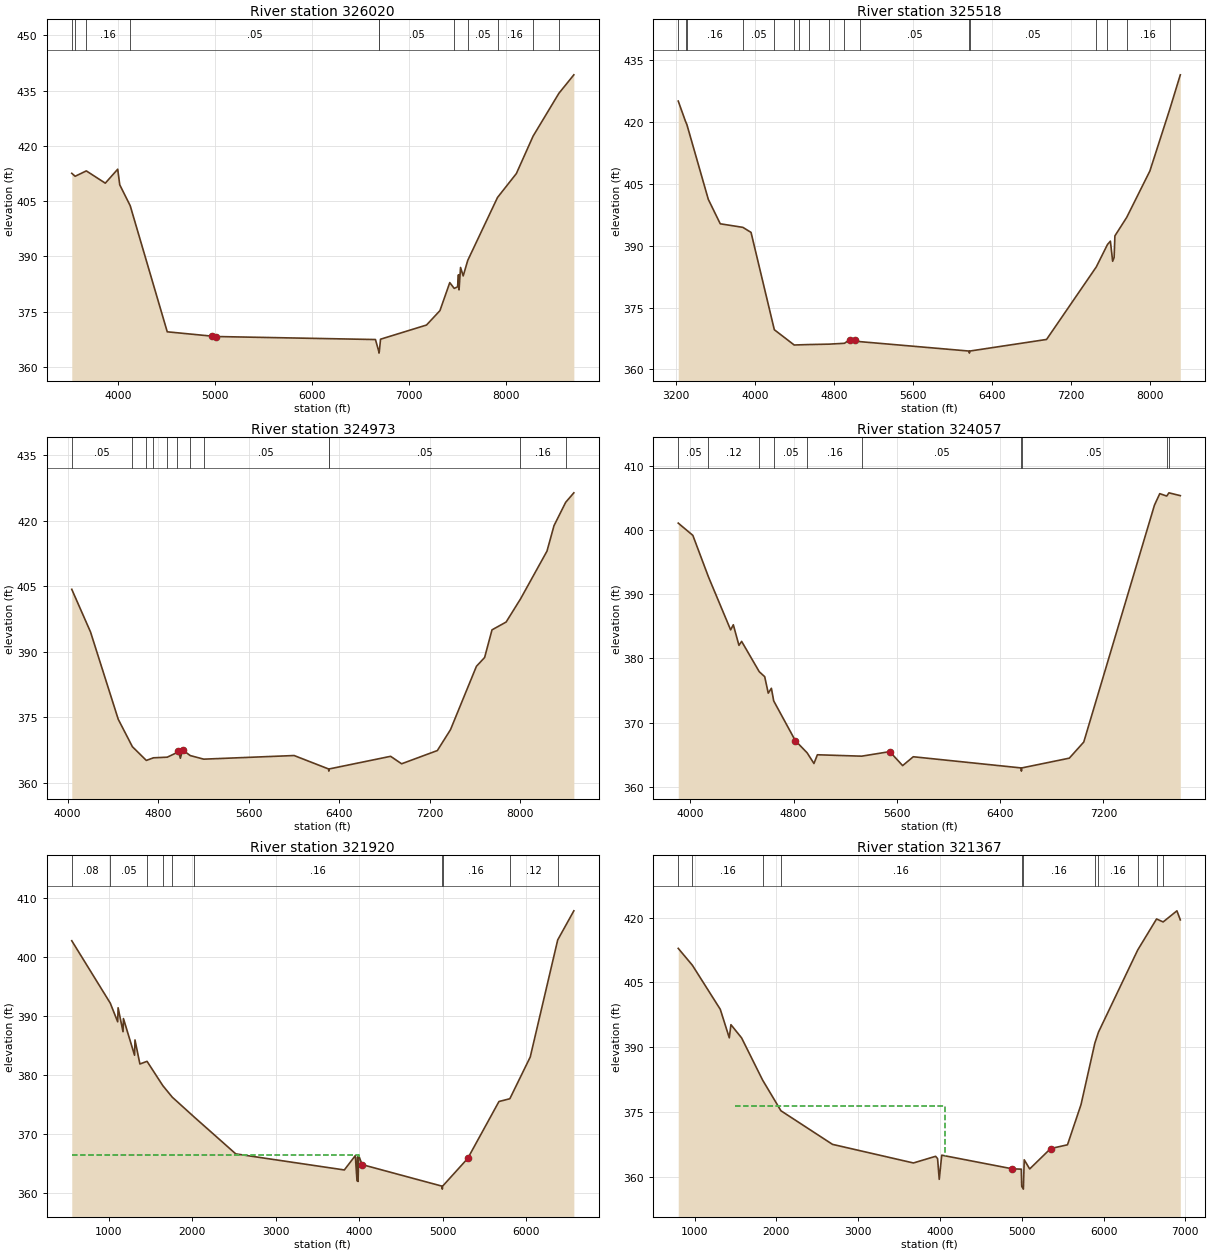
Type RM Length L Ch R = 1 ,326020  ,502,502,502
BEGIN DESCRIPTION:
UPPER KEECHI CREEK 126.0
END DESCRIPTION:
XS GIS Cut Line= 3
      3591312.57      10588921.1      3592399.61     10587960.19
       3594299.6     10584760.21
#Sta/Elev= 30
  3524.3  412.54  3559.3  411.74  3674.1   413.2  3869.7  409.87  3997.7  413.66
  4018.6  409.42  4126.4  403.74    4508   369.5  4968.1  368.32  5010.2  368.22
  6652.8   367.4  6686.8  364.21  6689.6  363.71  6692.8  364.21  6705.4  367.49
  7178.9  371.34  7317.2  375.25  7418.5  382.86  7464.4  381.29  7498.8  381.71
  7508.2     385    7514  380.89  7529.6  386.97    7557  384.68  7603.8   388.9
  7910.3  405.98  8104.4  412.47  8276.8  422.63  8542.4  434.26  8696.7  439.29
#Mann= 11 ,-1 , 0
  3524.3     .16       0  3559.3     .05       0  3674.1     .16       0
  4126.4     .05       0  6686.8     .03       0  6692.8     .05       0
  7464.4     .16       0  7603.8     .05       0  7910.3     .16       0
  8276.8     .05       0  8542.4     .16       0
Bank Sta=4968.1,5010.2
XS Rating Curve= 0 ,0
Exp/Cntr=0.3,0.1

Type RM Length L Ch R = 1 ,325518  ,545,545,545
BEGIN DESCRIPTION:
UPPER KEECHI CREEK 125.0
END DESCRIPTION:
XS GIS Cut Line= 3
      3591453.68     10589214.03      3592799.61     10588060.19
       3594399.6     10585160.21
#Sta/Elev= 30
  3225.2  425.11  3299.1  420.17  3313.3  419.37    3530  401.24  3650.8  395.32
  3879.3  394.46  3962.5  393.24  4198.4  369.61  4399.8   365.9    4449  365.94
  4546.2  366.01  4753.6  366.11    4909  366.32  4962.4  367.22  5011.8  367.08
  5065.1  366.72  6171.4  364.43  6174.1  363.93  6177.4  364.43  6955.5  367.25
  7458.8  384.84  7572.3  390.29    7602  391.11  7624.9  386.23  7639.7  387.13
  7647.7  392.39  7767.2  396.88  8001.8  408.13  8202.3  423.05  8310.1  431.48
#Mann= 17 ,-1 , 0
  3225.2     .16       0  3299.1     .12       0  3313.3     .16       0
  3879.3     .05       0  4198.4     .16       0  4399.8     .05       0
    4449     .12       0  4546.2     .16       0  4753.6     .05       0
    4909     .16       0  5065.1     .05       0  6171.4     .07       0
  6177.4     .05       0  7458.8     .16       0  7572.3     .05       0
  7767.2     .16       0  8202.3     .12       0
Bank Sta=4962.4,5011.8
XS Rating Curve= 0 ,0
Exp/Cntr=0.3,0.1

Type RM Length L Ch R = 1 ,324973  ,916,916,916
BEGIN DESCRIPTION:
UPPER KEECHI CREEK 124.0
END DESCRIPTION:
XS GIS Cut Line= 3
       3592899.6     10589360.21      3593149.61     10588410.19
      3594449.59     10585210.23
#Sta/Elev= 30
  4036.6  404.26  4202.1  394.51  4447.1  374.52  4572.3  368.23  4695.4  365.09
  4758.6  365.69  4880.3  365.83  4966.7  366.89  4977.6  367.35  4996.2  365.59
  5016.4  367.48  5083.4   366.2  5202.7  365.38  6001.2  366.21  6305.2  363.14
  6307.9  362.64  6311.2  363.14  6853.9  366.03    6951  364.32  7266.8  367.35
  7382.8  372.12  7612.2  386.64  7684.4  388.65  7749.8  394.98  7874.5  396.77
  8001.2  402.04  8235.5     413  8297.6  418.83    8401  424.19  8472.9  426.35
#Mann= 12 ,-1 , 0
  4036.6     .05       0  4572.3     .12       0  4695.4     .05       0
  4758.6     .12       0  4880.3     .07       0  4966.7     .05       0
  5083.4     .16       0  5202.7     .05       0  6305.2     .03       0
  6311.2     .05       0  8001.2     .16       0    8401     .12       0
Bank Sta=4977.6,5016.4
XS Rating Curve= 0 ,0
Exp/Cntr=0.3,0.1

Type RM Length L Ch R = 1 ,324057  ,2137,2137,2137
BEGIN DESCRIPTION:
UPPER KEECHI CREEK 123.0
END DESCRIPTION:
XS GIS Cut Line= 3
      3593247.47     10589357.31      3593672.84     10588801.72
       3594444.7     10585705.62
#Sta/Elev= 30
  3905.7  401.09  4018.9  399.18  4140.1   392.7  4311.8  384.45  4332.6  385.25
  4376.2  382.04    4397  382.66  4533.6  377.93  4575.7  377.16  4603.2  374.59
  4627.6  375.35  4645.6  373.38  4813.1  367.19  4904.3   365.3  4957.4  363.63
    4984  364.99  5327.1  364.77  5544.9  365.48  5644.5   363.3  5727.1  364.68
  6562.2  362.94  6564.9  362.44  6568.2  362.94  6936.2  364.46  7048.1  366.97
  7595.8  403.88    7637  405.68  7691.1  405.31    7708  405.81  7796.3  405.37
#Mann= 10 ,-1 , 0
  3905.7     .05       0  4140.1     .12       0  4533.6     .16       0
  4645.6     .05       0  4904.3     .16       0  5327.1     .05       0
  6562.2     .07       0  6568.2     .05       0  7691.1     .16       0
    7708     .05       0
Bank Sta=4813.1,5544.9
XS Rating Curve= 0 ,0
Exp/Cntr=0.3,0.1

Type RM Length L Ch R = 1 ,321920  ,553,553,553
BEGIN DESCRIPTION:
Mapping XS 37335364
END DESCRIPTION:
XS GIS Cut Line= 3
      3594122.93     10591449.26      3594448.45     10589279.15
      3595055.93      10585504.1
#Sta/Elev= 30
   555.2   402.8  1016.5  392.23  1105.6  389.06  1110.6  391.44  1169.6  387.38
  1174.7  389.61  1307.8  383.39  1312.9  385.99  1371.9  381.91  1457.6  382.36
  1646.7  378.24  1759.5  376.29  2020.5  372.95  2521.2  366.67  3822.2  363.95
  3953.8  366.38  3974.1   362.1  3981.7  366.14  3986.8     362  3994.4  366.39
  4034.9  364.86  4994.1   361.2  4996.8   360.7  5000.1   361.2    5301   365.9
  5675.7  375.55  5805.9  376.02  6050.5  383.09  6379.8  402.94  6573.2  407.87
#Mann= 10 ,-1 , 0
   555.2     .08       0  1016.5     .05       0  1457.6     .08       0
  1646.7     .08       0  1759.5     .05       0  2020.5     .16       0
  4994.1     .03       0  5000.1     .16       0  5805.9     .12       0
  6379.8     .05       0
#XS Ineff= 2 , 0
       0 3993.18  366.45               0
Permanent Ineff=
       T       F
Bank Sta=4034.9,5301
XS Rating Curve= 0 ,0
Exp/Cntr=0.3,0.1

Type RM Length L Ch R = 1 ,321367  ,1092,1092,1092
BEGIN DESCRIPTION:
Mapping XS 6f3e561a
END DESCRIPTION:
XS GIS Cut Line= 5
      3594828.22     10591253.98      3594773.97     10590049.55
       3595294.8     10587369.43      3595414.16     10586761.79
      3595674.57     10585199.31
#Sta/Elev= 30
   799.7  412.87   973.2  408.95    1314  398.77  1424.1  392.18  1444.1  395.22
  1574.3  392.17  1830.8  382.43  2055.6  375.31  2686.2  367.54  3675.4  363.24
  3946.8  364.78  3970.8  364.25  3991.2  359.45  4021.7  365.04  4886.4  361.88
  4994.4  361.81  4999.8  357.84  5019.9  357.19  5030.4  363.97  5097.2  361.86
  5353.1  366.57  5559.2  367.44  5724.5  376.72  5893.8  390.94  5938.4   393.5
  6417.7  412.48  6648.7  419.67  6728.8  418.98  6897.5  421.55  6938.9  419.46
#Mann= 11 ,-1 , 0
   799.7     .05       0   973.2     .16       0  1830.8     .08       0
  2055.6     .16       0  4999.8     .05       0  5019.9     .16       0
  5893.8     .12       0  5938.4     .16       0  6417.7     .08       0
  6648.7     .05       0  6728.8     .16       0
#XS Ineff= 1 ,-1
 1495.45 4064.77  376.33
Permanent Ineff=
       T
Bank Sta=4886.4,5353.1
XS Rating Curve= 0 ,0
Exp/Cntr=0.3,0.1

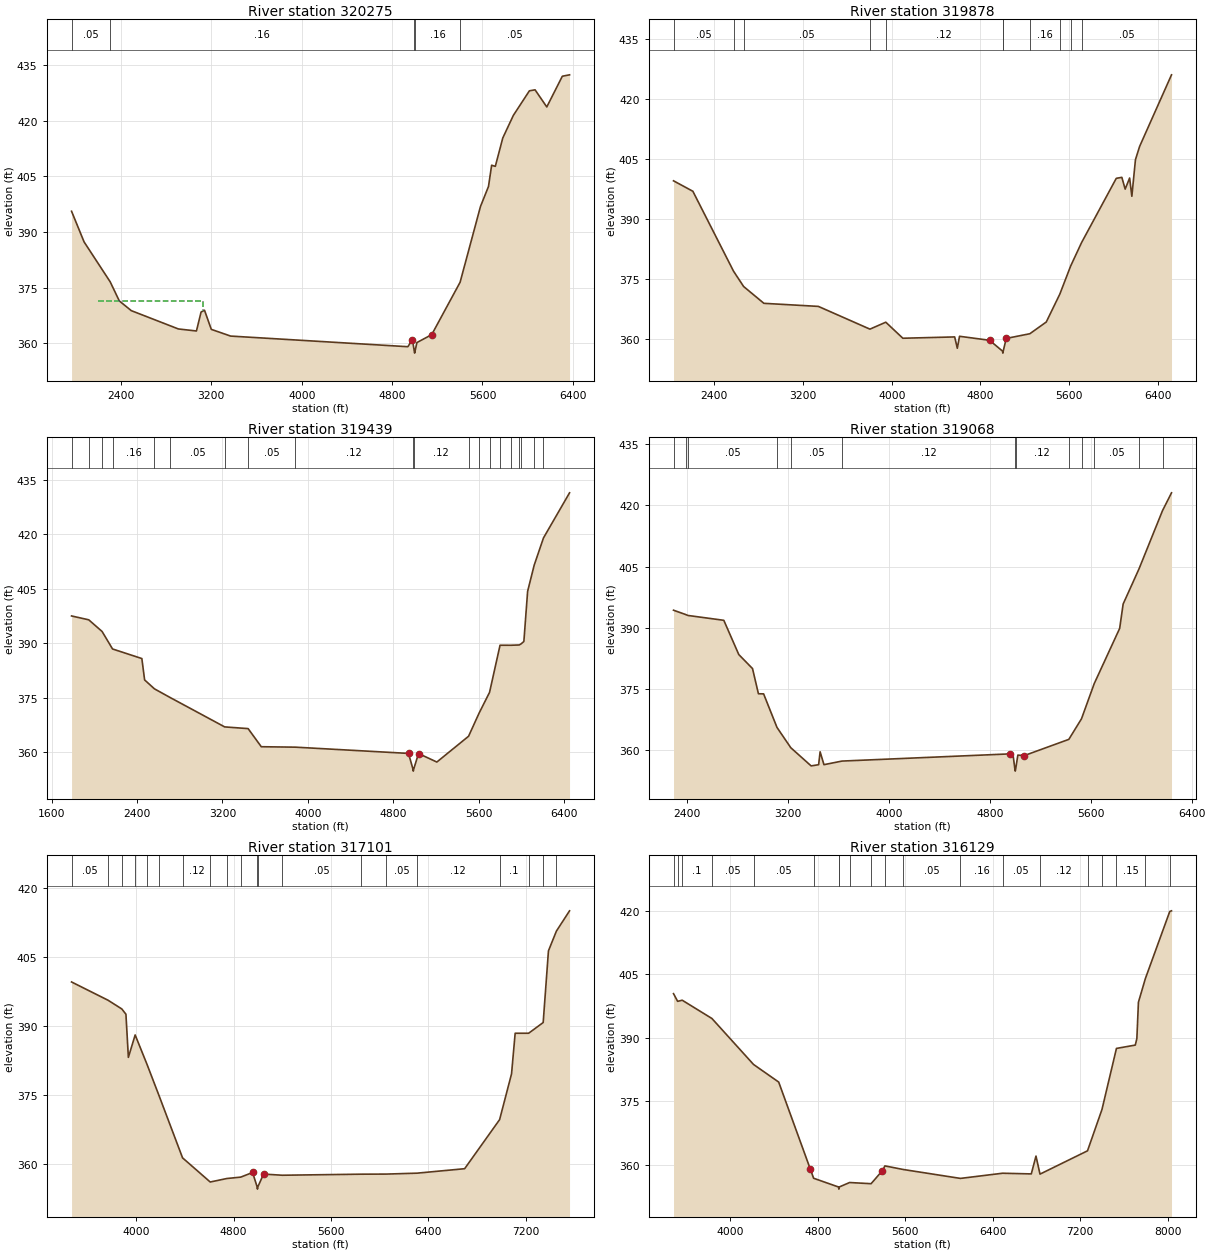
Type RM Length L Ch R = 1 ,320275  ,397,397,397
BEGIN DESCRIPTION:
UPPER KEECHI CREEK 122.0
END DESCRIPTION:
XS GIS Cut Line= 2
      3595869.89     10590060.38      3596325.62      10585676.7
#Sta/Elev= 30
  1963.2   395.6    2074  387.35  2305.2  376.59  2385.7  371.46  2491.8  368.84
  2908.5  363.91  3068.5  363.36  3109.5  368.47  3139.7  368.95    3200   363.8
  3370.9  361.99  4939.3  359.13  4979.6     361  4996.7   357.9  4999.4   357.4
  5002.7   357.9  5019.8  360.25  5150.5  362.37  5401.8  376.48  5582.4   396.9
  5653.2  402.28    5681     408  5713.5  407.69  5779.7  415.34  5873.2  421.42
  6015.1  428.03  6065.4   428.3  6169.1  423.69  6306.7  431.96  6370.5  432.34
#Mann= 5 ,-1 , 0
  1963.2     .05       0  2305.2     .16       0  4996.7     .07       0
  5002.7     .16       0  5401.8     .05       0
#XS Ineff= 1 ,-1
 2193.18 3127.27  371.41
Permanent Ineff=
       F
Bank Sta=4979.6,5150.5
XS Rating Curve= 0 ,0
Exp/Cntr=0.3,0.1

Type RM Length L Ch R = 1 ,319878  ,439,439,439
BEGIN DESCRIPTION:
UPPER KEECHI CREEK 121.0
END DESCRIPTION:
XS GIS Cut Line= 2
      3596293.06     10590092.99      3596596.77     10585613.38
#Sta/Elev= 30
    2033  399.56  2207.4  396.94  2573.9  376.92  2665.2  373.07  2847.7  368.86
  3338.8  368.09  3803.9  362.39  3946.8  364.13  4100.5  360.11  4567.9  360.44
  4591.7   357.6  4611.7   360.6  4882.3   359.6  4999.6  356.88  5002.4  356.38
  5005.6  356.88  5032.7  360.06  5245.6  361.24  5393.5  364.17  5515.5  371.14
  5613.6  378.21  5711.6  384.06  6024.9  400.18  6075.1  400.43  6105.1  397.48
  6145.2  400.26  6165.3  395.69  6197.8  404.86  6235.4  408.18  6522.9  426.12
#Mann= 11 ,-1 , 0
    2033     .05       0  2573.9     .08       0  2665.2     .05       0
  3803.9     .16       0  3946.8     .12       0  4999.6     .07       0
  5005.6     .12       0  5245.6     .16       0  5515.5     .05       0
  5613.6     .16       0  5711.6     .05       0
Bank Sta=4882.3,5032.7
XS Rating Curve= 0 ,0
Exp/Cntr=0.3,0.1

Type RM Length L Ch R = 1 ,319439  ,371,371,371
BEGIN DESCRIPTION:
UPPER KEECHI CREEK 120.0
END DESCRIPTION:
XS GIS Cut Line= 3
      3596661.99     10590342.55      3596922.41     10587098.16
      3596868.15     10585687.62
#Sta/Elev= 30
  1786.4  397.54  1947.4  396.48  2072.4  393.27  2170.5  388.46    2445  385.83
    2471  379.95  2562.9   377.5  2712.1  375.08  3221.3  367.03  3440.9  366.56
  3564.2  361.58  3883.6  361.46  4943.8  359.74    4986  355.37  4988.8  354.87
    4992  355.37  5037.7  359.71  5209.3  357.37  5506.6  364.46  5604.9   370.8
  5703.2  376.53  5801.5  389.49  5899.8  389.48  5981.3  389.56  5998.1  389.85
  6024.8  390.52  6059.9  404.31  6121.2  411.48  6208.4  418.99  6452.8   431.4
#Mann= 20 ,-1 , 0
  1786.4      .1       0  1947.4     .05       0  2072.4     .07       0
  2170.5     .16       0  2562.9     .05       0  2712.1     .05       0
  3221.3      .1       0  3440.9     .05       0  3883.6     .12       0
    4986     .07       0    4992     .12       0  5506.6     .07       0
  5604.9     .12       0  5703.2     .05       0  5801.5      .1       0
  5899.8     .15       0  5981.3      .1       0  5998.1     .05       0
  6121.2     .16       0  6208.4     .05       0
Bank Sta=4943.8,5037.7
XS Rating Curve= 0 ,0
Exp/Cntr=0.3,0.1

Type RM Length L Ch R = 1 ,319068  ,1967,1967,1967
BEGIN DESCRIPTION:
UPPER KEECHI CREEK 119.0
END DESCRIPTION:
XS GIS Cut Line= 2
      3597752.69     10589721.83      3597006.52     10585843.46
#Sta/Elev= 30
  2290.7  394.32  2388.1  393.25  2404.1  393.04  2689.5  391.85  2808.3  383.47
  2917.2  380.04    2964  373.88  3005.2  373.85  3111.1  365.65  3220.6  360.68
    3382  356.23  3441.5  356.52  3453.3  359.68  3483.8  356.53  3627.2  357.41
  4960.4  359.17  4982.9  359.03  4998.2  355.45  5000.9  354.95  5004.2  355.45
  5021.5  358.87  5072.4  358.75  5425.8  362.72  5526.4  367.76  5627.1  376.35
    5829  389.87  5856.6  395.83  5982.4  404.43  6168.8  418.68  6240.2  423.04
#Mann= 13 ,-1 , 0
  2290.7     .05       0  2388.1      .1       0  2404.1     .05       0
  3111.1     .12       0  3220.6     .05       0  3627.2     .12       0
  4998.2     .07       0  5004.2     .12       0  5425.8     .05       0
  5526.4      .1       0  5627.1     .05       0  5982.4     .16       0
  6168.8     .05       0
Bank Sta=4960.4,5072.4
XS Rating Curve= 0 ,0
Exp/Cntr=0.3,0.1

Type RM Length L Ch R = 1 ,317101  ,972,972,972
BEGIN DESCRIPTION:
Mapping XS e9f8d39b
END DESCRIPTION:
XS GIS Cut Line= 3
      3598221.45      10589756.6      3598178.05     10587621.17
      3597128.74     10585973.49
#Sta/Elev= 30
  3470.2  399.48  3769.7  395.51    3883  393.61  3916.7  392.46  3936.7  383.08
  3992.4  387.96  4090.6  381.51  4188.8  374.74  4381.7  361.23  4608.7  355.98
  4745.9  356.74  4859.2  357.04  4956.9  358.05  4993.9  354.93  4996.7  354.43
  4999.9  354.93  5046.9   357.7  5201.1  357.45  5850.4  357.68  6053.7   357.7
  6306.4   357.9    6698  358.87  6985.2  369.54  7083.2   379.5  7112.9  388.33
  7223.8  388.33    7343  390.66  7386.3  406.25  7451.6  410.54  7559.5  414.95
#Mann= 20 ,-1 , 0
  3470.2     .05       0  3769.7     .16       0    3883     .05       0
  3992.4     .08       0  4090.6      .1       0  4188.8     .05       0
  4381.7     .12       0  4608.7     .05       0  4745.9     .05       0
  4859.2     .12       0  4993.9     .07       0  4999.9     .12       0
  5201.1     .05       0  5850.4     .16       0  6053.7     .05       0
  6306.4     .12       0  6985.2      .1       0  7223.8     .15       0
    7343      .1       0  7451.6     .16       0
Bank Sta=4956.9,5046.9
XS Rating Curve= 0 ,0
Exp/Cntr=0.3,0.1

Type RM Length L Ch R = 1 ,316129  ,1115,1115,1115
BEGIN DESCRIPTION:
UPPER KEECHI CREEK 118.0
END DESCRIPTION:
XS GIS Cut Line= 3
      3598941.94     10589791.32      3598881.17     10587968.39
      3597127.72      10585876.4
#Sta/Elev= 30
    3481  400.43  3518.8  398.62  3560.4  398.89  3832.3  394.57  4212.5  383.73
  4442.7  379.57  4732.8  358.96  4761.9  356.88    4990  354.81  4992.7  354.31
    4996  354.81  5091.1  355.87  5287.6  355.59  5390.2  358.65  5413.9  359.79
  5582.4  358.94  6104.2  356.84  6489.4  358.06  6752.4   357.9  6795.3  362.11
  6832.1  357.85  7266.5  363.35  7398.8  373.11  7531.1  387.51  7703.5   388.3
  7717.8  389.85  7732.1  398.41  7795.8  404.01  8018.8  419.84  8034.6  419.98
#Mann= 20 ,-1 , 0
    3481     .05       0  3518.8     .08       0  3560.4      .1       0
  3832.3     .05       0  4212.5     .05       0  4761.9     .12       0
    4990     .07       0    4996     .05       0  5091.1     .05       0
  5287.6     .08       0  5413.9      .1       0  5582.4     .05       0
  6104.2     .16       0  6489.4     .05       0  6832.1     .12       0
  7266.5     .05       0  7398.8      .1       0  7531.1     .15       0
  7795.8     .16       0  8018.8     .05       0
Bank Sta=4732.8,5390.2
XS Rating Curve= 0 ,0
Exp/Cntr=0.3,0.1