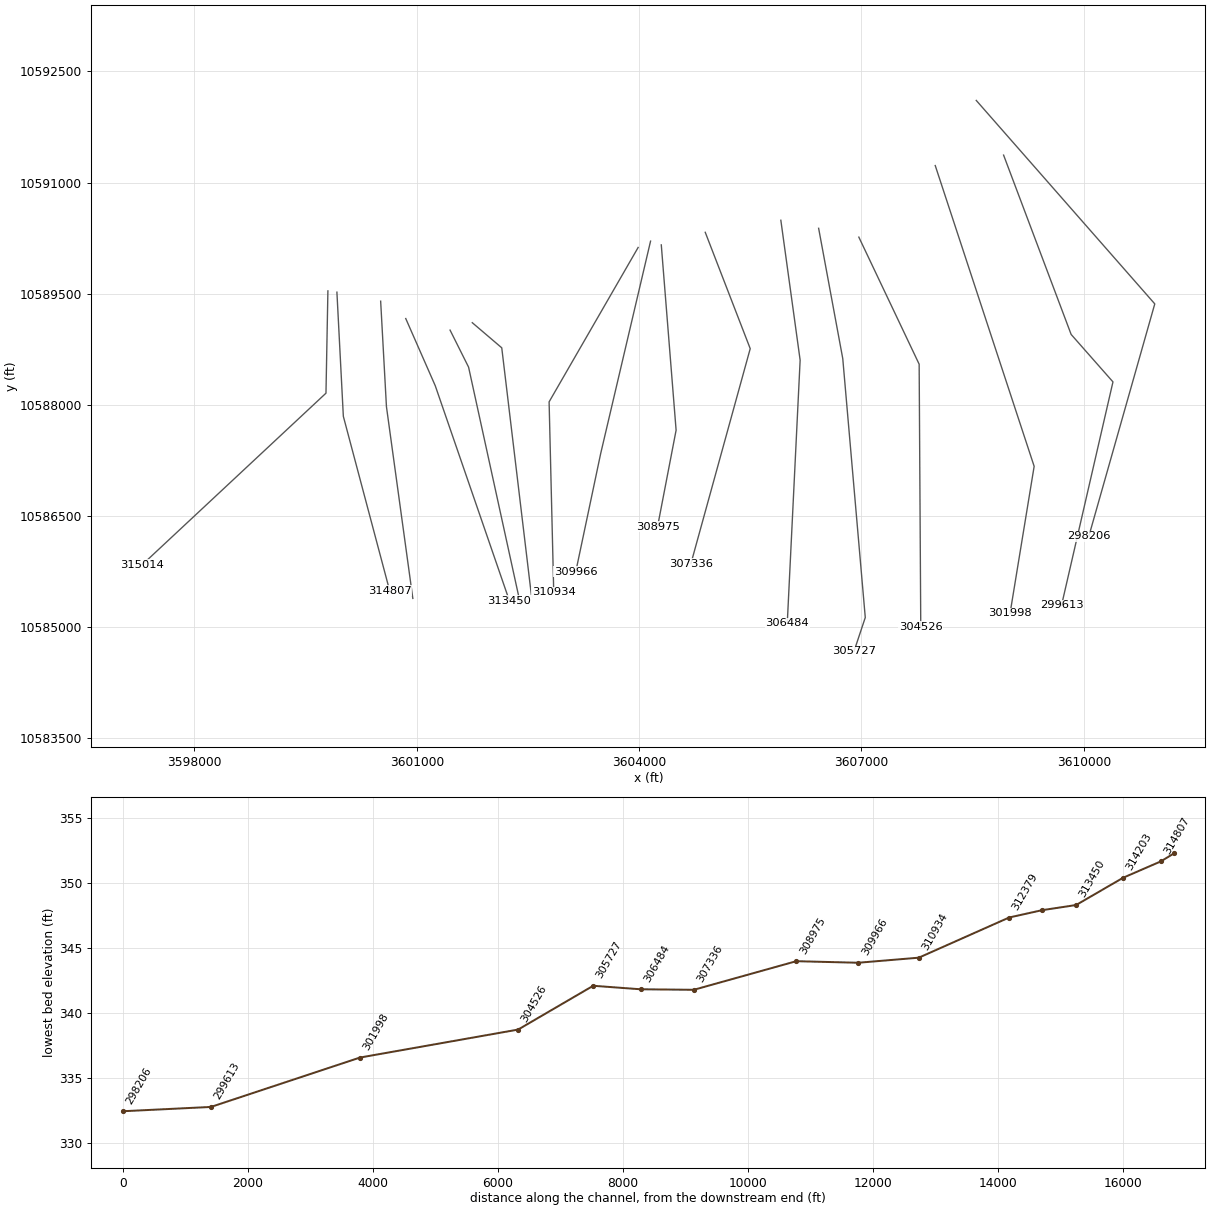
HEC-RAS study UPPER KEECHI CREEK.prj: UPPER KEECHI CREEK Base Level Engineering

--- UPPER KEECHI CREEK.g01 (geometry) --- (continued)

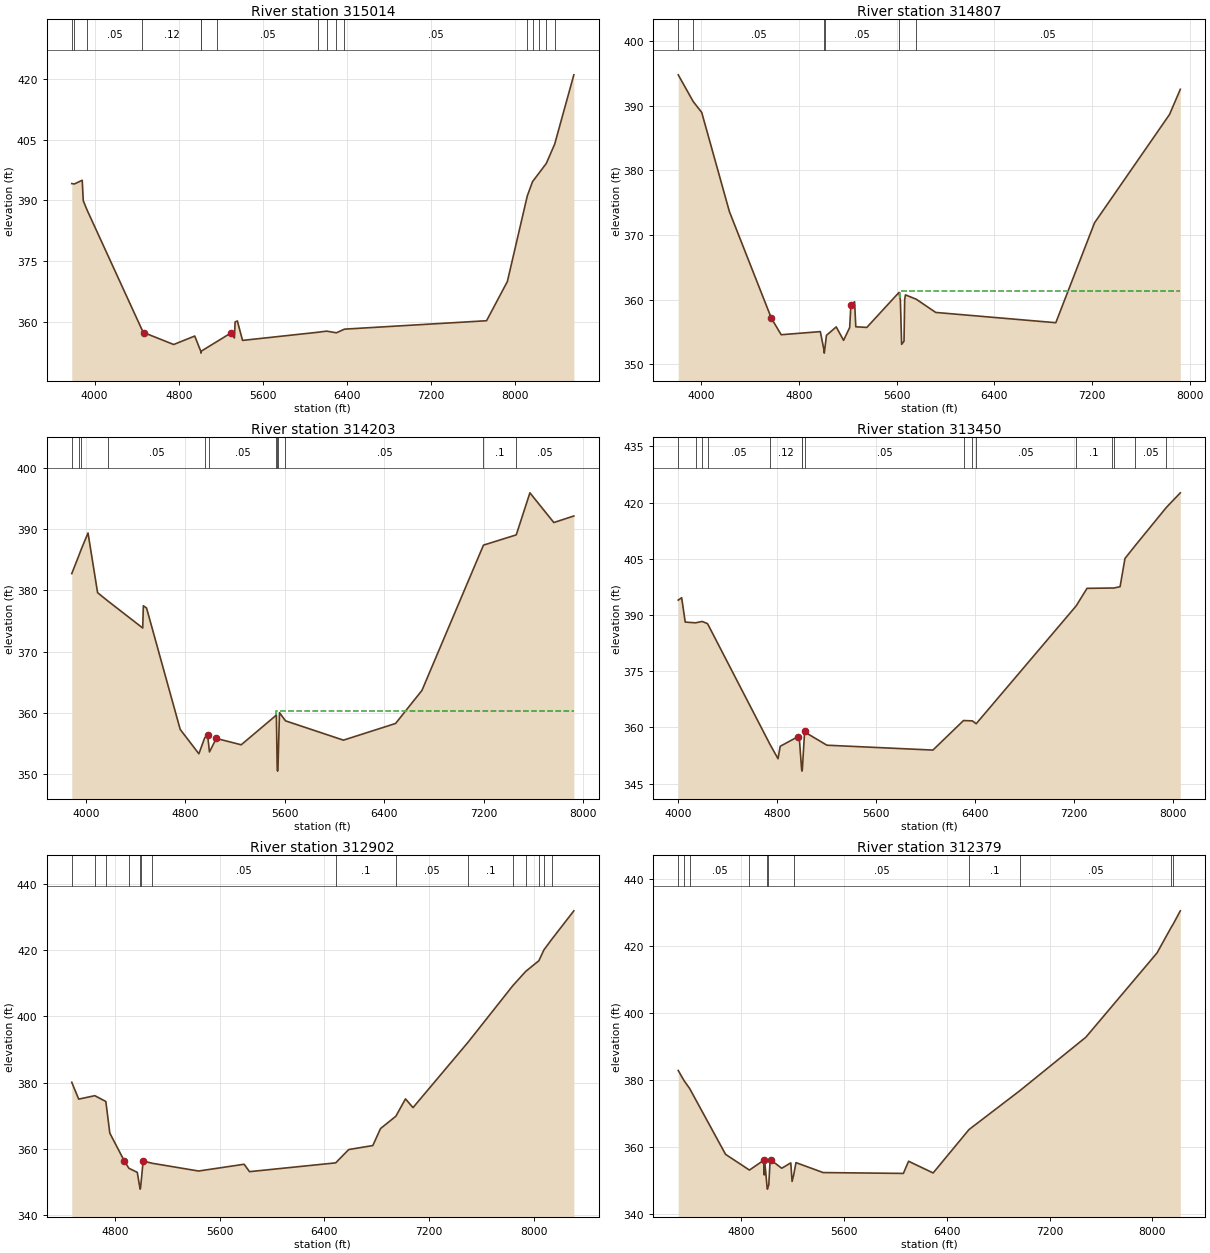
Type RM Length L Ch R = 1 ,315014  ,207,207,207
BEGIN DESCRIPTION:
UPPER KEECHI CREEK 117.0
END DESCRIPTION:
XS GIS Cut Line= 3
      3599801.31     10589539.55      3599775.27     10588159.36
      3597293.65     10585842.61
#Sta/Elev= 30
  3782.5  394.17  3807.1  394.07  3881.9  394.99  3891.9  389.93  3927.3  387.69
    4455  357.82    4472  357.33    4752  354.44  4952.1  356.53  5009.1  352.81
  5011.8  352.31  5015.1  352.81  5161.6  355.14  5293.8  357.25  5329.1  356.06
    5336  359.98  5357.5  360.26  5406.8  355.45  6125.1  357.47  6207.4  357.74
  6299.3  357.33  6376.4  358.23  7727.8  360.31  7925.6  369.99  8115.3  391.14
  8165.4  394.67  8225.5  396.72    8296  399.15  8375.5   403.9  8557.9  421.02
#Mann= 16 ,-1 , 0
  3782.5     .15       0  3807.1      .1       0  3927.3     .05       0
    4455     .12       0  5009.1     .07       0  5015.1     .12       0
  5161.6     .05       0  6125.1     .16       0  6207.4     .05       0
  6299.3      .1       0  6376.4     .05       0  8115.3     .16       0
  8165.4     .08       0  8225.5     .16       0    8296     .08       0
  8375.5     .16       0
Bank Sta=4472,5293.8
XS Rating Curve= 0 ,0
Exp/Cntr=0.3,0.1

Type RM Length L Ch R = 1 ,314807  ,604,604,604
BEGIN DESCRIPTION:
UPPER KEECHI CREEK 116.0
END DESCRIPTION:
XS GIS Cut Line= 3
      3599922.84      10589522.2      3600009.65     10587846.86
      3600634.54     10585494.84
#Sta/Elev= 30
  3812.4  394.79  3934.8  390.66  4004.7  388.97  4231.5  373.61  4575.4  357.09
  4655.5  354.55    4976  355.03  5005.6   352.2  5008.3   351.7  5011.6   352.2
    5026  354.45  5106.1  355.76  5166.2  353.68  5216.3  355.66  5226.3  359.21
  5256.3  359.65  5266.4  355.78  5356.5  355.68  5620.1   361.1  5631.4  359.94
  5641.7  353.06  5661.2  353.55  5666.4  359.95  5672.8  360.72  5761.1  360.05
  5921.1     358  6904.1  356.41  7221.3  371.88  7835.3  388.65  7923.6  392.55
#Mann= 6 ,-1 , 0
  3812.4      .1       0  3934.8     .05       0  5005.6     .03       0
  5011.6     .05       0  5620.1     .16       0  5761.1     .05       0
#XS Ineff= 2 , 0
       0                 5627.84       0  361.26
Permanent Ineff=
       F       T
Bank Sta=4575.4,5226.3
XS Rating Curve= 0 ,0
Exp/Cntr=0.3,0.1

Type RM Length L Ch R = 1 ,314203  ,753,753,753
BEGIN DESCRIPTION:
UPPER KEECHI CREEK 115.0
END DESCRIPTION:
XS GIS Cut Line= 3
      3600513.12     10589400.66      3600591.24     10587977.07
      3600947.15     10585390.27
#Sta/Elev= 30
    3888  382.76  3949.9  385.97  3963.9  386.73  4018.7  389.41  4095.7  379.64
  4181.6  378.23  4458.5  373.86  4463.5   377.5  4489.4  377.13  4759.8  357.27
    4910  353.28  4956.9   355.9  4980.1  356.37  4995.1  353.58  5050.2  355.79
  5250.5  354.75  5533.2  359.61  5539.8  350.94  5542.5  350.44  5545.8  350.94
  5558.2  360.01  5606.4  358.67  6072.4  355.51  6491.6  358.24  6703.6  363.65
  7198.2  387.42  7461.8   389.1  7571.7  395.98    7764  391.12  7924.9  392.19
#Mann= 12 ,-1 , 0
    3888     .05       0  3949.9     .08       0  3963.9      .1       0
  4181.6     .05       0  4956.9     .12       0  4995.1     .05       0
  5533.2     .07       0  5539.8     .03       0  5545.8     .07       0
  5606.4     .05       0  7198.2      .1       0  7461.8     .05       0
#XS Ineff= 2 , 0
       0                 5531.25       0   360.2
Permanent Ineff=
       F       T
Bank Sta=4980.1,5050.2
XS Rating Curve= 0 ,0
Exp/Cntr=0.3,0.1

Type RM Length L Ch R = 1 ,313450  ,548,548,548
BEGIN DESCRIPTION:
UPPER KEECHI CREEK 114.0
END DESCRIPTION:
XS GIS Cut Line= 3
      3600851.64     10589166.35      3601249.61     10588260.19
      3602249.62     10585360.16
#Sta/Elev= 30
  4002.8  393.99  4030.5  394.64  4059.3  388.13  4142.6  387.93  4196.4   388.3
  4239.8   387.7  4744.1   355.5  4809.1  351.65    4827  354.98  4970.7  357.54
  4983.6  356.12  4999.8  348.84  5002.6  348.34  5005.8  348.84  5024.2  359.03
  5028.9   358.7  5204.1  355.26  6060.9  353.96  6308.2  361.85  6379.8  361.75
  6410.5  360.99    7219  392.47  7306.1  397.13  7504.7  397.22  7521.2   397.2
  7573.5  397.58  7612.9  405.11  7697.5  408.62    7946  418.68  8060.1  422.63
#Mann= 16 ,-1 , 0
  4002.8     .05       0  4142.6     .08       0  4196.4      .1       0
  4239.8     .05       0  4744.1     .12       0  4999.8     .07       0
  5005.8     .12       0  5028.9     .05       0  6308.2     .08       0
  6379.8      .1       0  6410.5     .05       0    7219      .1       0
  7504.7     .15       0  7521.2      .1       0  7697.5     .05       0
    7946     .12       0
Bank Sta=4970.7,5024.2
XS Rating Curve= 0 ,0
Exp/Cntr=0.3,0.1

Type RM Length L Ch R = 1 ,312902  ,523,523,523
BEGIN DESCRIPTION:
UPPER KEECHI CREEK 113.0
END DESCRIPTION:
XS GIS Cut Line= 3
       3601449.6     10589010.21      3601699.61     10588510.19
      3602399.61      10585310.2
#Sta/Elev= 30
  4471.3  380.15  4524.4  375.08  4647.3  376.12  4731.5  374.37    4762  364.82
  4873.8  356.35  4907.9  354.22  4971.6  353.01    4991  348.44  4993.8  347.94
    4997  348.44  5016.4  356.41  5085.6  355.74  5439.8   353.4  5787.8  355.44
  5828.8  353.21  6486.9  355.86  6586.3  359.87  6770.5  361.08  6829.4   366.2
  6946.5  369.92  7020.2  375.15  7077.6  372.52  7498.3  392.25  7839.8  409.29
  7939.3  413.63  8038.9  416.81  8077.5  420.09  8138.4  423.33    8306  431.86
#Mann= 15 ,-1 , 0
  4471.3     .05       0  4647.3      .1       0  4731.5     .05       0
  4907.9     .12       0    4991     .07       0    4997     .12       0
  5085.6     .05       0  6486.9      .1       0  6946.5     .05       0
  7498.3      .1       0  7839.8     .08       0  7939.3      .1       0
  8038.9     .08       0  8077.5     .05       0  8138.4     .12       0
Bank Sta=4873.8,5016.4
XS Rating Curve= 0 ,0
Exp/Cntr=0.3,0.1

Type RM Length L Ch R = 1 ,312379  ,1445,1445,1445
BEGIN DESCRIPTION:
UPPER KEECHI CREEK 112.0
END DESCRIPTION:
XS GIS Cut Line= 3
      3601749.61     10589110.19      3602147.09     10588771.34
      3602549.61     10585410.17
#Sta/Elev= 30
  4309.5  382.78  4355.6  379.71  4398.3  377.41  4677.9  357.76  4863.6  353.07
    4974  355.97  4979.1   351.6  4984.1  355.13  5001.2  347.88  5003.9  347.38
  5007.2  347.88  5014.3  348.66  5024.3  355.77  5034.4  355.96    5115  353.61
  5185.5  355.22  5195.5  349.68  5207.9  351.57  5225.8  355.29  5437.3  352.32
  6061.7  352.07    6102   355.7  6293.3  352.21  6572.6  365.16  6965.9  376.69
  7481.8  392.71  8035.7  417.86  8145.8  425.48  8162.1  426.51    8217  430.43
#Mann= 11 ,-1 , 0
  4309.5     .05       0  4355.6      .1       0  4398.3     .05       0
  4863.6     .12       0  5001.2     .07       0  5007.2     .12       0
  5207.9     .05       0  6572.6      .1       0  6965.9     .05       0
  8145.8     .12       0  8162.1     .16       0
Bank Sta=4974,5034.4
XS Rating Curve= 0 ,0
Exp/Cntr=0.3,0.1

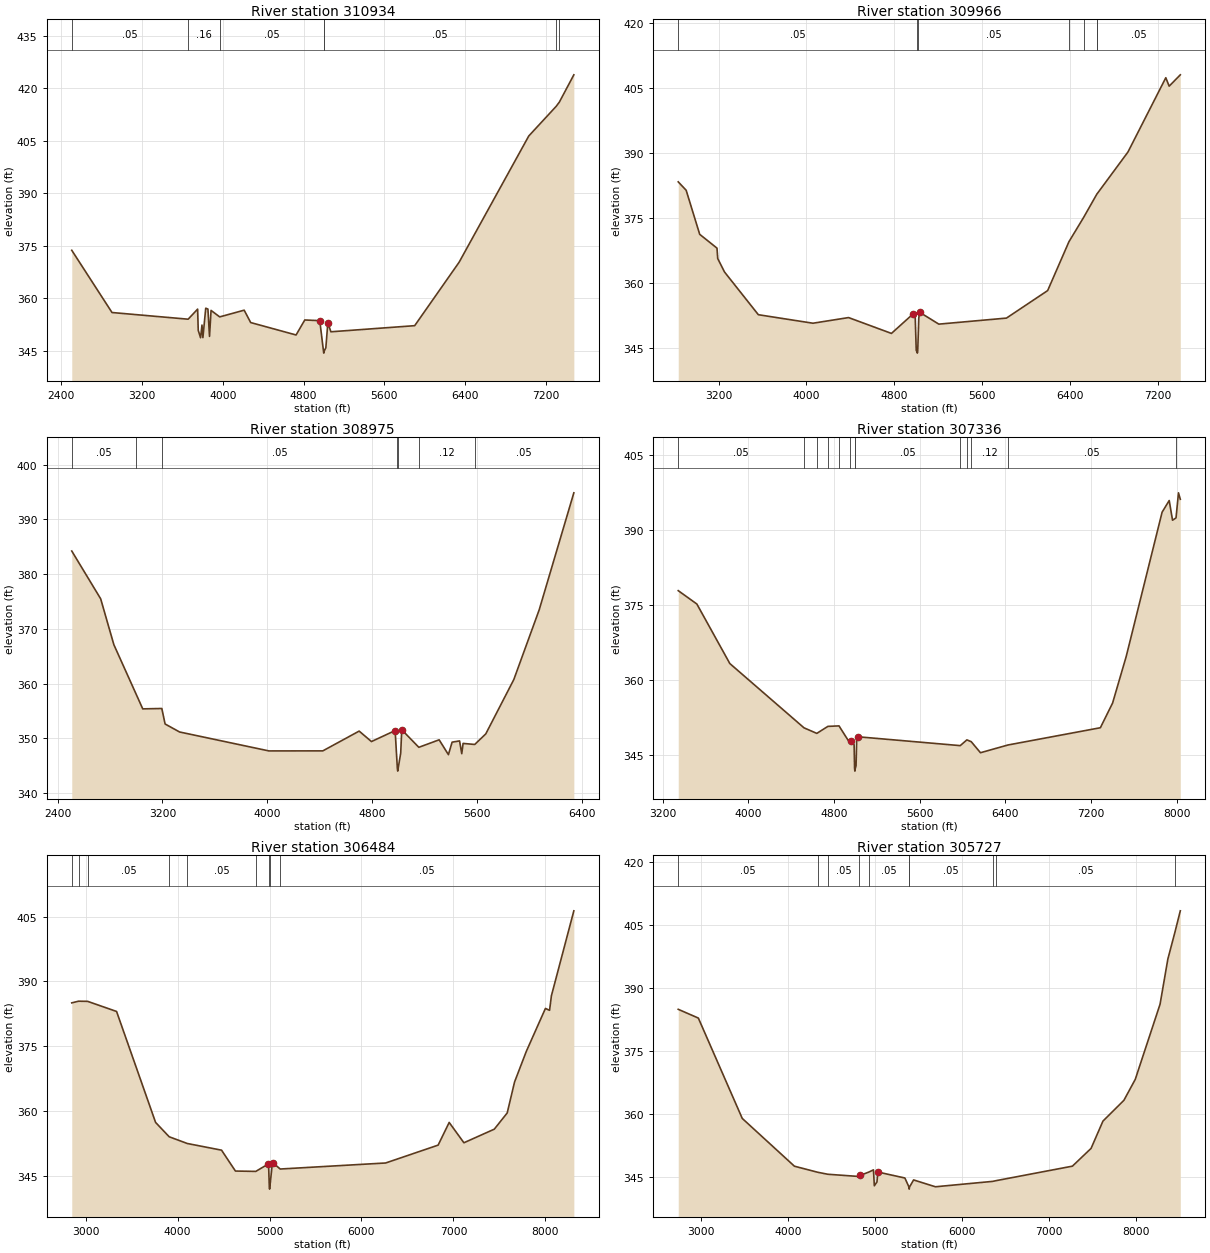
Type RM Length L Ch R = 1 ,310934  ,968,968,968
BEGIN DESCRIPTION:
Mapping XS c2178a74
END DESCRIPTION:
XS GIS Cut Line= 3
      3603987.34     10590125.47      3602785.98     10588042.18
      3602848.45       10585474.
#Sta/Elev= 30
  2503.4  373.69    2902   355.9  3656.3  353.99  3750.2  356.87  3756.2  350.81
  3779.3  348.69  3793.3  352.32  3802.4  348.72  3830.6  357.13  3852.2  356.89
    3868  349.08  3883.2   356.5    3969  354.65  4211.3  356.57  4275.9  353.03
  4725.5  349.48  4811.7  353.77  4960.3  353.57  4997.3  344.79    5000  344.29
  5003.3  344.79  5020.3  345.82  5040.3  352.97  5070.3  350.39  5900.5  352.14
  6340.7  370.28  7030.9  406.38  7301.9  414.84  7333.6  416.06  7477.2  423.86
#Mann= 7 ,-1 , 0
  2503.4     .05       0  3656.3     .16       0    3969     .05       0
  4997.3     .03       0  5003.3     .05       0  7301.9     .08       0
  7333.6     .05       0
Bank Sta=4960.3,5040.3
XS Rating Curve= 0 ,0
Exp/Cntr=0.3,0.1

Type RM Length L Ch R = 1 ,309966  ,991,991,991
BEGIN DESCRIPTION:
Mapping XS 20d9022b
END DESCRIPTION:
XS GIS Cut Line= 3
       3604154.9     10590210.58      3603482.16     10587345.99
      3603145.78      10585750.9
#Sta/Elev= 30
  2832.1  383.36  2904.4  381.42  3027.7  371.27  3185.1  368.09    3192  365.68
  3253.7  362.59  3561.8  352.75    4059  350.79  4383.6  352.09  4773.9  348.44
  4969.1  352.89  4989.6   352.8  4999.9  344.47  5007.2   344.4  5009.9   343.9
  5013.2   344.4    5023  351.99  5030.7  353.31  5205.4  350.58  5821.4  351.97
  6196.7  358.31  6390.6  369.57  6525.1   375.2  6646.5  380.62  6647.9  380.65
  6648.6  380.66  6928.1  390.24  7272.7  407.35  7303.3  405.41  7404.8  408.02
#Mann= 8 ,-1 , 0
  2832.1     .05       0  5007.2     .03       0  5013.2     .05       0
  6390.6     .08       0  6525.1     .05       0  6646.5     .08       0
  6647.9      .1       0  6648.6     .05       0
Bank Sta=4969.1,5030.7
XS Rating Curve= 0 ,0
Exp/Cntr=0.3,0.1

Type RM Length L Ch R = 1 ,308975  ,1639,1639,1639
BEGIN DESCRIPTION:
UPPER KEECHI CREEK 111.0
END DESCRIPTION:
XS GIS Cut Line= 3
      3604299.61      10590160.2      3604499.61     10587660.19
      3604249.61     10586360.21
#Sta/Elev= 30
  2508.2  384.22  2728.9  375.49  2829.2  367.13  2999.2  358.09  3049.9  355.39
  3195.4  355.46  3220.5  352.63  3330.8  351.17    4013  347.71  4424.3  347.72
  4701.4  351.33  4795.5  349.42  4976.1  351.43  4993.1  344.52  4995.9  344.02
  4999.1  344.52  5018.7  347.32  5026.4  351.58    5157  348.37    5312  349.74
  5382.8  347.03  5410.8  349.31  5467.8  349.54  5484.6   347.2  5494.8  349.08
  5583.6  348.89  5667.9  350.82  5881.8  360.74  6075.3  373.46    6340  394.85
#Mann= 7 ,-1 , 0
  2508.2     .05       0  2999.2      .1       0  3195.4     .05       0
  4993.1     .03       0  4999.1     .05       0    5157     .12       0
  5583.6     .05       0
Bank Sta=4976.1,5026.4
XS Rating Curve= 0 ,0
Exp/Cntr=0.3,0.1

Type RM Length L Ch R = 1 ,307336  ,852,852,852
BEGIN DESCRIPTION:
UPPER KEECHI CREEK 110.0
END DESCRIPTION:
XS GIS Cut Line= 3
      3604892.77     10590329.89      3605499.61     10588760.19
      3604699.62     10585860.23
#Sta/Elev= 30
    3344  377.92    3518  375.25  3826.1  363.34  4519.2  350.48  4638.8  349.37
  4742.4  350.77    4846  350.87  4949.5  347.38  4957.4  347.79  4987.4  347.09
  4991.8  342.32  4994.5  341.82  4997.8  342.32  5005.5  342.91  5011.9  348.56
  5024.2  348.69  5978.7  346.92  6041.1  348.07  6081.5  347.71    6168   345.5
  6425.4  347.05  7288.3   350.5  7402.5  355.44  7529.9  364.77  7865.1  393.62
  7931.5  395.95  7962.6  392.01  7995.2  392.48  8018.1  397.49  8035.2   396.2
#Mann= 13 ,-1 , 0
    3344     .05       0  4519.2     .08       0  4638.8      .1       0
  4742.4     .15       0    4846      .1       0  4949.5     .05       0
  4991.8     .03       0  4997.8     .05       0  5978.7     .16       0
  6041.1     .05       0  6081.5     .12       0  6425.4     .05       0
  7995.2     .08       0
Bank Sta=4957.4,5024.2
XS Rating Curve= 0 ,0
Exp/Cntr=0.3,0.1

Type RM Length L Ch R = 1 ,306484  ,757,757,757
BEGIN DESCRIPTION:
Mapping XS d71f1223
END DESCRIPTION:
XS GIS Cut Line= 3
      3605912.71     10590492.73      3606173.13     10588604.68
      3605999.52     10585056.55
#Sta/Elev= 30
  2850.3  385.04  2924.4  385.43  3022.9  385.39  3337.4  383.05  3761.4  357.33
  3909.2     354  4106.1  352.44  4478.7  350.89  4629.5  346.05  4850.6  345.97
    4981  347.61    4991  346.86    4998  342.36  5000.8  341.86    5004  342.36
    5031  347.91  5041.1  347.88  5116.4  346.52  6262.5  347.92  6833.2  352.06
  6953.3  357.32  7113.5  352.61  7443.9  355.76  7584.1  359.52  7664.2   366.7
  7792.3  373.82  7999.7  383.75  8044.6  383.31  8064.7  386.69  8308.6  406.38
#Mann= 9 ,-1 , 0
  2850.3     .05       0  2924.4     .08       0  3022.9     .05       0
  3909.2     .08       0  4106.1     .05       0  4850.6     .16       0
    4998     .07       0    5004     .16       0  5116.4     .05       0
Bank Sta=4981,5041.1
XS Rating Curve= 0 ,0
Exp/Cntr=0.3,0.1

Type RM Length L Ch R = 1 ,305727  ,1201,1201,1201
BEGIN DESCRIPTION:
Mapping XS 005bc802
END DESCRIPTION:
XS GIS Cut Line= 4
       3606422.7     10590384.17      3606748.22     10588626.38
      3607052.04     10585132.45      3606900.12     10584676.69
#Sta/Elev= 30
  2734.6  384.95  2966.1  382.86  3470.9  358.97  4070.9  347.59  4338.1  346.15
  4454.7  345.67  4814.5  345.14  4825.8  345.38  4930.1  346.22  4980.2  346.72
  4990.2  342.93  5020.3  343.83  5030.4   346.2  5341.5  344.78  5388.7  342.63
  5391.5  342.13  5394.7  342.63  5441.9  344.32  5692.9  342.69  6353.6  343.98
    6394  344.16  7268.8   347.6  7483.3  351.83  7620.1  358.33    7861  363.28
  7991.5  368.26  8276.9  386.16  8366.5  396.91  8445.8  403.14  8509.8   408.4
#Mann= 10 ,-1 , 0
  2734.6     .05       0  4338.1     .08       0  4454.7     .05       0
  4814.5      .1       0  4930.1     .05       0  5388.7     .03       0
  5394.7     .05       0  6353.6     .16       0    6394     .05       0
  8445.8     .16       0
Bank Sta=4825.8,5030.4
XS Rating Curve= 0 ,0
Exp/Cntr=0.3,0.1

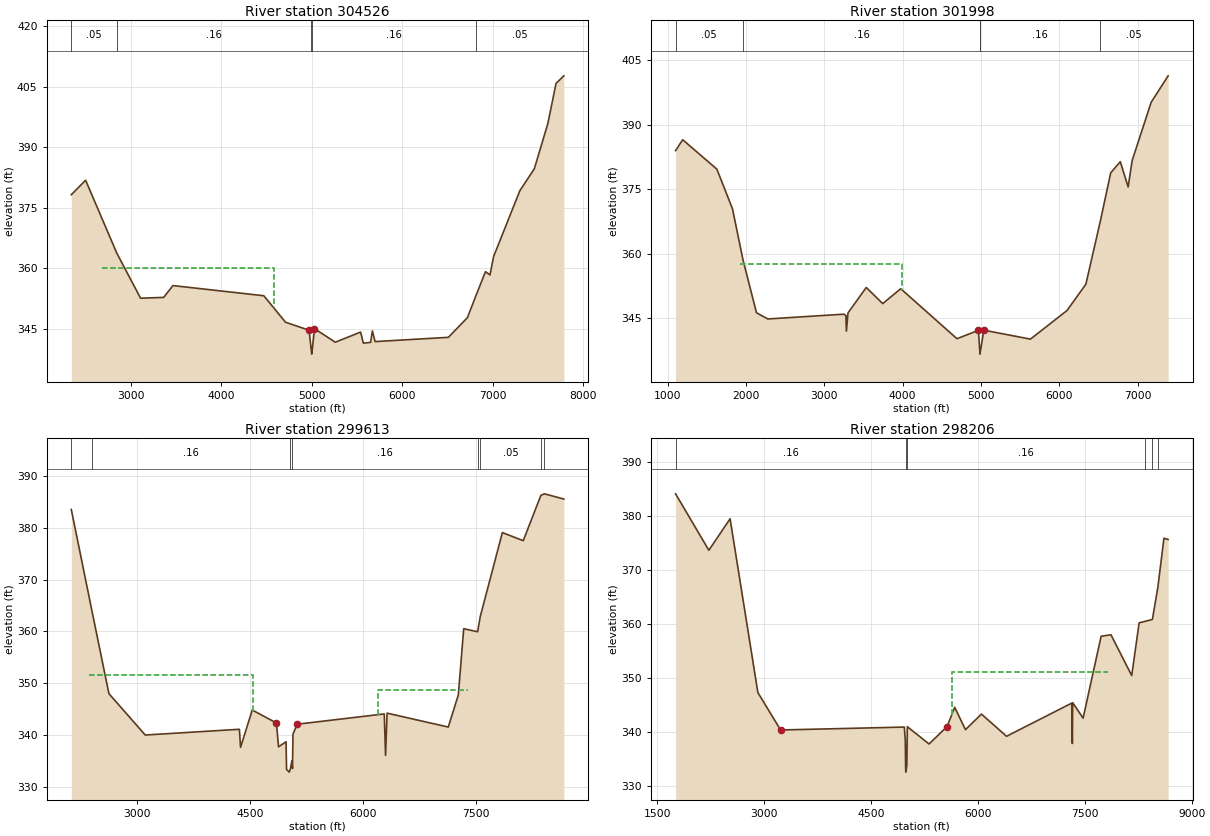
Type RM Length L Ch R = 1 ,304526  ,2528,2528,2528
BEGIN DESCRIPTION:
Mapping XS becfbf3a
END DESCRIPTION:
XS GIS Cut Line= 3
      3606965.21     10590264.87      3607779.03     10588550.42
      3607800.73     10585003.68
#Sta/Elev= 30
  2343.8  378.27    2502  381.86  2847.1  363.78  3109.6  352.62  3365.1  352.82
  3467.1  355.75  4471.8  353.23  4711.8  346.67  4971.8  344.68  4998.8  339.26
  5001.6  338.76  5004.8  339.26  5031.8  345.08  5261.8  341.71  5541.9  344.23
  5571.9  341.49  5651.9  341.66  5671.9   344.5  5701.9  341.87  6511.9  342.92
  6721.9  347.79  6821.9  353.55  6921.9   359.2  6971.9  358.39  7011.9  362.95
  7301.9  379.26  7461.9   384.7  7611.9  395.96  7701.9  405.86  7788.4  407.74
#Mann= 5 ,-1 , 0
  2343.8     .05       0  2847.1     .16       0  4998.8     .07       0
  5004.8     .16       0  6821.9     .05       0
#XS Ineff= 1 ,-1
 2681.82 4580.68  360.11
Permanent Ineff=
       F
Bank Sta=4971.8,5031.8
XS Rating Curve= 0 ,0
Exp/Cntr=0.3,0.1

Type RM Length L Ch R = 1 ,301998  ,2385,2385,2385
BEGIN DESCRIPTION:
Mapping XS a4fb22b0
END DESCRIPTION:
XS GIS Cut Line= 3
      3607996.06     10591230.52      3609330.68     10587172.38
      3609005.17     10585186.75
#Sta/Elev= 30
    1103  383.93  1193.6  386.47  1629.7  379.63  1829.5  370.38  1961.9  358.63
    2135  346.23  2279.9  344.79  3250.8   345.9  3276.1  345.58  3282.4  341.96
  3302.6  346.19  3535.7  352.11  3745.6  348.36  3975.5  351.82    4693   340.2
  4966.4  342.13  4984.8  337.11  4987.5  336.61  4990.8  337.11  5035.3  342.18
  5630.5   340.1  6097.1  346.76  6337.3  352.86  6521.2  367.47    6654  378.76
  6776.5  381.36  6876.9  375.48  6927.6  381.62  7170.8  395.19  7387.1  401.33
#Mann= 5 ,-1 , 0
    1103     .05       0  1961.9     .16       0  4984.8     .07       0
  4990.8     .16       0  6521.2     .05       0
#XS Ineff= 1 ,-1
 1918.75 3994.89  357.68
Permanent Ineff=
       T
Bank Sta=4966.4,5035.3
XS Rating Curve= 0 ,0
Exp/Cntr=0.3,0.1

Type RM Length L Ch R = 1 ,299613  ,1407,1407,1407
BEGIN DESCRIPTION:
Mapping XS f8e2774e
END DESCRIPTION:
XS GIS Cut Line= 4
      3608918.36     10591371.59      3609829.81      10588951.9
      3610394.05     10588311.71      3609699.61     10585295.22
#Sta/Elev= 30
  2128.9  383.57  2408.2  363.59  2628.1  347.98  3109.7  339.98  4358.9  341.09
  4374.4   337.6  4529.5  344.81  4850.1  342.31  4878.3   337.7  4977.8  338.68
  4984.5  333.33  5020.3  332.81  5034.8  333.43  5055.6  334.99  5063.2  333.51
  5069.9  340.17  5126.8  342.07  6280.6  344.06    6298  336.05  6318.3  344.21
  7129.9  341.52  7263.5  347.74  7334.5  360.52  7519.2  359.94    7554  362.86
  7847.5   379.1  8124.6  377.54  8358.9   386.3  8406.1  386.59  8663.3  385.58
#Mann= 8 ,-1 , 0
  2128.9     .05       0  2408.2     .16       0  5034.8     .07       0
  5055.6     .16       0  7519.2      .1       0    7554     .05       0
  8358.9     .16       0  8406.1     .05       0
#XS Ineff= 2 ,-1
 2369.89 4545.45  351.67 6203.98 7397.16  348.63
Permanent Ineff=
       T       F
Bank Sta=4850.1,5126.8
XS Rating Curve= 0 ,0
Exp/Cntr=0.3,0.1

Type RM Length L Ch R = 1 ,298206  ,1289,1289,1289
BEGIN DESCRIPTION:
UPPER KEECHI CREEK 109.0
END DESCRIPTION:
XS GIS Cut Line= 3
      3608549.46     10592109.42      3610958.29     10589364.22
      3610068.54      10586228.4
#Sta/Elev= 30
  1757.4  384.06  2224.4   373.6  2522.3  379.44  2912.3  347.23  3231.2  340.29
  4966.8  340.83    4981  338.34  4985.6  332.98  4988.4  332.48  5002.5   333.7
  5009.5   340.9  5314.1   337.7  5567.1  340.92  5673.7   344.5  5825.2  340.35
  6049.5  343.24  6401.3  339.12    7316  345.27  7324.7  337.79  7329.9  345.34
  7475.9  342.49  7728.8  357.66  7866.9  357.94    8158  350.37  8261.9  360.15
  8344.4  360.42  8447.8  360.77  8524.3  366.68  8610.2  375.83  8669.2   375.6
#Mann= 6 ,-1 , 0
  1757.4     .16       0  4985.6     .07       0  5002.5     .16       0
  8344.4     .08       0  8447.8      .1       0  8524.3     .05       0
#XS Ineff= 1 ,-1
 5631.82 7822.73  350.99
Permanent Ineff=
       T
Bank Sta=3231.2,5567.1
XS Rating Curve= 0 ,0
Exp/Cntr=0.3,0.1