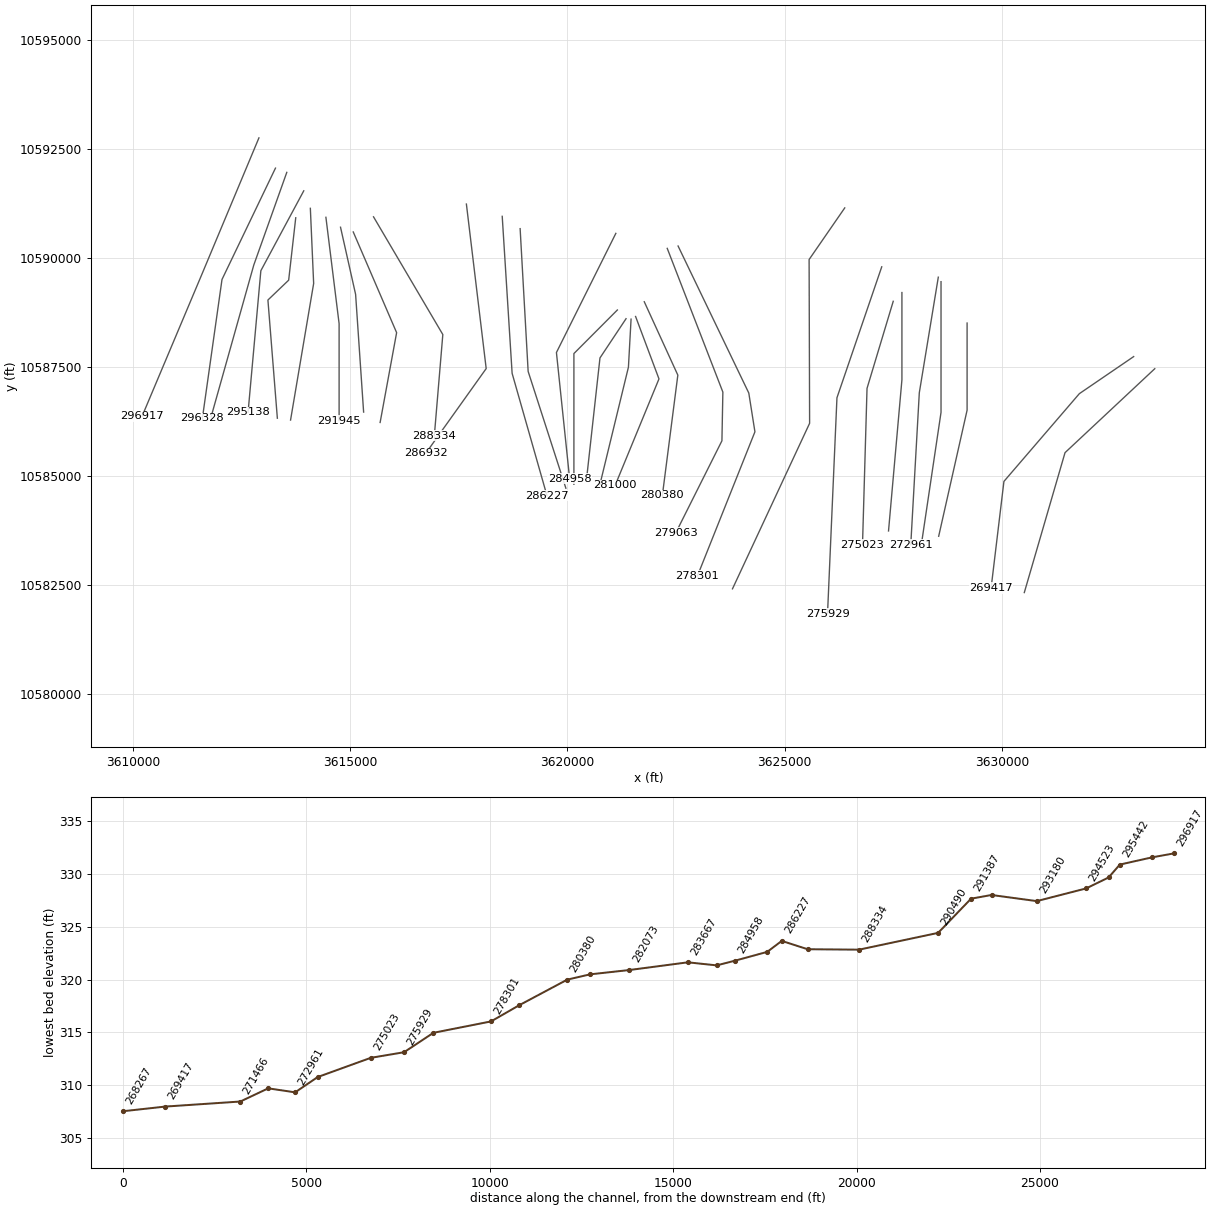
HEC-RAS study UPPER KEECHI CREEK.prj: UPPER KEECHI CREEK Base Level Engineering

--- UPPER KEECHI CREEK.g01 (geometry) --- (continued)

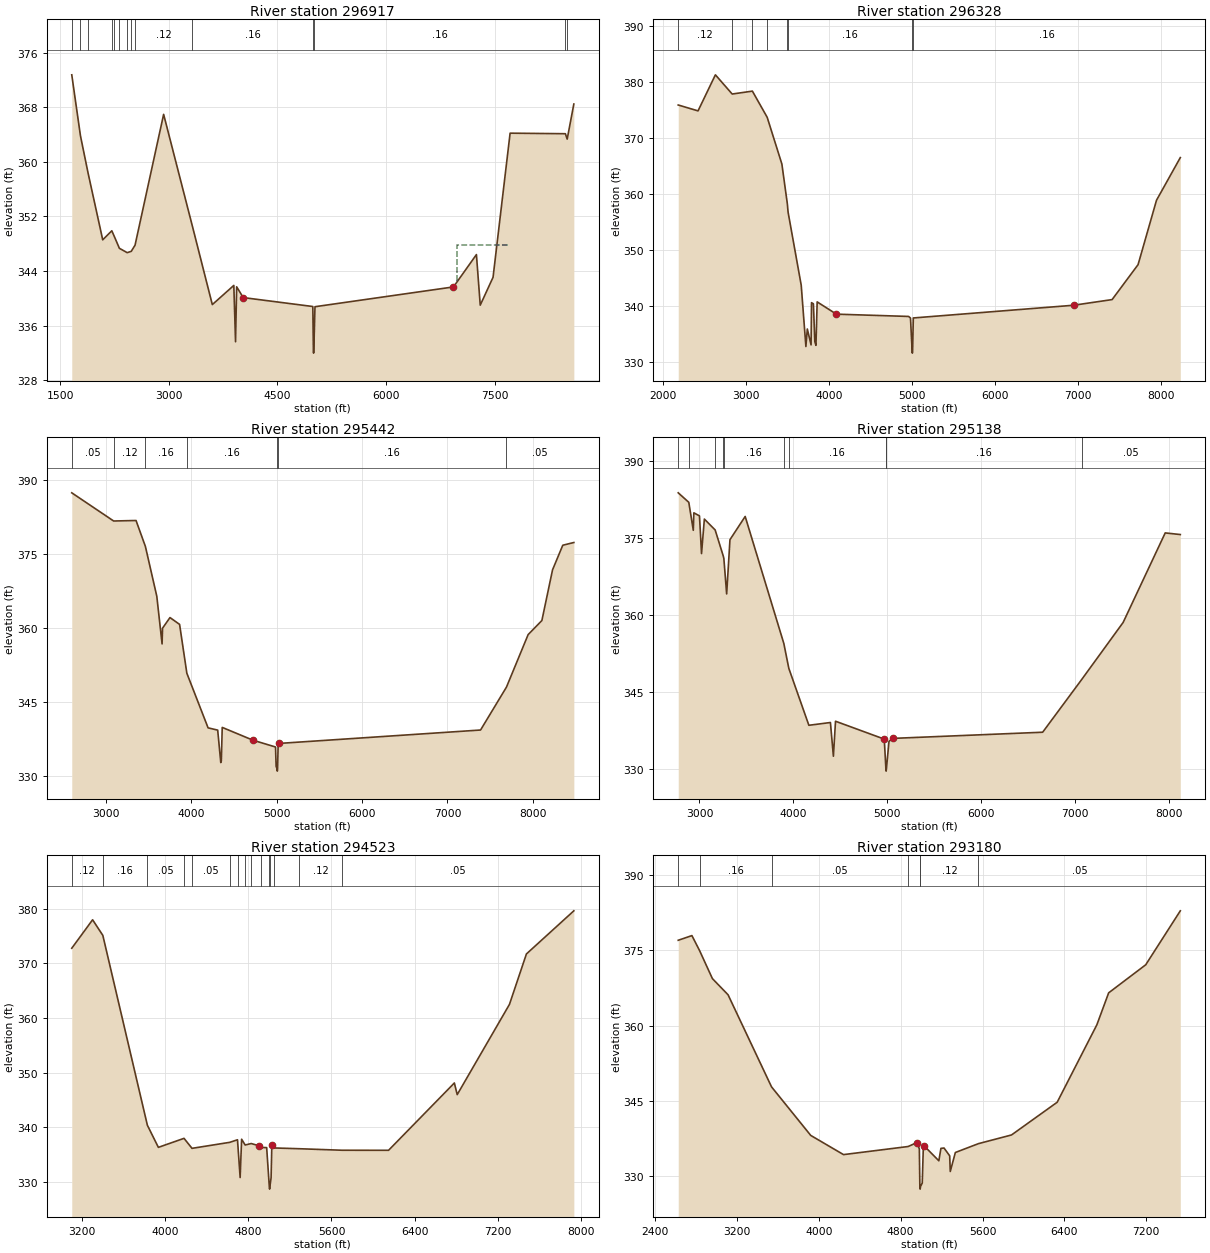
Type RM Length L Ch R = 1 ,296917  ,589,589,589
BEGIN DESCRIPTION:
UPPER KEECHI CREEK 108.0
END DESCRIPTION:
XS GIS Cut Line= 3
      3612899.62     10592760.21      3611599.61     10589660.19
      3610209.57     10586369.39
#Sta/Elev= 30
    1661  372.74  1780.9  363.81  1886.2  358.35  2088.5  348.56  2214.1  349.89
  2248.8  349.05  2318.7  347.32  2426.9  346.68  2482.7  346.88    2535  347.78
  2929.7  366.95  3327.2  350.55    3602  339.07    3899  341.88  3922.8  333.63
  3938.2  341.68  4028.7   340.1    4990  338.79  4997.9  332.46  5000.6  331.96
  5003.9  332.46  5019.9  338.76  6932.4  341.66  7249.5   346.4  7302.3  338.99
  7479.1  343.07  7714.7  364.19  8478.1  364.11    8503  363.32  8594.9  368.46
#Mann= 14 ,-1 , 0
    1661     .12       0  1780.9     .16       0  1886.2     .12       0
  2214.1     .16       0  2248.8     .05       0  2318.7     .16       0
  2426.9     .12       0  2482.7     .16       0    2535     .12       0
  3327.2     .16       0  4997.9     .03       0  5003.9     .16       0
  8478.1     .08       0    8503     .05       0
#XS Ineff= 1 ,-1
 6986.36 7695.45  347.87
Permanent Ineff=
       T
Bank Sta=4028.7,6932.4
XS Rating Curve= 0 ,0
Exp/Cntr=0.3,0.1

Type RM Length L Ch R = 1 ,296328  ,886,886,886
BEGIN DESCRIPTION:
UPPER KEECHI CREEK 107.0
END DESCRIPTION:
XS GIS Cut Line= 3
      3613280.31       10592066.      3612049.61     10589510.19
      3611598.47     10586325.98
#Sta/Elev= 30
  2183.5   375.9  2422.3  374.85  2631.5  381.29  2833.9  377.86  3077.5  378.38
    3256   373.7    3433  365.36  3498.6  358.28  3507.8  356.77  3666.1  343.72
  3722.5  332.77  3739.6   335.9  3784.9  333.06  3790.4   340.6    3813   340.4
  3830.1  333.64  3843.7  332.98  3858.3  340.74  4090.1  338.55  4960.9  338.14
  4983.5  337.85  5003.1  332.09  5005.9  331.59  5009.1  332.09  5017.4  337.87
  6949.3  340.14  7413.9  341.15    7727  347.39  7949.2  358.89  8236.2  366.51
#Mann= 8 ,-1 , 0
  2183.5     .12       0  2833.9     .16       0  3077.5     .05       0
    3256     .16       0  3498.6     .12       0  3507.8     .16       0
  5003.1     .03       0  5009.1     .16       0
Bank Sta=4090.1,6949.3
XS Rating Curve= 0 ,0
Exp/Cntr=0.3,0.1

Type RM Length L Ch R = 1 ,295442  ,304,304,304
BEGIN DESCRIPTION:
UPPER KEECHI CREEK 106.0
END DESCRIPTION:
XS GIS Cut Line= 3
      3613540.77     10591968.43       3612781.2     10589841.65
      3611799.62     10586360.23
#Sta/Elev= 30
  2603.6   387.3  3093.6  381.59  3355.7  381.69  3465.3  376.43  3598.8  366.33
  3660.4  356.68  3665.7  359.86  3752.8  362.02  3865.3  360.64  3950.3  350.74
  4198.8  339.67  4311.3  339.21  4347.4  332.64  4353.8  332.98  4364.4  339.76
  4725.5  337.16  4988.1  335.79  4995.1  331.87  5005.9   331.4  5008.7   330.9
  5011.9   331.4  5019.3  336.55  5034.3  336.52  7387.5  339.23  7690.8  347.93
  7944.4  358.57  8105.1  361.42  8229.8  371.69  8349.7  376.68  8479.1  377.23
#Mann= 7 ,-1 , 0
  2603.6     .05       0  3093.6     .12       0  3465.3     .16       0
  3950.3     .16       0  5005.9     .03       0  5011.9     .16       0
  7690.8     .05       0
Bank Sta=4725.5,5034.3
XS Rating Curve= 0 ,0
Exp/Cntr=0.3,0.1

Type RM Length L Ch R = 1 ,295138  ,615,615,615
BEGIN DESCRIPTION:
UPPER KEECHI CREEK 105.0
END DESCRIPTION:
XS GIS Cut Line= 3
      3613931.39     10591545.23      3612943.96     10589711.45
      3612649.61     10586460.18
#Sta/Elev= 30
  2773.6  383.84  2886.1  381.99  2934.1  376.55  2939.8  379.95  2999.8  379.35
  3021.7  372.02  3051.9  378.73  3166.9  376.61  3252.7  371.57  3259.5  371.06
  3289.4  364.16  3324.5  374.72  3486.6  379.24  3898.3  354.52  3951.4  349.68
    4165   338.6  4394.4  339.14  4426.2  332.58  4448.7  339.39    4968  335.91
  4985.1  330.18  4987.9  329.68  4991.1  330.18  5018.3  335.48  5058.4  336.05
  6654.9  337.25  7069.5  347.48  7512.2  358.62  7960.2  376.04  8120.9  375.72
#Mann= 10 ,-1 , 0
  2773.6     .05       0  2886.1     .12       0  3166.9     .16       0
  3252.7     .12       0  3259.5     .16       0  3898.3     .05       0
  3951.4     .16       0  4985.1     .03       0  4991.1     .16       0
  7069.5     .05       0
Bank Sta=4968,5058.4
XS Rating Curve= 0 ,0
Exp/Cntr=0.3,0.1

Type RM Length L Ch R = 1 ,294523  ,1343,1343,1343
BEGIN DESCRIPTION:
UPPER KEECHI CREEK 104.0
END DESCRIPTION:
XS GIS Cut Line= 4
      3613746.92     10590926.77      3613584.15     10589494.43
      3613106.72      10589038.7      3613323.74     10586326.05
#Sta/Elev= 30
  3105.1  372.76  3305.3  377.97  3403.5  375.11  3831.4  340.34    3937  336.29
  4183.3  337.94  4260.3  336.11  4622.7  337.21  4697.1  337.68  4722.5  330.76
  4736.7  337.78  4770.8  336.72  4828.9  336.99  4899.3   336.6  4918.9  336.28
  4977.3  336.24  5002.6  329.14  5005.4  328.64  5008.6  329.14  5019.8  330.73
  5026.7  336.64  5047.5  336.18  5288.6  336.04  5702.7  335.76  6148.2  335.75
  6780.2  348.08  6807.8  345.95  7309.4  362.47  7472.4  371.71    7928  379.61
#Mann= 15 ,-1 , 0
  3105.1     .12       0  3403.5     .16       0  3831.4     .05       0
  4183.3     .12       0  4260.3     .05       0  4622.7     .07       0
  4697.1     .12       0  4770.8     .07       0  4828.9     .05       0
  4918.9     .12       0  5002.6     .07       0  5008.6     .12       0
  5047.5     .05       0  5288.6     .12       0  5702.7     .05       0
Bank Sta=4899.3,5026.7
XS Rating Curve= 0 ,0
Exp/Cntr=0.3,0.1

Type RM Length L Ch R = 1 ,293180  ,1235,1235,1235
BEGIN DESCRIPTION:
UPPER KEECHI CREEK 103.0
END DESCRIPTION:
XS GIS Cut Line= 3
      3614083.29     10591143.72      3614159.24     10589418.48
      3613627.78     10586283.92
#Sta/Elev= 30
  2626.4  376.97  2760.1   377.9  2835.1  374.91  2960.3  369.34  3113.3  366.12
  3538.2  347.79  3921.2  338.13  4241.5  334.31  4872.8  335.92  4960.1  336.71
  4982.4  335.44  4987.6  327.94  4990.3  327.44  4993.6  327.94  5010.9  328.65
    5021  335.55  5031.1  336.01  5173.1  333.08  5193.4  335.55  5223.8  335.62
    5279  334.07  5284.7  330.95  5334.3  334.73  5559.8  336.49  5883.1  338.22
  6329.4  344.73    6717  360.14  6832.6  366.51  7194.6  372.09  7532.6  382.83
#Mann= 7 ,-1 , 0
  2626.4     .05       0  2835.1     .16       0  3538.2     .05       0
  4872.8     .12       0  4987.6     .07       0  4993.6     .12       0
  5559.8     .05       0
Bank Sta=4960.1,5031.1
XS Rating Curve= 0 ,0
Exp/Cntr=0.3,0.1

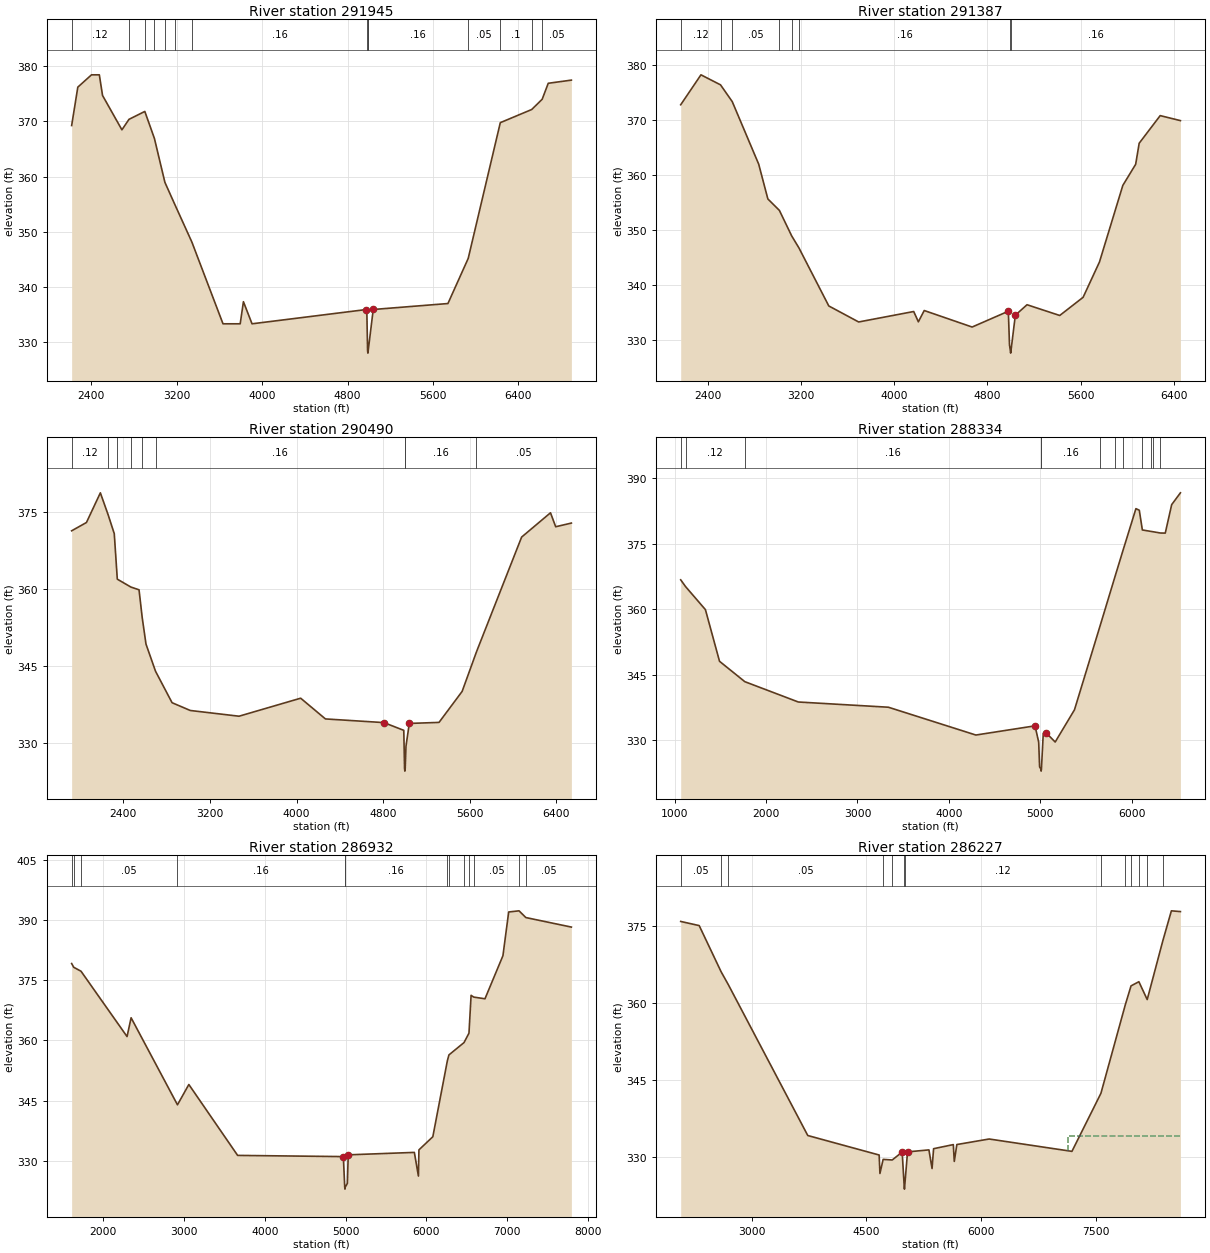
Type RM Length L Ch R = 1 ,291945  ,558,558,558
BEGIN DESCRIPTION:
UPPER KEECHI CREEK 102.0
END DESCRIPTION:
XS GIS Cut Line= 3
      3614441.36     10590937.59      3614745.18     10588496.17
      3614745.18     10586273.53
#Sta/Elev= 30
  2214.8  369.23  2272.6  376.18  2400.9  378.41  2474.2  378.41  2504.4  374.67
  2685.8  368.45  2752.1  370.35  2900.5  371.78  2990.4  366.89  3088.7  358.94
  3187.1   354.7  3340.8  348.16  3633.1  333.33  3794.3  333.33  3824.5  337.33
  3905.1  333.33    4971   335.9    4981  335.51  4984.2  332.31    4988  328.52
  4990.8  328.02    4994  328.52    5041  335.92    5741     337    5931  345.17
  6231.8  369.75  6526.1  372.13  6624.2  373.99    6681  376.88  6897.7  377.45
#Mann= 14 ,-1 , 0
  2214.8     .12       0  2752.1     .16       0  2900.5     .05       0
  2990.4     .08       0  3088.7      .1       0  3187.1     .05       0
  3340.8     .16       0  4984.2     .12       0    4988     .07       0
    4994     .16       0    5931     .05       0  6231.8      .1       0
  6526.1     .08       0  6624.2     .05       0
Bank Sta=4971,5041
XS Rating Curve= 0 ,0
Exp/Cntr=0.3,0.1

Type RM Length L Ch R = 1 ,291387  ,897,897,897
BEGIN DESCRIPTION:
UPPER KEECHI CREEK 101.0
END DESCRIPTION:
XS GIS Cut Line= 3
      3614777.74     10590709.67      3615124.95     10589168.91
      3615309.41      10586467.1
#Sta/Elev= 30
  2168.3  372.79    2342  378.23  2509.9  376.41  2610.6  373.36  2837.8  361.98
  2916.1  355.68    3015   353.6  3120.2  348.98  3182.6  346.79  3438.9  336.24
  3695.1  333.33  4167.4  335.23  4207.5  333.36  4257.6  335.41  4668.6  332.41
  4979.3  335.28  4989.3  329.14  4996.3  328.17  4999.1  327.67  5002.3  328.17
  5039.4  334.56  5139.7  336.46  5420.3  334.51  5620.8  337.81  5761.1  344.22
  5961.6  358.14  6071.8  361.98  6101.9   365.8  6282.3  370.82  6455.8  369.91
#Mann= 8 ,-1 , 0
  2168.3     .12       0  2509.9     .16       0  2610.6     .05       0
    3015     .08       0  3120.2     .05       0  3182.6     .16       0
  4996.3     .03       0  5002.3     .16       0
Bank Sta=4979.3,5039.4
XS Rating Curve= 0 ,0
Exp/Cntr=0.3,0.1

Type RM Length L Ch R = 1 ,290490  ,2156,2156,2156
BEGIN DESCRIPTION:
UPPER KEECHI CREEK 100.0
END DESCRIPTION:
XS GIS Cut Line= 3
      3615070.68     10590601.25      3616068.96       10588290.
       3615689.2     10586228.41
#Sta/Elev= 30
  1923.7  371.39  2060.4  373.01  2188.8  378.81  2260.4  374.53  2317.2  370.83
  2345.2  361.94  2470.6   360.4  2545.8  359.86  2575.6  354.36  2610.1  349.25
  2698.3  343.94  2850.8   337.8  3018.8  336.28  3469.1  335.16  4038.1  338.68
  4266.8  334.63  4807.2  333.91  4990.2   332.4  4997.4  324.93  5000.1  324.43
  5003.4  324.93  5010.6   329.3  5041.1  333.75  5315.6  333.95  5529.1  340.01
  5661.3  347.73  6078.2  370.16  6344.9  374.91  6392.8  372.18  6537.6   372.9
#Mann= 9 ,-1 , 0
  1923.7     .12       0  2260.4     .05       0  2345.2      .1       0
  2470.6     .15       0  2575.6     .05       0  2698.3     .16       0
  4997.4     .07       0  5003.4     .16       0  5661.3     .05       0
Bank Sta=4807.2,5041.1
XS Rating Curve= 0 ,0
Exp/Cntr=0.3,0.1

Type RM Length L Ch R = 1 ,288334  ,1402,1402,1402
BEGIN DESCRIPTION:
Mapping XS 057e00ff
END DESCRIPTION:
XS GIS Cut Line= 3
      3615537.26     10590948.45      3617132.33      10588246.6
      3616937.04     10585924.86
#Sta/Elev= 30
  1066.5  366.73  1119.9  365.17    1337  359.89  1491.2  348.04  1768.2  343.36
  2353.5   338.7  3338.9   337.5    4296  331.12  4943.1  333.23  4983.2   329.5
  4993.2   323.8  5007.2  323.34  5009.9  322.84  5013.2  323.34  5033.4   331.5
  5063.5  331.64  5163.8  329.52  5374.8  336.91  5655.6  356.21  5821.2  367.68
  5902.6  373.27    6047  383.06  6083.9   382.7  6117.5  378.17  6216.3  377.82
  6234.3  377.76    6315  377.47  6368.1  377.45  6438.3  383.98    6534  386.69
#Mann= 12 ,-1 , 0
  1066.5     .08       0  1119.9     .12       0  1768.2     .16       0
  5007.2     .07       0  5013.2     .16       0  5655.6     .16       0
  5821.2     .12       0  5902.6     .05       0  6117.5      .1       0
  6216.3     .05       0  6234.3     .15       0    6315     .05       0
Bank Sta=4943.1,5063.5
XS Rating Curve= 0 ,0
Exp/Cntr=0.3,0.1

Type RM Length L Ch R = 1 ,286932  ,705,705,705
BEGIN DESCRIPTION:
UPPER KEECHI CREEK 99.0
END DESCRIPTION:
XS GIS Cut Line= 3
      3617674.86     10591241.41       3618130.6     10587465.35
      3616742.48     10585524.16
#Sta/Elev= 30
    1607   379.2  1632.5  378.27  1723.1  377.28  2293.2  360.97  2343.5  365.66
  2917.7  343.93  3058.7     349    3663   331.3  4972.5     331  4989.6  323.38
  4992.4  322.88  4995.6  323.38  5022.2  324.31  5032.9  331.44  5851.9  332.05
  5902.3  326.14  5908.6  332.68  6080.7  335.96    6261  354.94  6280.4  356.39
  6467.2  359.47  6528.5  361.82  6554.7  371.26  6588.1  370.82  6726.7   370.4
  6949.1  381.15  7020.4  392.07  7148.7  392.36    7233  390.68  7796.9   388.3
#Mann= 13 ,-1 , 0
    1607     .05       0  1632.5     .08       0  1723.1     .05       0
  2917.7     .16       0  4989.6     .07       0  4995.6     .16       0
    6261      .1       0  6280.4     .15       0  6467.2      .1       0
  6528.5     .08       0  6588.1     .05       0  7148.7     .08       0
    7233     .05       0
Bank Sta=4972.5,5032.9
XS Rating Curve= 0 ,0
Exp/Cntr=0.3,0.1

Type RM Length L Ch R = 1 ,286227  ,396,396,396
BEGIN DESCRIPTION:
Mapping XS 93c9ccc4
END DESCRIPTION:
XS GIS Cut Line= 3
      3618499.52      10590959.3      3618727.38     10587356.85
      3619530.32     10584546.55
#Sta/Elev= 30
  2072.4  375.85  2314.2  375.04  2600.1  366.06  2696.6  363.48  3733.5  334.12
  4666.7  330.32  4676.7  326.72  4718.8  329.47  4837.5  329.35  4967.3   330.9
  4994.3  324.17  4997.1  323.67  5000.3  324.17  5037.4  330.93  5317.1  331.32
  5358.1  327.69  5378.1  331.55  5635.9  332.35  5648.6  329.07  5682.1  332.36
  6104.3  333.44  7186.6  331.03  7565.4  342.34  7884.7  359.63  7959.2  363.29
  8061.7   364.1  8170.6  360.62  8373.8  372.03  8486.6  377.92  8604.8  377.77
#Mann= 13 ,-1 , 0
  2072.4     .05       0  2600.1     .08       0  2696.6     .05       0
  4718.8     .16       0  4837.5     .12       0  4994.3     .07       0
  5000.3     .12       0  7565.4     .05       0  7884.7     .08       0
  7959.2     .05       0  8061.7      .1       0  8170.6     .12       0
  8373.8     .05       0
#XS Ineff= 2 , 0
       0                 7130.68       0  334.04
Permanent Ineff=
       T       T
Bank Sta=4967.3,5037.4
XS Rating Curve= 0 ,0
Exp/Cntr=0.3,0.1

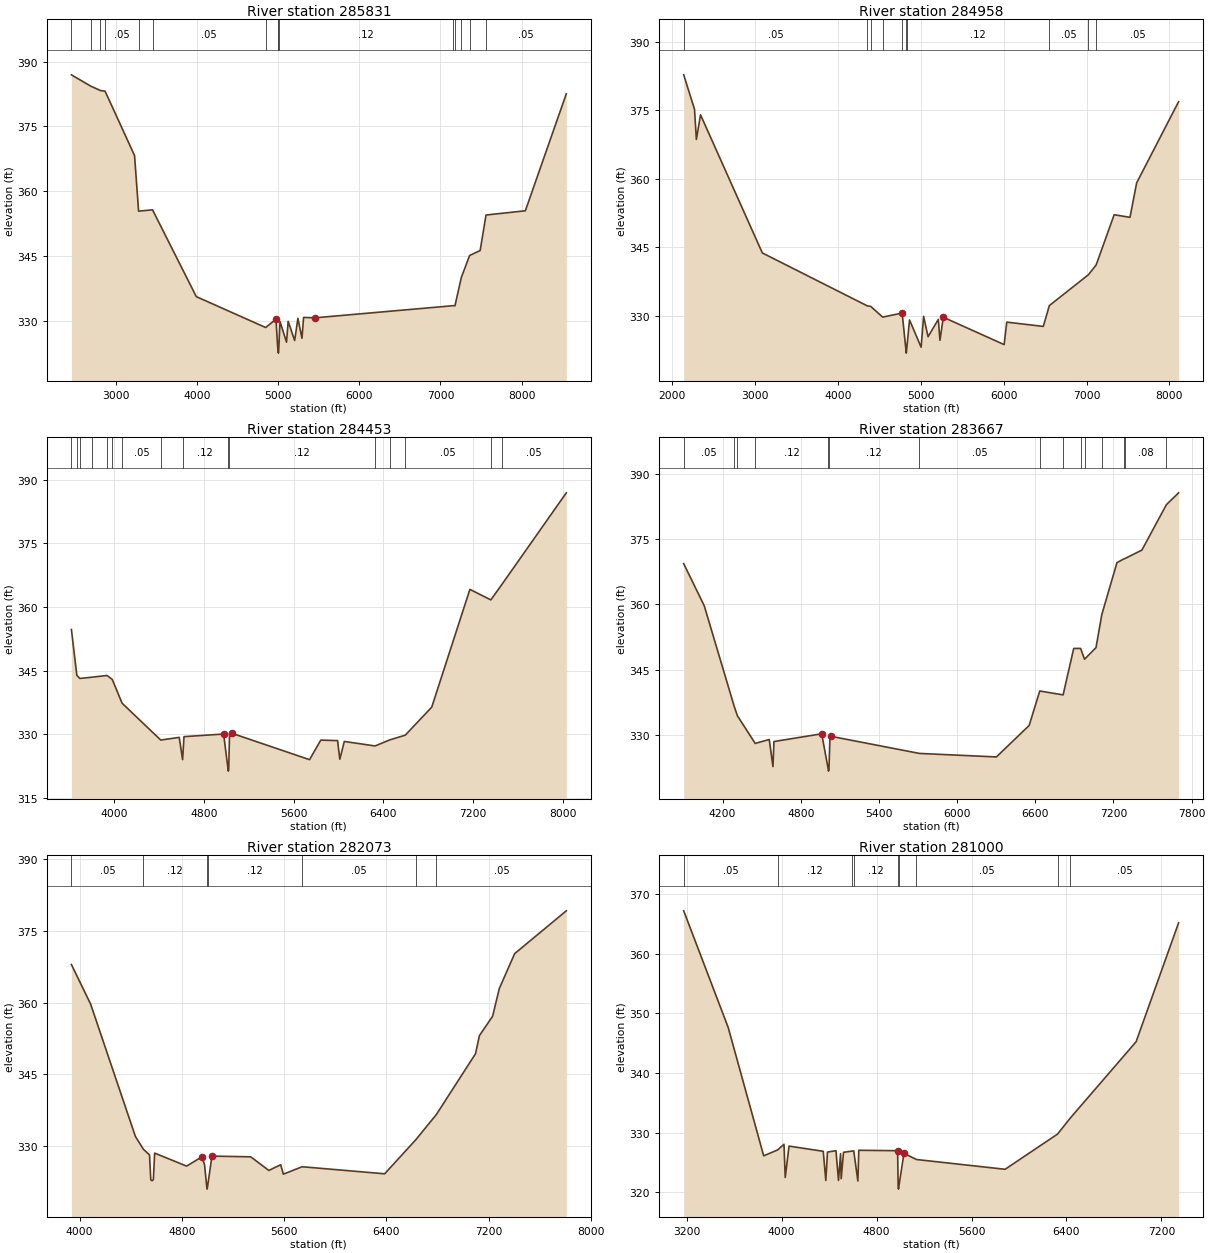
Type RM Length L Ch R = 1 ,285831  ,873,873,873
BEGIN DESCRIPTION:
Mapping XS 5eeba5be
END DESCRIPTION:
XS GIS Cut Line= 3
      3618911.84     10590677.18      3619096.31     10587400.25
      3619964.36     10584720.14
#Sta/Elev= 30
  2451.2  386.93  2691.1   384.3  2809.6   383.3  2866.3  383.15  3229.4  368.28
  3279.3  355.43    3451  355.74  3990.6  335.68  4844.8  328.55  4972.2  330.45
  4993.1   324.1  4999.2  323.13    5002  322.63  5005.2  323.13  5022.3  329.91
  5102.4  325.16  5122.4  329.98  5202.5  325.54  5242.6  330.66  5292.7  326.07
  5312.7  330.88  5452.9  330.79    7155  333.59  7178.2  333.57  7256.8  340.11
  7358.6  345.18  7488.8  346.34  7561.1  354.54  8045.9  355.52  8550.5  382.55
#Mann= 15 ,-1 , 0
  2451.2     .08       0  2691.1     .05       0  2809.6     .08       0
  2866.3     .05       0  3279.3      .1       0    3451     .05       0
  4844.8     .16       0  4993.1     .12       0  4999.2     .07       0
  5005.2     .12       0    7155     .07       0  7178.2     .05       0
  7256.8     .12       0  7358.6      .1       0  7561.1     .05       0
#XS Ineff= 1 ,-1
 6916.64 7386.17   332.3
Permanent Ineff=
       T
Bank Sta=4972.2,5452.9
XS Rating Curve= 0 ,0
Exp/Cntr=0.3,0.1

Type RM Length L Ch R = 1 ,284958  ,505,505,505
BEGIN DESCRIPTION:
Mapping XS a19fe6dc
END DESCRIPTION:
XS GIS Cut Line= 3
      3621114.55     10590568.68      3619747.35     10587834.28
      3620051.17     10584937.12
#Sta/Elev= 30
  2139.6  382.75  2270.1   375.2  2292.4   368.6  2342.7     374  3088.2  343.74
  4355.7  332.14  4394.5  332.05  4540.2  329.69  4774.5  330.58  4775.3  330.53
  4821.8   322.3  4824.5   321.8  4827.8   322.3  4863.9  329.06  5003.7   323.1
  5033.6  329.86  5087.5   325.4  5210.9  329.19    5231  324.61  5271.3  329.66
  6005.3  323.67  6036.9  328.59  6477.8  327.65  6550.6  332.21  7022.4  338.98
  7115.3  341.11  7332.5  352.11  7523.5  351.54    7604  359.09  8109.8  376.87
#Mann= 10 ,-1 , 0
  2139.6     .05       0  4355.7     .16       0  4394.5     .05       0
  4540.2     .16       0  4775.3     .12       0  4821.8     .07       0
  4827.8     .12       0  6550.6     .05       0  7022.4      .1       0
  7115.3     .05       0
Bank Sta=4774.5,5271.3
XS Rating Curve= 0 ,0
Exp/Cntr=0.3,0.1

Type RM Length L Ch R = 1 ,284453  ,786,786,786
BEGIN DESCRIPTION:
UPPER KEECHI CREEK 98.0
END DESCRIPTION:
XS GIS Cut Line= 3
      3621149.59     10588810.17      3620149.61     10587810.19
      3620149.61     10584810.17
#Sta/Elev= 30
  3617.7  354.72    3666  343.93  3692.8  343.18  3800.6  343.48  3935.3  343.88
  3981.6  342.97  4069.9  337.35  4414.6  328.67  4579.3   329.3  4609.6  324.05
  4621.8  329.47  4975.3  330.09  5014.7  321.85  5017.5  321.35  5020.7  321.85
  5028.3  330.29  5051.9  330.24  5741.9  324.05  5841.9  328.66  5991.9  328.54
  6011.9  324.16  6051.9  328.34  6326.3  327.28  6455.9   328.7  6595.3  329.82
  6831.9  336.43  7171.9  364.16  7358.8  361.69  7456.9  365.31  8031.9  386.91
#Mann= 16 ,-1 , 0
  3617.7     .08       0    3666      .1       0  3692.8     .15       0
  3800.6      .1       0  3935.3     .15       0  3981.6      .1       0
  4069.9     .05       0  4414.6     .16       0  4609.6     .12       0
  5014.7     .07       0  5020.7     .12       0  6326.3     .05       0
  6455.9      .1       0  6595.3     .05       0  7358.8     .08       0
  7456.9     .05       0
Bank Sta=4975.3,5051.9
XS Rating Curve= 0 ,0
Exp/Cntr=0.3,0.1

Type RM Length L Ch R = 1 ,283667  ,1594,1594,1594
BEGIN DESCRIPTION:
UPPER KEECHI CREEK 97.0
END DESCRIPTION:
XS GIS Cut Line= 3
      3621349.63     10588610.22      3620749.61     10587710.19
      3620449.61      10585010.2
#Sta/Elev= 30
  3901.6  369.33  4059.4  359.64  4289.4  336.51  4313.4  334.39  4450.4  328.01
  4558.1  328.91  4586.7  322.68  4594.2  328.44  4960.8  330.22  5010.5  322.14
  5013.2  321.64  5016.5  322.14  5023.5  328.93  5033.6  329.63  5710.6  325.71
  6301.4   324.9  6552.9  332.13  6634.5  340.06  6813.5  339.16    6895  349.84
    6948  349.84  6978.1  347.36    7066  350.03  7110.9  357.66    7227  369.57
  7281.9  370.44  7288.6  370.51  7418.2  372.45  7606.4  382.89  7699.9  385.61
#Mann= 15 ,-1 , 0
  3901.6     .05       0  4289.4      .1       0  4313.4     .05       0
  4450.4     .12       0  5010.5     .07       0  5016.5     .12       0
  5710.6     .05       0  6634.5      .1       0  6813.5     .05       0
    6948     .08       0  6978.1     .05       0  7110.9     .08       0
  7281.9      .1       0  7288.6     .08       0  7606.4     .05       0
Bank Sta=4960.8,5033.6
XS Rating Curve= 0 ,0
Exp/Cntr=0.3,0.1

Type RM Length L Ch R = 1 ,282073  ,1073,1073,1073
BEGIN DESCRIPTION:
UPPER KEECHI CREEK 96.0
END DESCRIPTION:
XS GIS Cut Line= 3
      3621465.23     10588600.09      3621404.47     10587497.69
      3620749.61      10584810.2
#Sta/Elev= 30
  3936.5  367.97  4086.6  359.69  4437.2  331.93  4499.5  329.26  4547.3  328.08
  4557.3  322.84  4567.4  322.67  4577.4  322.89  4587.4  328.46  4837.8  325.73
  4957.9   327.7    4978  325.95    4995  321.41  4997.8  320.91    5001  321.41
  5035.5  327.83  5338.6  327.68  5480.6  324.82  5573.2  326.03    5594  324.04
  5740.8   325.6  6386.3  324.12  6630.8  331.29    6791  336.56  7096.5  349.27
  7127.4  353.08  7230.3  357.12  7282.8  362.94  7402.8  370.25  7806.7  379.22
#Mann= 7 ,-1 , 0
  3936.5     .05       0  4499.5     .12       0    4995     .07       0
    5001     .12       0  5740.8     .05       0  6630.8     .08       0
    6791     .05       0
Bank Sta=4957.9,5035.5
XS Rating Curve= 0 ,0
Exp/Cntr=0.3,0.1

Type RM Length L Ch R = 1 ,281000  ,620,620,620
BEGIN DESCRIPTION:
UPPER KEECHI CREEK 95.0
END DESCRIPTION:
XS GIS Cut Line= 3
      3621569.39     10588660.91      3622107.59     10587228.59
      3621100.65     10584789.36
#Sta/Elev= 30
  3175.5  367.21  3550.2  347.64  3849.4  326.09  3965.9  327.07  4020.2  328.02
  4030.9  322.46  4062.9  327.72    4351  326.85  4372.7  321.96  4386.6  326.72
  4458.2  326.95  4479.6  321.96  4496.8  326.46  4502.2  322.25  4521.7  326.68
  4595.7  326.89  4607.8  326.92  4642.7  321.87  4650.5  327.02  4977.6  326.95
  4982.2     321  4984.9   320.5  4988.2     321  5030.9   326.5  5136.2  325.47
  5883.1  323.83  6324.9  329.74  6432.7  332.44  6986.6  345.24  7344.5  365.19
#Mann= 9 ,-1 , 0
  3175.5     .05       0  3965.9     .12       0  4595.7     .16       0
  4607.8     .12       0  4982.2     .07       0  4988.2     .12       0
  5136.2     .05       0  6324.9     .08       0  6432.7     .05       0
Bank Sta=4977.6,5030.9
XS Rating Curve= 0 ,0
Exp/Cntr=0.3,0.1

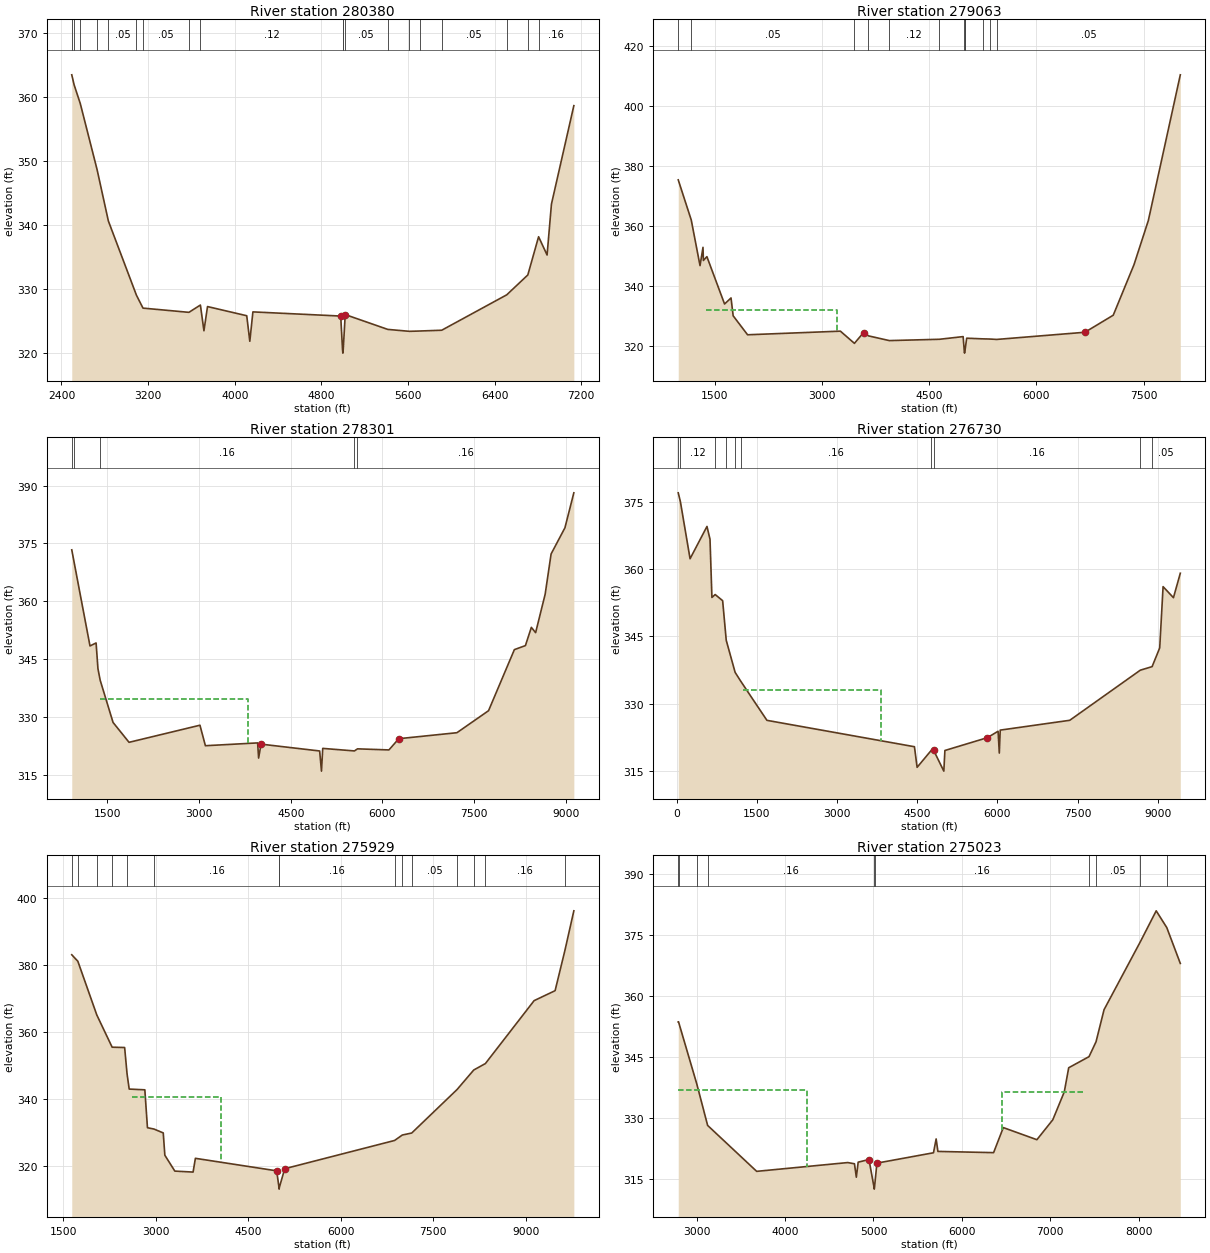
Type RM Length L Ch R = 1 ,280380  ,1317,1317,1317
BEGIN DESCRIPTION:
Mapping XS 9b2fd325
END DESCRIPTION:
XS GIS Cut Line= 3
      3621769.05     10588999.42      3622541.62      10587315.4
      3622185.74     10584555.12
#Sta/Elev= 30
  2494.9   363.4  2516.4  361.85  2573.5  358.92  2728.5  348.63  2832.8  340.61
  3092.1  329.03  3152.5  327.02  3576.6  326.36  3682.6   327.5  3715.3  323.49
  3748.3  327.26  4110.4  325.83  4138.9  321.85  4167.4  326.43  4978.1  325.78
  4995.2   320.5    4998     320  5001.2   320.5  5016.2  324.92  5018.4  326.02
  5412.6   323.7  5612.6   323.4    5712  323.45  5910.8  323.57  6511.1  329.09
  6705.9  332.19  6805.3  338.15  6883.7   335.3    6924  343.24  7130.8  358.59
#Mann= 19 ,-1 , 0
  2494.9     .05       0  2516.4     .08       0  2573.5     .05       0
  2728.5     .08       0  2832.8     .05       0  3092.1     .08       0
  3152.5     .05       0  3576.6     .07       0  3682.6     .12       0
  4995.2     .07       0  5001.2     .12       0  5016.2     .05       0
  5412.6     .07       0  5612.6     .05       0    5712     .07       0
  5910.8     .05       0  6511.1      .1       0  6705.9     .12       0
  6805.3     .16       0
Bank Sta=4978.1,5018.4
XS Rating Curve= 0 ,0
Exp/Cntr=0.3,0.1

Type RM Length L Ch R = 1 ,279063  ,762,762,762
BEGIN DESCRIPTION:
UPPER KEECHI CREEK 94.0
END DESCRIPTION:
XS GIS Cut Line= 4
      3622297.82     10590224.22      3623578.22     10586925.57
      3623556.52     10585807.94      3622494.65     10583695.04
#Sta/Elev= 30
   990.6  375.36  1172.7  361.97  1295.3  346.75  1336.9  352.85  1342.3  348.47
  1391.4  349.75  1638.5  333.94  1728.8  335.97  1758.7  330.01  1960.3  323.68
  3258.3  324.89  3454.4  320.82  3582.5  324.43  3650.6  323.32  3942.3  321.74
  4642.6  322.18  4974.5  323.07  4991.5  318.06  4994.3  317.56  4997.5  318.06
    4999  318.19  5024.5  322.54  5249.5  322.32  5347.7  322.26  5445.9  322.13
  6677.6  324.52  7073.8  330.21  7364.1  347.07    7565  361.84  8011.6   410.4
#Mann= 12 ,-1 , 0
   990.6     .16       0  1172.7     .05       0  3454.4     .16       0
  3650.6     .05       0  3942.3     .12       0  4642.6     .05       0
  4991.5     .07       0  4997.5     .05       0    4999     .07       0
  5249.5     .12       0  5347.7     .07       0  5445.9     .05       0
#XS Ineff= 1 ,-1
 1380.68 3206.25  331.79
Permanent Ineff=
       F
Bank Sta=3582.5,6677.6
XS Rating Curve= 0 ,0
Exp/Cntr=0.3,0.1

Type RM Length L Ch R = 1 ,278301  ,1571,1571,1571
BEGIN DESCRIPTION:
UPPER KEECHI CREEK 93.0
END DESCRIPTION:
XS GIS Cut Line= 4
       3622547.4     10590278.45      3624175.01     10586903.86
      3624316.07     10586014.11      3622992.38     10582704.89
#Sta/Elev= 30
     919  373.35   957.1  370.16  1217.1  348.46  1316.8  349.24  1347.2  342.58
  1383.4   339.6  1594.3  328.65  1855.8   323.5  3015.4  327.93  3104.6  322.62
  3959.1  323.35  3974.9  319.42  4014.6  323.03  4973.1  321.26  5003.2  316.04
  5023.7  321.93    5542  321.27  5592.1  321.81  6106.4  321.53  6267.9  324.44
  7218.5  325.99  7735.5  331.69  8158.1  347.51  8338.5  348.55  8435.6  353.27
  8505.5   351.9  8661.6  361.87  8758.7  372.29  8984.7  379.06  9130.6  388.12
#Mann= 5 ,-1 , 0
     919     .16       0   957.1     .05       0  1383.4     .16       0
    5542     .07       0  5592.1     .16       0
#XS Ineff= 1 ,-1
 1386.36 3795.45334.6347
Permanent Ineff=
       F
Bank Sta=4014.6,6267.9
XS Rating Curve= 0 ,0
Exp/Cntr=0.3,0.1

Type RM Length L Ch R = 1 ,276730  ,801,801,801
BEGIN DESCRIPTION:
UPPER KEECHI CREEK 92.0
END DESCRIPTION:
XS GIS Cut Line= 4
      3626383.53     10591153.28      3625563.24     10589968.41
      3625574.75     10586209.42      3623799.61     10582410.19
#Sta/Elev= 30
    28.9  376.99    68.8  375.05   250.4   362.3   566.7   369.5   623.4  366.63
   659.2  353.67   719.9  354.32   859.7  352.95     927  344.12  1093.4  336.97
  1199.1  334.99  1688.2  326.28  4448.2   320.4  4498.2  315.81  4762.4  319.58
  4808.2  319.69  4818.2  319.34    4998  314.96  5018.2  319.56  5813.2  322.42
  6013.1  323.85    6036  318.98  6053.3   324.1  7354.2  326.29  8674.2  337.46
  8894.8  338.25  9037.2  342.43  9100.2  356.08  9294.1  353.62  9422.5  359.07
#Mann= 10 ,-1 , 0
    28.9     .16       0    68.8     .12       0   719.9      .1       0
     927     .05       0  1093.4     .12       0  1199.1     .16       0
  4762.4     .07       0  4818.2     .16       0  8674.2      .1       0
  8894.8     .05       0
#XS Ineff= 1 ,-1
 1238.64 3818.18333.1532
Permanent Ineff=
       T
Bank Sta=4808.2,5813.2
XS Rating Curve= 0 ,0
Exp/Cntr=0.3,0.1

Type RM Length L Ch R = 1 ,275929  ,906,906,906
BEGIN DESCRIPTION:
UPPER KEECHI CREEK 91.0
END DESCRIPTION:
XS GIS Cut Line= 3
       3627234.9     10589800.99      3626204.09     10586795.36
      3625987.08     10581836.59
#Sta/Elev= 30
  1640.4  382.95  1738.7  381.02    2046  365.03  2294.9  355.41  2497.6  355.31
  2536.7   347.5  2571.6  342.93  2825.3  342.71  2867.6  331.42  2973.3  331.02
  3123.7  329.87  3149.7  323.22  3311.6  318.49  3607.6   318.2  3644.8   322.3
  4963.2  318.57  5000.2  313.62    5003  313.12  5006.2  313.62  5093.3   319.2
    6875  327.62  7000.1  329.24  7152.9  329.84  7887.6  342.79  8158.2  348.61
  8347.1  350.53  9137.2  369.28  9477.5  372.25  9633.4  383.99  9781.4  396.04
#Mann= 15 ,-1 , 0
  1640.4      .1       0  1738.7     .05       0    2046     .05       0
  2294.9     .05       0  2536.7      .1       0  2973.3     .16       0
  5000.2     .03       0  5006.2     .16       0    6875     .05       0
  7000.1     .16       0  7152.9     .05       0  7887.6      .1       0
  8158.2     .05       0  8347.1     .16       0  9633.4     .05       0
#XS Ineff= 1 ,-1
 2619.32 4068.18  340.43
Permanent Ineff=
       F
Bank Sta=4963.2,5093.3
XS Rating Curve= 0 ,0
Exp/Cntr=0.3,0.1

Type RM Length L Ch R = 1 ,275023  ,1447,1447,1447
BEGIN DESCRIPTION:
UPPER KEECHI CREEK 90.0
END DESCRIPTION:
XS GIS Cut Line= 3
       3627499.6     10589010.17      3626896.26     10587011.18
      3626792.09     10583417.45
#Sta/Elev= 30
    2790  353.71  2793.1  353.74  3000.5  338.41  3122.8  328.25  3677.9  316.96
  4708.7  319.12  4785.1  318.82    4806  315.52  4826.9  319.22  4949.1  319.87
  5006.1  313.09  5008.9  312.59  5012.1  313.09  5039.1  318.98  5679.4  321.53
  5709.4  324.93  5729.4  321.86  6359.7  321.56  6469.7  327.72  6849.9  324.74
    7030  329.64    7160   336.5    7210  342.43  7440.1  345.16  7519.6  348.83
  7610.2  356.71  8022.4  373.47  8200.4  381.01  8320.4  376.88  8473.3  368.08
#Mann= 10 ,-1 , 0
    2790     .12       0  2793.1     .07       0  3000.5     .16       0
  3122.8     .16       0  5006.1     .07       0  5012.1     .16       0
  7440.1     .08       0  7519.6     .05       0  8022.4     .16       0
  8320.4     .12       0
#XS Ineff= 2 ,-1
 2692.05 4243.18  336.97 6458.52  7389.2  336.36
Permanent Ineff=
       F       F
Bank Sta=4949.1,5039.1
XS Rating Curve= 0 ,0
Exp/Cntr=0.3,0.1

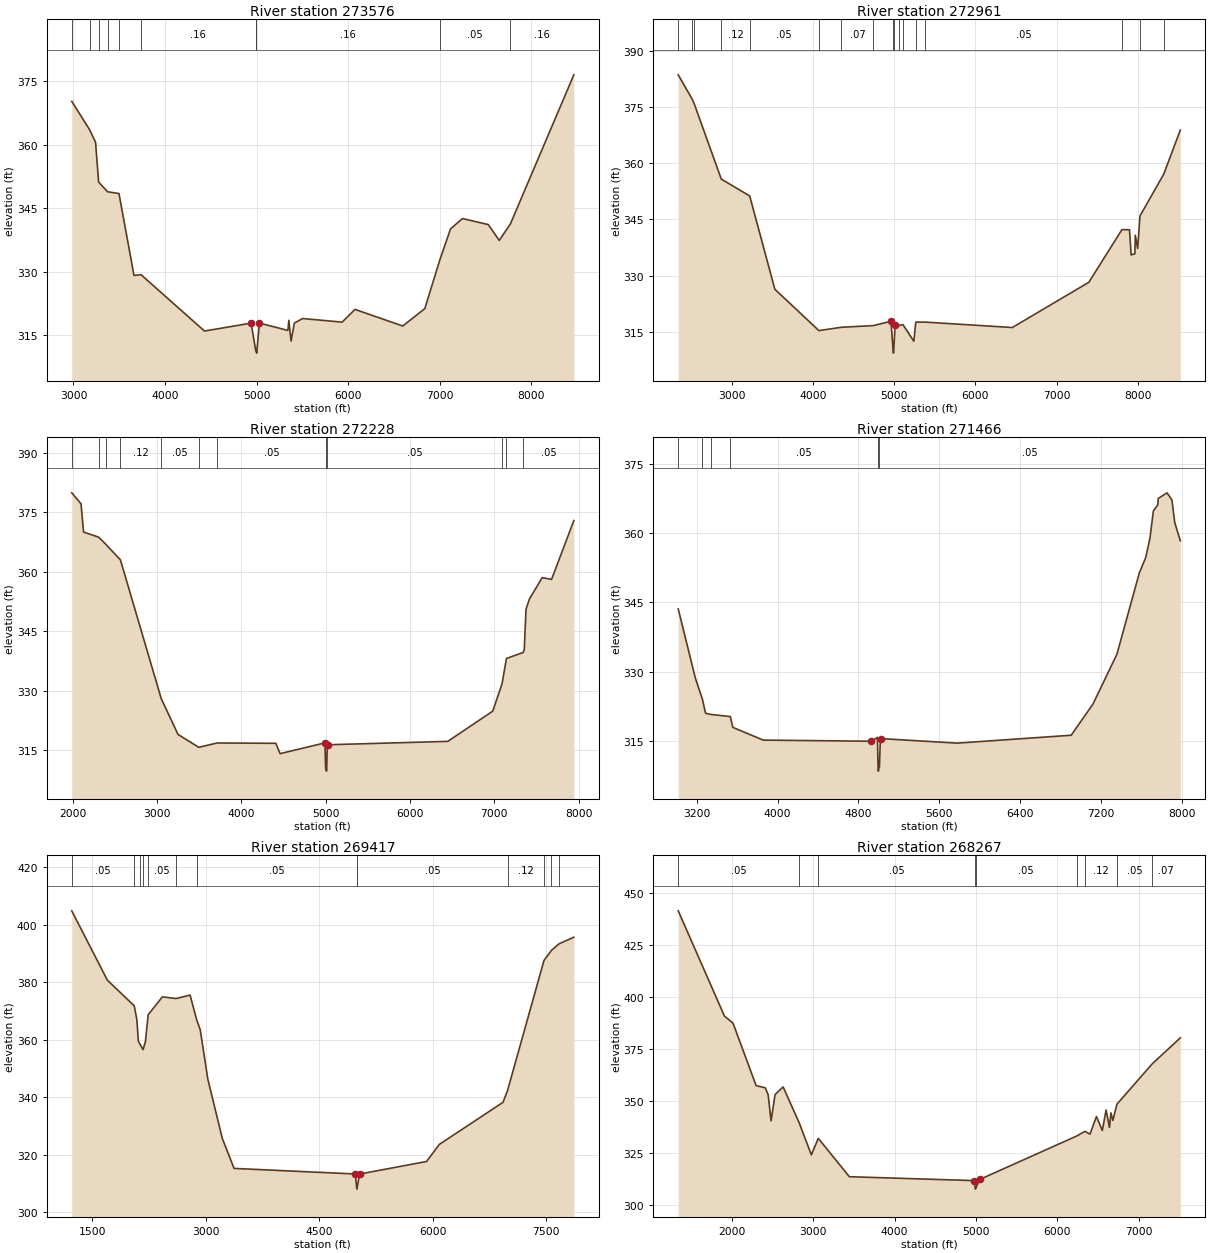
Type RM Length L Ch R = 1 ,273576  ,615,615,615
BEGIN DESCRIPTION:
UPPER KEECHI CREEK 89.0
END DESCRIPTION:
XS GIS Cut Line= 3
      3627699.61     10589210.19      3627699.61     10587210.19
      3627391.05     10583738.58
#Sta/Elev= 30
  2981.7   370.3  3176.9  363.59  3241.7  360.63    3275  351.22  3373.1  348.92
  3497.3  348.51  3661.7  329.14  3737.6  329.33  4431.7  315.99  4941.7  317.86
  4991.7  311.33  4998.8  311.27  5001.5  310.77  5031.9  317.88  5343.1  316.14
  5353.2  318.54  5377.6  313.63  5413.4  317.88  5503.8  318.95  5935.4   318.1
    6076  321.11  6598.1  317.18    6839   321.3  6999.6  332.59  7120.1  340.16
  7250.6  342.59  7531.7  341.17  7652.2  337.42  7774.1  341.33    8467  376.57
#Mann= 10 ,-1 , 0
  2981.7     .12       0  3176.9     .07       0    3275     .08       0
  3373.1      .1       0  3497.3     .07       0  3737.6     .16       0
  4991.7     .07       0  4998.8     .16       0  6999.6     .05       0
  7774.1     .16       0
Bank Sta=4941.7,5031.9
XS Rating Curve= 0 ,0
Exp/Cntr=0.3,0.1

Type RM Length L Ch R = 1 ,272961  ,733,733,733
BEGIN DESCRIPTION:
UPPER KEECHI CREEK 88.0
END DESCRIPTION:
XS GIS Cut Line= 3
      3628536.87     10589563.22      3628099.61     10586910.19
       3627903.2     10583426.14
#Sta/Elev= 30
  2342.9  383.54  2518.4  376.92  2540.3  375.78  2872.4  355.74  3222.2  351.24
  3531.8  326.36  4073.7  315.33  4351.6  316.22    4743  316.66  4960.8  317.81
  4988.2  309.82  4990.9  309.32  4994.2  309.82  5011.5  316.78    5059  316.68
  5108.3  316.92  5242.1  312.48  5266.1  317.59  5382.9  317.59    6454  316.15
  7395.5  328.21  7802.7  342.25  7896.3  342.22  7916.3  335.51  7962.3  335.83
  7967.3  340.75  7996.4  337.22    8025   345.9  8317.5  357.06  8521.3  368.81
#Mann= 17 ,-1 , 0
  2342.9     .05       0  2518.4     .16       0  2540.3     .05       0
  2872.4     .12       0  3222.2     .05       0  4073.7     .12       0
  4351.6     .07       0    4743     .12       0  4988.2     .07       0
  4994.2     .12       0    5059     .07       0  5108.3     .12       0
  5266.1     .07       0  5382.9     .05       0  7802.7     .16       0
    8025     .05       0  8317.5     .16       0
Bank Sta=4960.8,5011.5
XS Rating Curve= 0 ,0
Exp/Cntr=0.3,0.1

Type RM Length L Ch R = 1 ,272228  ,762,762,762
BEGIN DESCRIPTION:
UPPER KEECHI CREEK 87.0
END DESCRIPTION:
XS GIS Cut Line= 3
      3628599.61     10589460.22      3628599.61     10586460.19
      3628163.62     10583538.98
#Sta/Elev= 30
  1988.9  379.94  2098.9  377.17  2128.9  370.04  2308.1  368.75  2390.5  366.99
  2565.8  363.02  3049.3  328.03  3248.9  318.96  3495.4  315.71  3712.1   316.8
  4408.9  316.72  4458.9  314.11  4991.5  316.83    4999  310.37  5006.2   310.2
  5008.9   309.7  5012.2   310.2  5018.5  315.86  5029.4  316.36  6447.7  317.21
  6980.8  324.84  7090.6   331.7    7143  338.12  7342.5  339.66  7354.9  340.42
  7375.1  350.55  7415.5  353.13  7567.2  358.54  7678.4   358.1  7942.5  372.94
#Mann= 12 ,-1 , 0
  1988.9     .05       0  2308.1     .08       0  2390.5     .05       0
  2565.8     .12       0  3049.3     .05       0  3495.4     .12       0
  3712.1     .05       0  5006.2     .03       0  5012.2     .05       0
  7090.6     .08       0    7143      .1       0  7342.5     .05       0
Bank Sta=4991.5,5029.4
XS Rating Curve= 0 ,0
Exp/Cntr=0.3,0.1

Type RM Length L Ch R = 1 ,271466  ,2049,2049,2049
BEGIN DESCRIPTION:
UPPER KEECHI CREEK 86.0
END DESCRIPTION:
XS GIS Cut Line= 3
      3629199.61     10588510.16      3629199.61     10586510.19
      3628545.56     10583617.07
#Sta/Elev= 30
  3017.1  343.58  3187.1  328.54  3256.3  324.02  3287.1  320.99  3336.4  320.74
  3532.6  320.26  3557.1  317.93  3857.1  315.17  4927.1  314.92  4987.1  315.75
  4994.1  308.95  4996.8  308.45  5000.1  308.95  5007.1  309.33  5014.6  314.36
  5027.3  315.49  5775.7  314.51  6903.9  316.22  7118.8  322.95  7356.2  333.76
  7577.2  351.32  7641.7  354.74  7682.7  358.88    7717   364.8  7760.2  366.11
  7765.3   367.5  7851.7  368.71    7900  367.18  7928.7  362.22  7983.2  358.34
#Mann= 6 ,-1 , 0
  3017.1     .05       0  3256.3      .1       0  3336.4     .15       0
  3532.6     .05       0  4994.1     .03       0  5000.1     .05       0
Bank Sta=4927.1,5027.3
XS Rating Curve= 0 ,0
Exp/Cntr=0.3,0.1

Type RM Length L Ch R = 1 ,269417  ,1150,1150,1150
BEGIN DESCRIPTION:
UPPER KEECHI CREEK 85.0
END DESCRIPTION:
XS GIS Cut Line= 4
      3633033.38     10587740.33      3631783.41     10586889.65
       3630047.3     10584875.76      3629752.16     10582427.88
#Sta/Elev= 30
  1229.4  404.81  1700.2  380.67  2055.2  371.76  2089.2  367.03  2110.2  359.41
  2132.1  358.36  2171.7  356.52    2203   359.3  2239.7  368.67  2427.4  374.88
  2606.5  374.29  2793.5  375.49  2879.6  366.98  2927.7  363.42  3027.5  346.29
  3218.4  325.68  3374.4  315.18  4977.1  313.24  4995.4  308.47  4998.1  307.97
  5001.4  308.47  5034.1  313.22  5919.3  317.59  6088.4  323.54  6929.2  338.17
  6989.8  342.31  7471.3  387.54  7570.5  391.07  7669.8  393.31  7865.9  395.64
#Mann= 13 ,-1 , 0
  1229.4     .05       0  2055.2      .1       0  2132.1     .15       0
  2171.7     .08       0  2239.7     .05       0  2606.5     .16       0
  2879.6     .05       0  4995.4     .03       0  5001.4     .05       0
  6989.8     .12       0  7471.3     .08       0  7570.5     .16       0
  7669.8     .05       0
Bank Sta=4977.1,5034.1
XS Rating Curve= 0 ,0
Exp/Cntr=0.3,0.1

Type RM Length L Ch R = 1 ,268267  ,1256,1256,1256
BEGIN DESCRIPTION:
Mapping XS 9efa5d94
END DESCRIPTION:
XS GIS Cut Line= 3
      3633519.53     10587462.57      3631453.55     10585535.48
      3630516.26     10582324.41
#Sta/Elev= 30
  1340.5  441.32  1908.2  390.75  2014.2   387.3  2297.5  357.29  2410.4  356.24
    2446  352.86  2481.2  340.35  2530.6  352.99  2629.7  356.67  2826.9  339.43
  2976.6  324.01  3061.7  331.94  3443.6   313.5  4973.4  311.63  4991.2  308.03
    4994  307.53  4997.2  308.03  5046.3  312.19  6235.9  333.03  6339.3  335.31
  6400.6  333.97  6480.2  342.44  6552.4   335.7  6598.5  345.59  6640.1  337.18
    6658  344.19  6681.8  340.56  6731.9  348.36  7166.1  367.77  7510.8  380.25
#Mann= 9 ,-1 , 0
  1340.5     .05       0  2826.9     .16       0  3061.7     .05       0
  4991.2     .03       0  4997.2     .05       0  6235.9     .07       0
  6339.3     .12       0  6731.9     .05       0  7166.1     .07       0
Bank Sta=4973.4,5046.3
XS Rating Curve= 0 ,0
Exp/Cntr=0.3,0.1