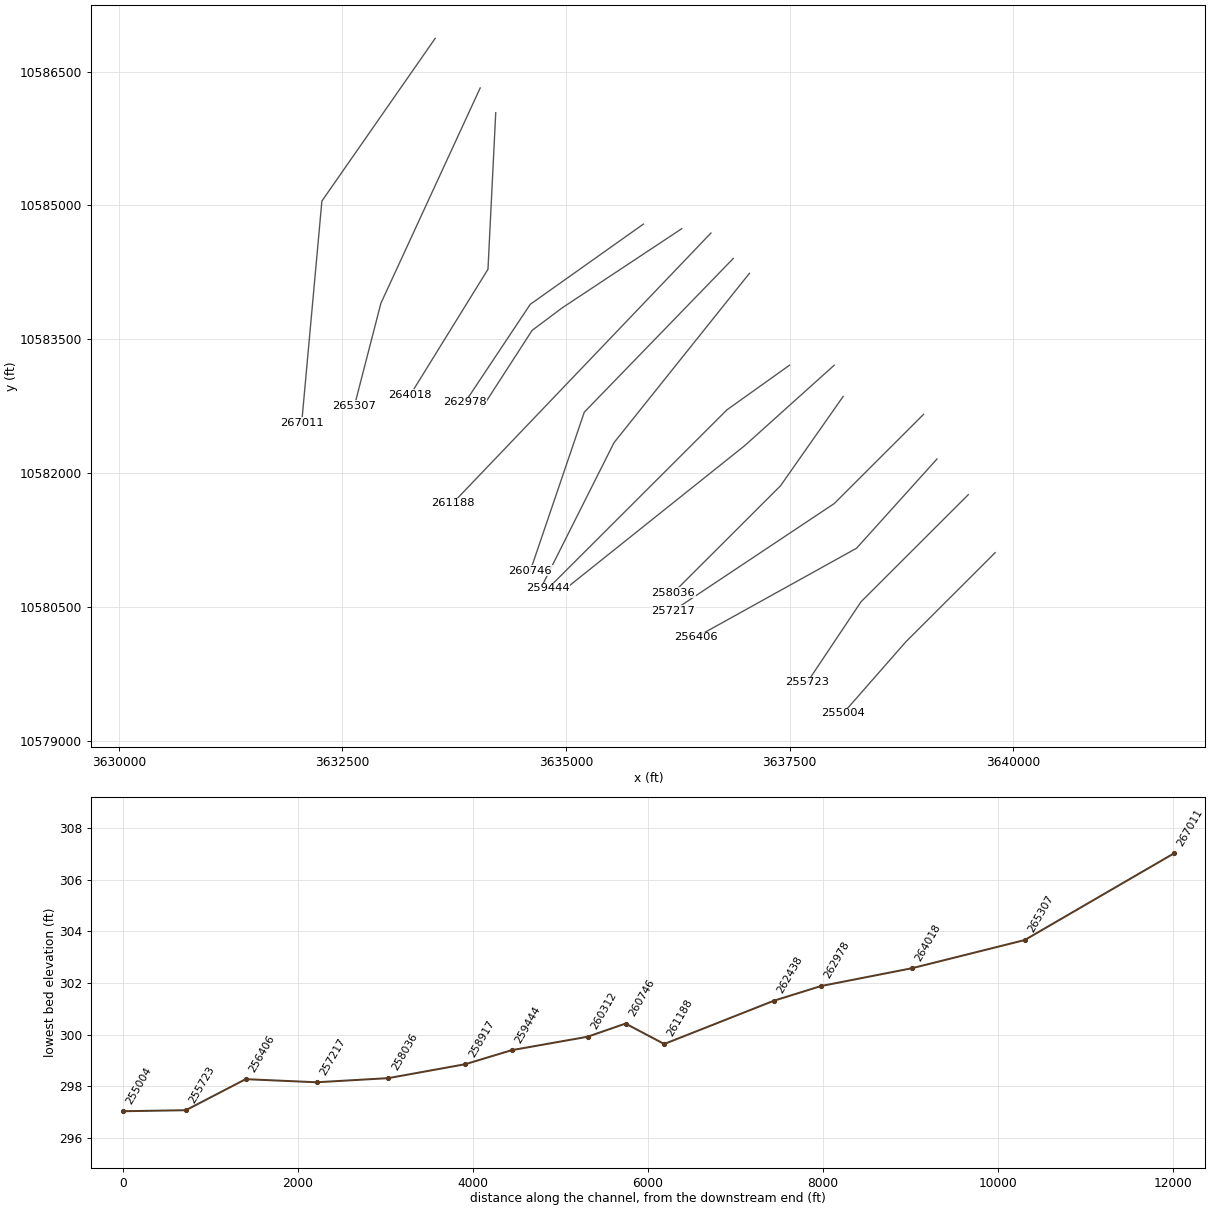
HEC-RAS study UPPER KEECHI CREEK.prj: UPPER KEECHI CREEK Base Level Engineering

--- UPPER KEECHI CREEK.g01 (geometry) --- (continued)

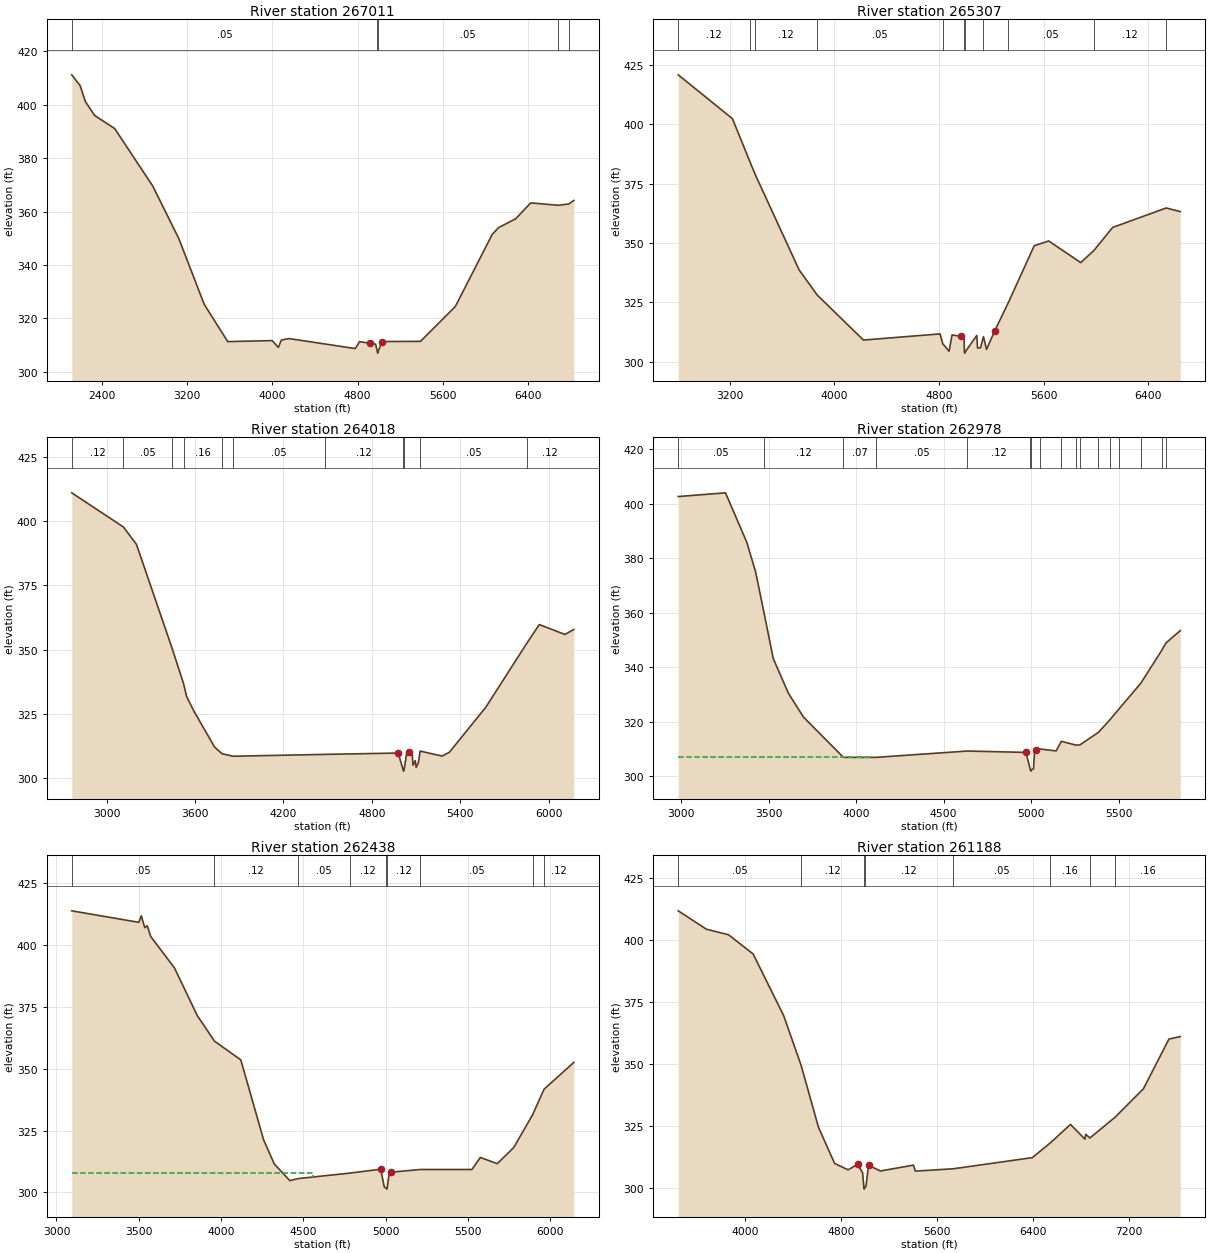
Type RM Length L Ch R = 1 ,267011  ,1704,1704,1704
BEGIN DESCRIPTION:
Mapping XS 1e2b9118
END DESCRIPTION:
XS GIS Cut Line= 3
      3633536.89     10586872.31      3632269.52     10585049.37
      3632043.82     10582566.72
#Sta/Elev= 30
  2117.7  411.22  2195.6  407.22  2246.2  401.17  2332.7  395.98  2520.4  391.11
  2878.2  369.56  3122.7  349.89    3361  325.28  3581.8  311.33  3999.1   311.7
  4056.8  309.15  4085.5  311.92  4157.1  312.46  4778.9  308.72  4819.1  311.31
  4919.5   310.7  4969.7  310.36  4986.8  307.51  4989.5  307.01  4992.8  307.51
  5029.9  311.34  5391.4  311.42  5717.7  324.43  6064.2  351.43  6124.4  354.02
  6285.1  357.33  6425.7  363.26  6685.3  362.37  6784.1  362.87  6830.8  364.19
#Mann= 5 ,-1 , 0
  2117.7     .05       0  4986.8     .03       0  4992.8     .05       0
  6685.3     .16       0  6784.1     .12       0
Bank Sta=4919.5,5029.9
XS Rating Curve= 0 ,0
Exp/Cntr=0.3,0.1

Type RM Length L Ch R = 1 ,265307  ,1289,1289,1289
BEGIN DESCRIPTION:
Mapping XS 6d96b0ab
END DESCRIPTION:
XS GIS Cut Line= 3
      3634040.34     10586316.71      3632929.24     10583903.54
      3632634.36     10582758.69
#Sta/Elev= 30
    2807  420.77  3221.5  402.32    3353  384.49  3396.6  378.71  3731.4  338.67
  3869.8  328.11  4223.3  309.15  4808.8  311.76  4829.9  307.58  4877.7  304.46
  4900.7   311.3  4969.5  310.74  4992.5  310.38    4995  304.16  4997.8  303.66
    5001  304.16  5089.9  311.11  5095.4  305.81  5118.3   305.9  5140.7  310.57
  5164.3  305.25  5225.2  312.79  5332.2  325.06  5529.1  348.86  5640.1  350.85
  5884.3  341.75  5985.1  346.84  6128.4  356.54    6538  364.74  6645.9  363.21
#Mann= 11 ,-1 , 0
    2807     .12       0    3353     .05       0  3396.6     .12       0
  3869.8     .05       0  4829.9     .12       0    4995     .07       0
    5001     .12       0  5140.7     .16       0  5332.2     .05       0
  5985.1     .12       0    6538     .16       0
Bank Sta=4969.5,5225.2
XS Rating Curve= 0 ,0
Exp/Cntr=0.3,0.1

Type RM Length L Ch R = 1 ,264018  ,1040,1040,1040
BEGIN DESCRIPTION:
Mapping XS df26c140
END DESCRIPTION:
XS GIS Cut Line= 3
      3634213.97     10586038.98      3634127.16     10584285.48
      3633259.12     10582879.26
#Sta/Elev= 30
    2763  411.13  3113.9  397.79  3202.3     391  3445.3  350.27    3522  336.67
  3542.7  331.63  3592.8   325.9    3733  311.92  3783.5  309.34  3859.1  308.38
  4480.3   309.1  4978.9  309.62  5012.5  303.07  5015.3  302.57  5018.5  303.07
  5036.8  309.63  5052.2  310.08  5073.5  309.47  5079.3  304.89  5094.7  306.67
  5100.7  303.99    5116  305.83  5127.8  310.39    5277  308.44  5326.5  309.94
  5573.6  327.49  5851.9  352.45  5936.6  359.73  6111.4  355.88  6171.2  357.83
#Mann= 11 ,-1 , 0
    2763     .12       0  3113.9     .05       0  3445.3     .12       0
    3522     .16       0  3783.5     .12       0  3859.1     .05       0
  4480.3     .12       0  5012.5     .07       0  5018.5     .12       0
  5127.8     .05       0  5851.9     .12       0
Bank Sta=4978.9,5052.2
XS Rating Curve= 0 ,0
Exp/Cntr=0.3,0.1

Type RM Length L Ch R = 1 ,262978  ,540,540,540
BEGIN DESCRIPTION:
Mapping XS 1783929d
END DESCRIPTION:
XS GIS Cut Line= 3
      3635865.46     10584791.14      3634600.25     10583892.69
      3633871.07     10582795.45
#Sta/Elev= 30
  2983.5  402.63  3253.6  403.99  3375.4  385.82  3425.8  374.96  3472.5  360.33
  3526.7  343.15  3612.8  330.49  3698.9  321.73  3927.5  306.93  4111.4  306.92
  4635.4  309.25  4970.5  308.75  4995.8  302.38  4998.6  301.88  5001.8  302.38
  5013.9  302.71  5019.9  309.42  5028.9  309.73  5051.6  309.99  5143.1   309.3
    5173  312.81  5258.3   311.4  5279.4  311.53  5385.1  316.13  5448.2  320.57
  5502.5  324.71  5626.9  334.12  5747.8  346.32  5770.2  348.88  5852.7  353.45
#Mann= 17 ,-1 , 0
  2983.5     .05       0  3472.5     .12       0  3927.5     .07       0
  4111.4     .05       0  4635.4     .12       0  4995.8     .07       0
  5001.8     .12       0  5051.6     .05       0    5173     .16       0
  5258.3     .05       0  5279.4     .16       0  5385.1     .05       0
  5448.2     .16       0  5502.5     .05       0  5626.9     .16       0
  5747.8     .12       0  5770.2     .05       0
#XS Ineff= 2 , 0
       0 4098.95  307.11               0
Permanent Ineff=
       T       F
Bank Sta=4970.5,5028.9
XS Rating Curve= 0 ,0
Exp/Cntr=0.3,0.1

Type RM Length L Ch R = 1 ,262438  ,1250,1250,1250
BEGIN DESCRIPTION:
Mapping XS 119abd0f
END DESCRIPTION:
XS GIS Cut Line= 4
      3636294.67     10584739.89      3634954.42     10583851.02
      3634621.08     10583601.02       3634065.5     10582739.87
#Sta/Elev= 30
    3093  413.77  3500.3  409.12  3515.3  411.78  3536.4  406.96  3551.4  407.74
  3572.5   403.4  3716.9   390.7    3855  371.48  3959.9  361.11  4119.9  353.52
  4258.2  321.24    4323   311.5  4417.6  304.75  4466.7  305.56  4781.1  307.78
  4969.7  309.35  4991.4   302.1    5003  301.81  5005.7  301.31    5009  301.81
  5019.7  306.83    5033  308.15    5209  309.23  5523.5  309.25  5574.8  314.11
  5677.7   311.6  5777.4   318.1  5892.8  331.42  5961.7  341.69  6142.7  352.53
#Mann= 9 ,-1 , 0
    3093     .05       0  3959.9     .12       0  4466.7     .05       0
  4781.1     .12       0    5003     .07       0    5009     .12       0
    5209     .05       0  5892.8     .16       0  5961.7     .12       0
#XS Ineff= 2 , 0
       0  4560.9   307.7               0
Permanent Ineff=
       T       F
Bank Sta=4969.7,5033
XS Rating Curve= 0 ,0
Exp/Cntr=0.3,0.1

Type RM Length L Ch R = 1 ,261188  ,442,442,442
BEGIN DESCRIPTION:
UPPER KEECHI CREEK 84.0
END DESCRIPTION:
XS GIS Cut Line= 2
      3636621.09     10584691.31      3633732.18     10581663.51
#Sta/Elev= 30
  3445.6  411.78    3681  404.36  3864.7  402.14  4069.7  394.41  4324.5  369.54
  4470.7   349.4  4614.5  324.58  4748.8     310    4862  307.41  4939.9   309.6
  4982.1   306.3  4993.3  300.14    4996  299.64  4999.3  300.14  5010.5  300.78
  5031.9  309.24  5130.9  306.95  5406.8  309.32  5420.9   306.9  5736.6  307.83
  6396.9  312.33  6548.4  318.33  6715.2  325.72  6835.3  319.78  6842.5  321.74
  6876.8  320.23  7085.1  328.55  7323.4   340.1  7535.7  360.11  7630.5  361.11
#Mann= 8 ,-1 , 0
  3445.6     .05       0  4470.7     .12       0  4993.3     .07       0
  4999.3     .12       0  5736.6     .05       0  6548.4     .16       0
  6876.8     .05       0  7085.1     .16       0
Bank Sta=4939.9,5031.9
XS Rating Curve= 0 ,0
Exp/Cntr=0.3,0.1

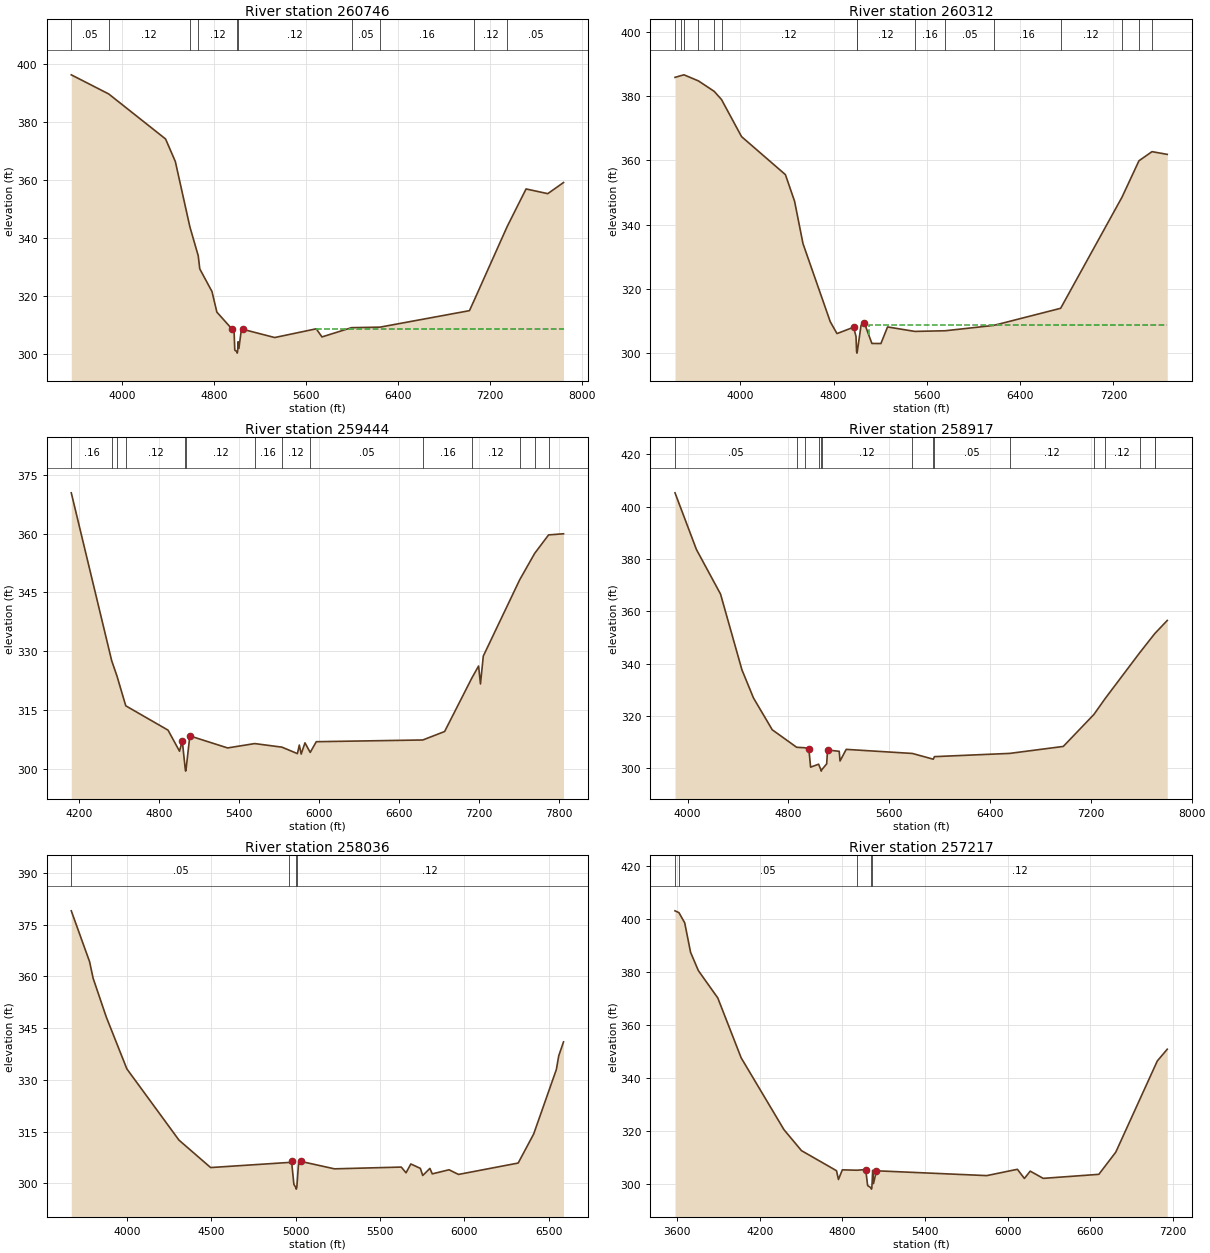
Type RM Length L Ch R = 1 ,260746  ,434,434,434
BEGIN DESCRIPTION:
Mapping XS b4ea11da
END DESCRIPTION:
XS GIS Cut Line= 3
      3636871.06     10584406.55      3635204.42     10582684.36
      3634600.26     10580906.61
#Sta/Elev= 30
  3561.3  396.29  3886.1  389.71    4380   374.2  4464.9  366.43  4590.8  343.99
  4663.8  333.95  4677.1  329.45  4783.1  321.65  4825.6  314.55  4960.1  308.59
  4974.3  308.46  4981.2  301.47  4999.5  300.93  5002.3  300.43  5005.5  300.93
  5009.5  304.34  5016.7  302.02  5037.8  308.44  5051.9  308.63  5327.7   305.8
  5688.4  308.81    5738  306.01    5995   309.2  6242.1  309.38  7018.8  315.06
    7057  318.39  7347.7  344.15  7510.4  356.98  7698.7  355.36  7835.5  359.19
#Mann= 10 ,-1 , 0
  3561.3     .05       0  3886.1     .12       0  4590.8      .1       0
  4663.8     .12       0  4999.5     .07       0  5005.5     .12       0
    5995     .05       0  6242.1     .16       0    7057     .12       0
  7347.7     .05       0
#XS Ineff= 2 , 0
       0                 5686.52       0  308.81
Permanent Ineff=
       F       T
Bank Sta=4960.1,5051.9
XS Rating Curve= 0 ,0
Exp/Cntr=0.3,0.1

Type RM Length L Ch R = 1 ,260312  ,868,868,868
BEGIN DESCRIPTION:
Mapping XS fb20b630
END DESCRIPTION:
XS GIS Cut Line= 3
      3637051.67     10584239.95      3635537.75     10582344.08
      3634732.21     10580739.94
#Sta/Elev= 30
  3439.9  385.86  3489.9  386.39  3516.9  386.65  3641.1  384.75    3776   381.5
  3838.7  378.95  4010.6  367.39  4386.8  355.54  4465.3  347.25  4537.4  334.05
  4771.1  309.73  4828.8  306.01  4971.3  307.99  4992.1  305.12  4997.1  300.42
  4999.8  299.92  5003.1  300.42  5035.3   308.6  5064.1  309.25  5128.2  302.94
  5205.6  302.91  5262.6  308.08  5496.1  306.69  5756.7  306.89    6172  308.55
  6746.9  313.89  7273.6  348.56  7418.6  359.87  7530.5  362.71  7661.1  361.86
#Mann= 15 ,-1 , 0
  3439.9     .16       0  3489.9     .05       0  3516.9     .16       0
  3641.1     .05       0    3776     .16       0  3838.7     .12       0
  4997.1     .07       0  5003.1     .12       0  5496.1     .16       0
  5756.7     .05       0    6172     .16       0  6746.9     .12       0
  7273.6     .05       0  7418.6     .16       0  7530.5     .12       0
#XS Ineff= 2 , 0
       0                 5102.27       0  308.54
Permanent Ineff=
       F       T
Bank Sta=4971.3,5064.1
XS Rating Curve= 0 ,0
Exp/Cntr=0.3,0.1

Type RM Length L Ch R = 1 ,259444  ,527,527,527
BEGIN DESCRIPTION:
UPPER KEECHI CREEK 83.0
END DESCRIPTION:
XS GIS Cut Line= 3
      3637499.61     10583210.19      3636799.61     10582710.19
      3634799.58     10580710.16
#Sta/Elev= 30
  4143.6  370.43  4446.7  327.55  4485.9  323.69    4552  316.07  4868.7  309.86
  4954.7  304.49  4975.6  307.11  4997.8   299.9  5000.5   299.4  5003.8   299.9
  5032.1  308.39    5315  305.32  5518.1  306.43  5722.2  305.52  5838.2  303.87
  5852.4  306.06  5866.5  303.75  5894.8  306.62  5934.2  304.18  5979.6  306.91
    6778  307.35  6941.3  309.51    7146   323.2  7195.9  326.23    7210  321.65
  7231.2  328.77    7504  348.24  7616.2  354.98  7720.4  359.69  7832.3  359.98
#Mann= 14 ,-1 , 0
  4143.6     .16       0  4446.7     .12       0  4485.9     .05       0
    4552     .12       0  4997.8     .07       0  5003.8     .12       0
  5518.1     .16       0  5722.2     .12       0  5934.2     .05       0
    6778     .16       0    7146     .12       0    7504     .05       0
  7616.2     .16       0  7720.4     .12       0
Bank Sta=4975.6,5032.1
XS Rating Curve= 0 ,0
Exp/Cntr=0.3,0.1

Type RM Length L Ch R = 1 ,258917  ,881,881,881
BEGIN DESCRIPTION:
UPPER KEECHI CREEK 82.0
END DESCRIPTION:
XS GIS Cut Line= 3
      3637999.57     10583210.16      3636999.61     10582310.19
      3634999.58     10580710.17
#Sta/Elev= 30
  3899.6  405.29  4069.6  383.62  4260.9  366.58  4430.6  337.62  4522.5  326.83
  4671.3  314.68  4864.9  307.98  4929.3   307.8    4962  307.31  4975.8  300.38
  5039.3  301.51  5057.7  299.36  5060.4  298.86  5063.7  299.36  5103.3  301.64
  5110.4  306.95  5202.7  306.44  5209.4  302.74  5258.5  307.18  5783.4  305.62
  5949.4  303.42  5958.5   304.4  6555.6  305.64    6981   308.3  7223.8  320.51
  7312.4  326.55  7587.2  344.11  7706.8  351.43  7711.1  351.65  7806.2  356.48
#Mann= 15 ,-1 , 0
  3899.6     .05       0  4864.9     .12       0  4929.3     .05       0
  5039.3     .12       0  5057.7     .03       0  5063.7     .12       0
  5783.4     .05       0  5949.4     .12       0  5958.5     .05       0
  6555.6     .12       0  7223.8     .16       0  7312.4     .12       0
  7587.2     .16       0  7706.8     .05       0  7711.1     .16       0
Bank Sta=4962,5110.4
XS Rating Curve= 0 ,0
Exp/Cntr=0.3,0.1

Type RM Length L Ch R = 1 ,258036  ,819,819,819
BEGIN DESCRIPTION:
UPPER KEECHI CREEK 81.0
END DESCRIPTION:
XS GIS Cut Line= 3
      3638099.59     10582860.16      3637399.61     10581860.19
      3636199.59     10580660.17
#Sta/Elev= 30
  3670.8  378.97  3779.3  364.23  3800.2  359.45  3878.3   348.2  4000.3  333.16
  4309.4  312.51  4496.9  304.57  4963.7  306.06  4976.3  306.48  4990.4  299.68
  5001.6  298.82  5004.3  298.32  5007.6  298.82  5018.7  306.32  5032.8  306.34
  5230.8   304.2  5626.8  304.71  5655.1  303.05  5683.4  305.61  5739.9  304.34
  5754.1  302.27  5796.5  304.32  5810.7  302.74  5909.7  303.93  5966.2  302.58
  6319.8  305.88  6411.7   314.3  6546.1  332.99  6560.2  336.95  6588.5  340.99
#Mann= 4 ,-1 , 0
  3670.8     .05       0  4963.7     .12       0  5001.6     .07       0
  5007.6     .12       0
Bank Sta=4976.3,5032.8
XS Rating Curve= 0 ,0
Exp/Cntr=0.3,0.1

Type RM Length L Ch R = 1 ,257217  ,811,811,811
BEGIN DESCRIPTION:
UPPER KEECHI CREEK 80.0
END DESCRIPTION:
XS GIS Cut Line= 3
      3638999.59     10582660.17      3637999.61     10581660.19
      3636199.63      10580460.2
#Sta/Elev= 30
    3583  403.14  3611.7  402.46  3653.7  398.58  3696.1   387.5  3752.7   380.6
  3894.1  370.26  4063.8  347.69  4374.9  320.59  4502.2  312.68  4756.8  305.11
  4770.9   301.8  4799.2  305.44  4905.1  305.29  4968.9  305.55    4983   299.5
  5007.7  298.66  5010.5  298.16  5013.7  298.66  5019.7  305.25  5025.7  300.25
  5046.8  305.08    5849  303.26  6071.3  305.64  6122.4  302.18  6164.5  304.95
  6259.1  302.22  6663.3  303.74  6786.4   312.1  7088.4  346.52  7160.5  350.93
#Mann= 5 ,-1 , 0
    3583     .16       0  3611.7     .05       0  4905.1     .12       0
  5007.7     .07       0  5013.7     .12       0
Bank Sta=4968.9,5046.8
XS Rating Curve= 0 ,0
Exp/Cntr=0.3,0.1

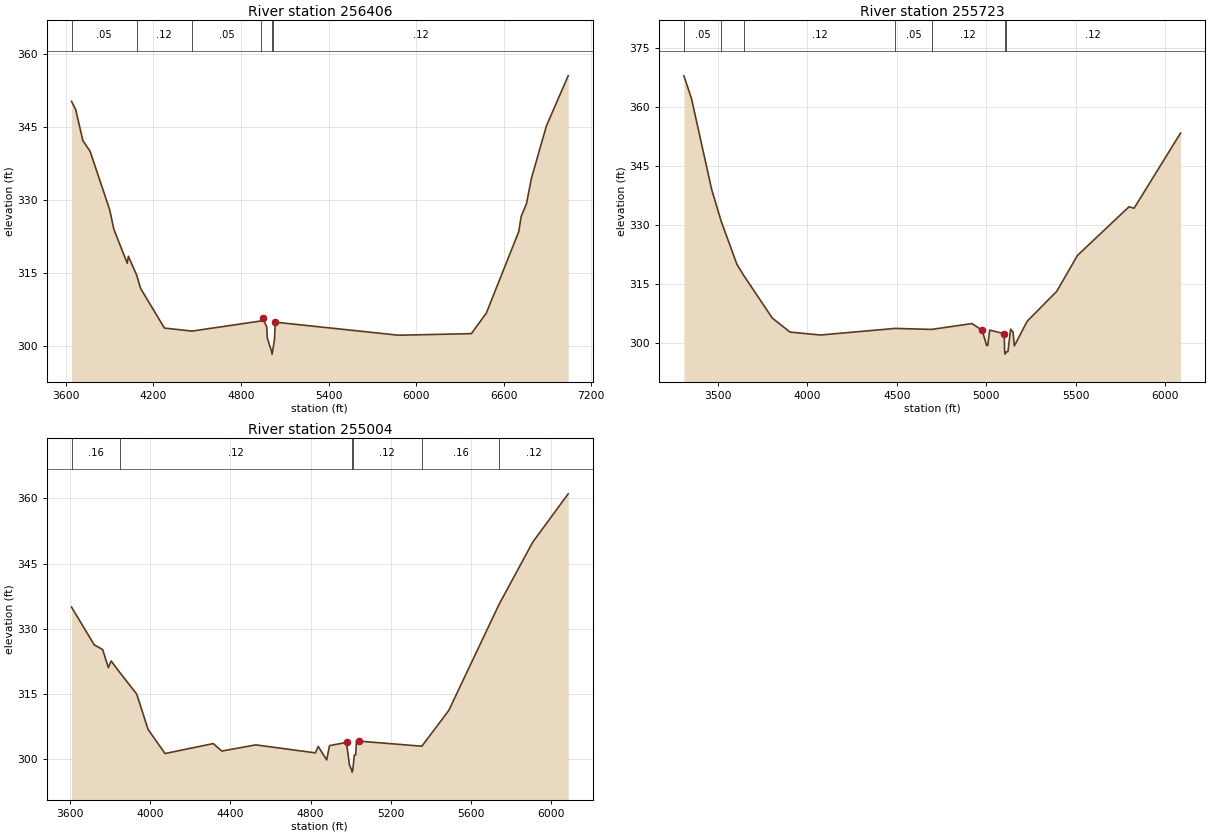
Type RM Length L Ch R = 1 ,256406  ,683,683,683
BEGIN DESCRIPTION:
UPPER KEECHI CREEK 79.0
END DESCRIPTION:
XS GIS Cut Line= 3
      3639149.58     10582160.15      3638249.61     10581160.19
      3636449.65     10580160.21
#Sta/Elev= 30
    3638  350.19    3666  348.56  3716.1  342.11  3765.4  339.93  3899.9  327.91
  3928.3  323.92  4020.3  316.93  4027.7  318.37  4084.3  314.53  4112.2  311.73
  4275.1  303.63  4464.5  303.01  4935.1  305.08  4947.8  305.69  4976.2  303.88
    4980  301.57  5010.1  298.78  5012.8  298.28  5016.1  298.78  5029.1  301.28
  5034.8  304.84  5880.2  302.16  6378.9  302.49  6481.9  306.74  6703.8  323.46
  6719.8  326.51  6756.5  329.17  6790.8  334.42  6893.7  345.19  7042.4  355.42
#Mann= 6 ,-1 , 0
    3638     .05       0  4084.3     .12       0  4464.5     .05       0
  4935.1     .12       0  5010.1     .07       0  5016.1     .12       0
Bank Sta=4947.8,5034.8
XS Rating Curve= 0 ,0
Exp/Cntr=0.3,0.1

Type RM Length L Ch R = 1 ,255723  ,719,719,719
BEGIN DESCRIPTION:
UPPER KEECHI CREEK 78.0
END DESCRIPTION:
XS GIS Cut Line= 3
      3639499.62      10581760.2      3638299.61     10580560.19
      3637699.63     10579660.21
#Sta/Elev= 30
  3309.1     368  3351.5  362.23  3464.7     339  3518.3  330.87  3606.1  319.93
  3646.7  316.94  3804.1  306.25  3903.1   302.7  4072.8  301.95  4490.9  303.63
    4695  303.38  4921.3  304.87  4977.9  303.12  5002.6   299.3  5009.2   299.3
  5019.7   303.2  5100.8   302.3  5103.8  297.58  5106.6  297.08  5109.8  297.58
  5121.8  297.71  5136.9  303.41  5150.4  302.73  5157.9  299.17    5230  305.48
  5395.3   313.1  5510.9  322.23  5799.4  334.64  5827.9  334.27  6087.8  353.43
#Mann= 7 ,-1 , 0
  3309.1     .05       0  3518.3     .16       0  3646.7     .12       0
  4490.9     .05       0    4695     .12       0  5103.8     .07       0
  5109.8     .12       0
Bank Sta=4977.9,5100.8
XS Rating Curve= 0 ,0
Exp/Cntr=0.3,0.1

Type RM Length L Ch R = 1 ,255004  ,619,619,619
BEGIN DESCRIPTION:
UPPER KEECHI CREEK 77.0
END DESCRIPTION:
XS GIS Cut Line= 3
      3639799.58     10581110.16      3638799.61     10580110.19
       3638099.6     10579310.18
#Sta/Elev= 30
  3607.8  335.01  3720.9  326.34  3763.3  325.22  3791.6  321.08  3805.7  322.61
  3849.9  319.89    3933     315  3989.6  306.87  4074.4  301.32  4314.9  303.61
  4357.3  301.88    4527  303.31    4824  301.47  4838.1  302.96  4880.5  299.85
  4894.7  303.14  4979.5  303.88  4993.7  298.77  5004.8  297.54  5007.6  297.04
  5010.8  297.54  5018.4  300.99  5025.3  300.99  5029.1  304.24  5043.3  304.17
  5355.2     303  5489.4  311.22  5740.6  335.66    5908  349.92    6085  361.05
#Mann= 6 ,-1 , 0
  3607.8     .16       0  3849.9     .12       0  5004.8     .07       0
  5010.8     .12       0  5355.2     .16       0  5740.6     .12       0
Bank Sta=4979.5,5043.3
XS Rating Curve= 0 ,0
Exp/Cntr=0.3,0.1