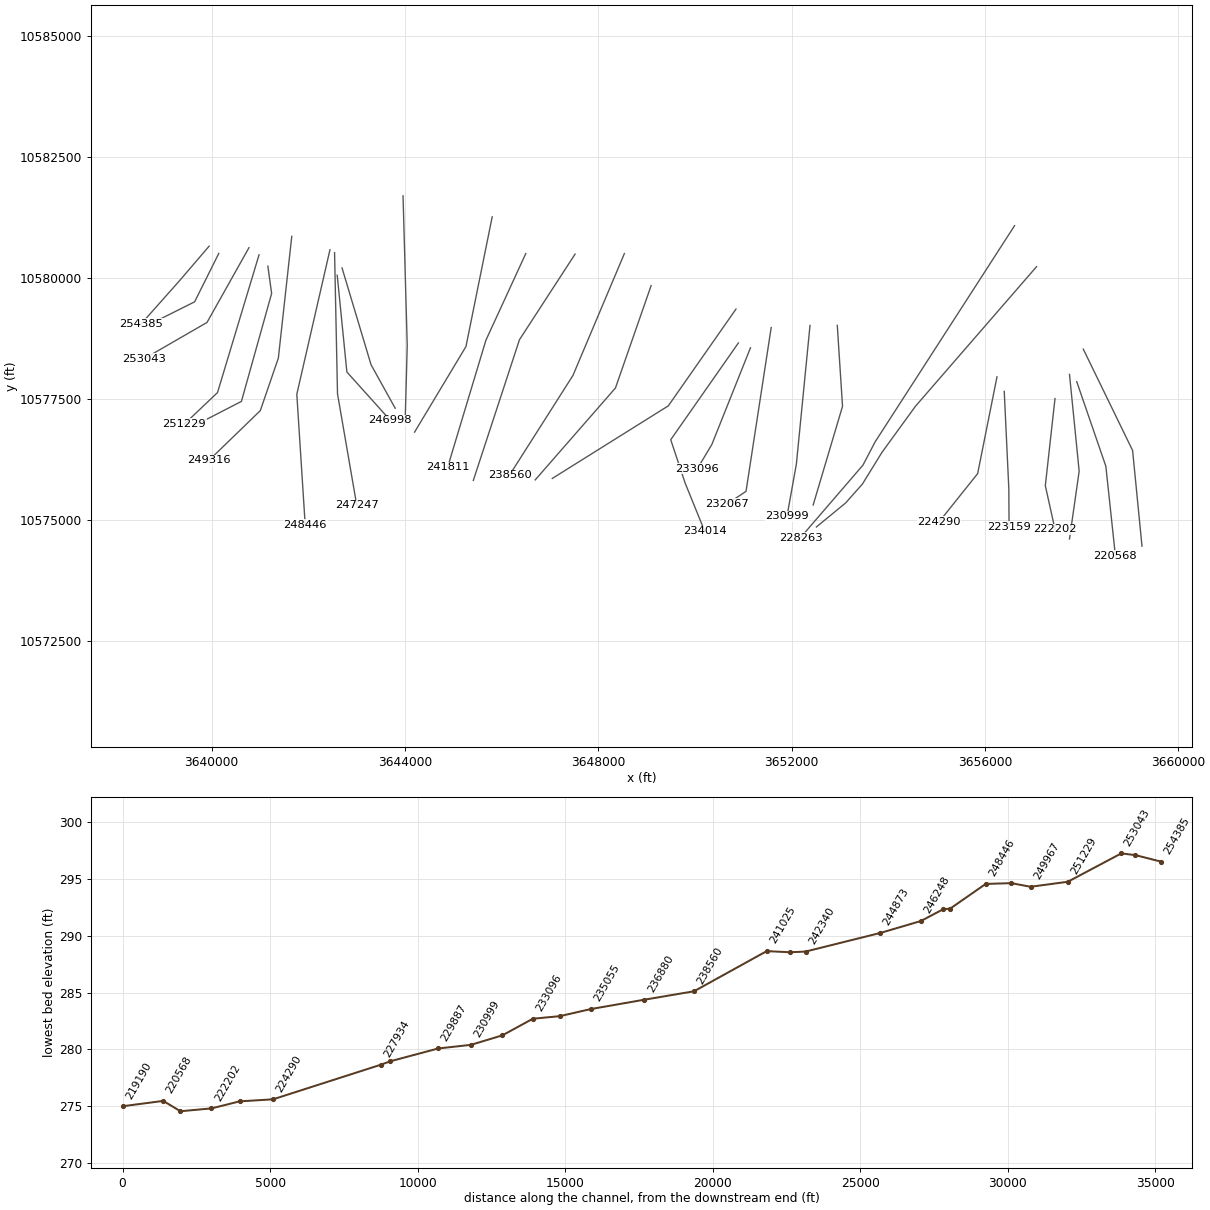
HEC-RAS study UPPER KEECHI CREEK.prj: UPPER KEECHI CREEK Base Level Engineering

--- UPPER KEECHI CREEK.g01 (geometry) --- (continued)

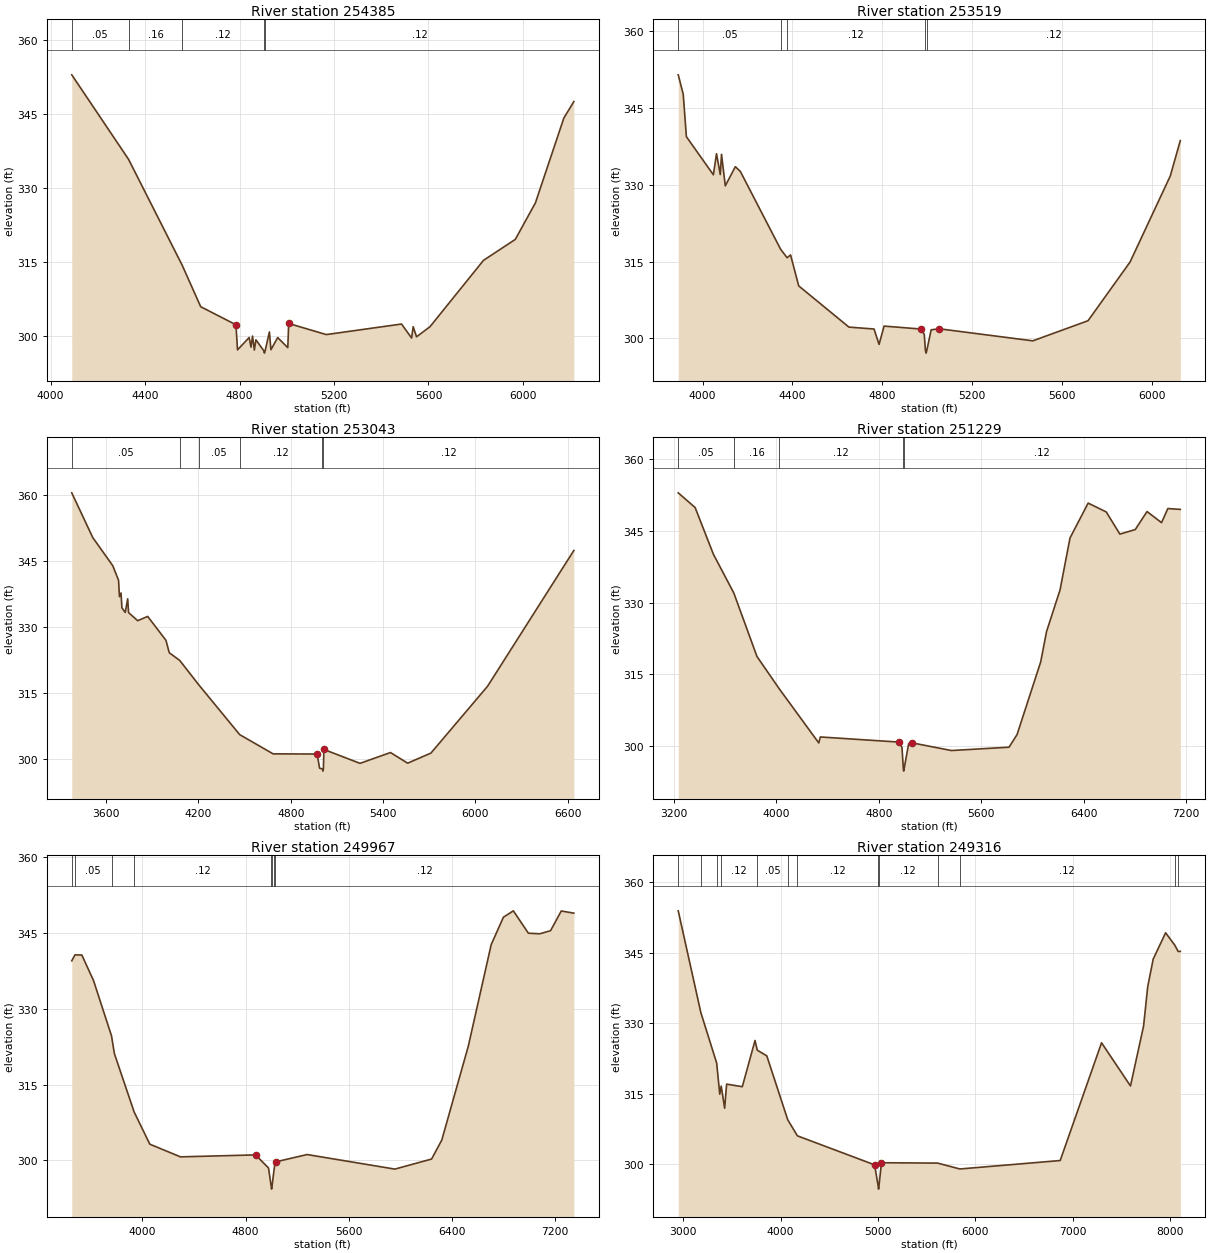
Type RM Length L Ch R = 1 ,254385  ,866,866,866
BEGIN DESCRIPTION:
UPPER KEECHI CREEK 76.0
END DESCRIPTION:
XS GIS Cut Line= 3
      3639949.58     10580660.16      3639349.61     10579960.19
      3638549.59     10579060.17
#Sta/Elev= 30
  4089.6  352.96  4330.1  335.83  4557.5  314.33  4635.6  305.95  4784.9  302.29
  4791.5   297.2  4840.8  299.71  4848.5  297.75  4855.1     300  4862.8  297.16
  4869.4  299.24  4902.6  297.04  4905.4  296.54  4908.6  297.04  4926.5  300.84
    4933  297.23  4961.6  299.69  5004.4  297.65  5008.2  302.55  5167.5   300.3
  5486.1  302.44  5528.7   299.6  5535.4  301.89  5549.6  299.85  5606.5  301.89
  5833.1  315.35  5967.7  319.59    6053     327  6173.4   344.2  6215.7  347.54
#Mann= 5 ,-1 , 0
  4089.6     .05       0  4330.1     .16       0  4557.5     .12       0
  4902.6     .07       0  4908.6     .12       0
Bank Sta=4784.9,5008.2
XS Rating Curve= 0 ,0
Exp/Cntr=0.3,0.1

Type RM Length L Ch R = 1 ,253519  ,476,476,476
BEGIN DESCRIPTION:
UPPER KEECHI CREEK 75.0
END DESCRIPTION:
XS GIS Cut Line= 3
       3640149.6     10580510.18      3639649.61     10579510.19
      3638649.57     10579010.17
#Sta/Elev= 30
  3891.7  351.46    3914  347.67    3928  339.38  4048.2  331.94  4062.2  336.05
    4079  331.98  4084.5  335.94  4101.3  329.78    4146  333.52  4168.4  332.59
  4347.8  317.39  4376.7  315.74    4392  316.29  4428.3  310.24    4652  302.19
  4763.8  301.82  4786.1  298.81  4808.5  302.39  4973.4  301.81  4987.4  300.77
  4992.7  297.61  4995.5  297.11  4998.7  297.61  5018.1  301.66  5054.4  301.86
  5470.9  299.51  5716.9  303.44  5904.1  314.91    6083  331.69  6127.8  338.62
#Mann= 5 ,-1 , 0
  3891.7     .05       0  4347.8     .16       0  4376.7     .12       0
  4992.7     .07       0  4998.7     .12       0
Bank Sta=4973.4,5054.4
XS Rating Curve= 0 ,0
Exp/Cntr=0.3,0.1

Type RM Length L Ch R = 1 ,253043  ,1814,1814,1814
BEGIN DESCRIPTION:
UPPER KEECHI CREEK 74.0
END DESCRIPTION:
XS GIS Cut Line= 3
      3640774.27     10580629.42       3639906.2     10579084.27
      3638613.74     10578338.28
#Sta/Elev= 30
  3376.2  360.58  3512.8   350.4  3642.9  343.99  3680.5  340.67  3686.2  336.95
  3696.5  337.79  3702.2  334.42  3723.9  333.37  3739.8  336.47  3745.5  333.33
  3804.8  331.49  3869.9  332.46  3988.5  327.03  4010.2   324.2  4078.6  322.43
  4202.4  316.88  4468.2  305.56  4685.4  301.19  4971.7  301.15  4987.6  297.92
  5006.3  297.76  5009.1  297.26  5012.3  297.76  5015.5  302.19  5250.5  299.03
  5448.6  301.49  5560.2  299.07  5711.4  301.36  6079.8  316.57  6640.8  347.46
#Mann= 6 ,-1 , 0
  3376.2     .05       0  4078.6     .16       0  4202.4     .05       0
  4468.2     .12       0  5006.3     .07       0  5012.3     .12       0
Bank Sta=4971.7,5015.5
XS Rating Curve= 0 ,0
Exp/Cntr=0.3,0.1

Type RM Length L Ch R = 1 ,251229  ,1262,1262,1262
BEGIN DESCRIPTION:
Mapping XS 1e77ec59
END DESCRIPTION:
XS GIS Cut Line= 3
      3640982.59     10580481.83      3640123.22     10577634.62
       3639438.3     10576984.38
#Sta/Elev= 30
    3235  353.01  3366.9  349.93  3509.2  340.17  3668.8  332.04  3849.4  318.76
  4021.1  312.08  4331.9  300.66  4343.9  301.91  4956.7  300.84  4981.1  299.76
  4991.9  295.26  4994.6  294.76  4997.9  295.26  5033.4  300.51  5060.8  300.67
  5367.6  299.07  5816.8  299.77  5879.4  302.41    6064  317.63  6109.3  323.95
    6215   332.7  6292.6  343.56  6434.2  350.86  6575.4  349.01  6681.8  344.37
  6801.9  345.32  6893.7  349.09    7007  346.77  7056.4  349.72  7153.5  349.54
#Mann= 5 ,-1 , 0
    3235     .05       0  3668.8     .16       0  4021.1     .12       0
  4991.9     .07       0  4997.9     .12       0
Bank Sta=4956.7,5060.8
XS Rating Curve= 0 ,0
Exp/Cntr=0.3,0.1

Type RM Length L Ch R = 1 ,249967  ,651,651,651
BEGIN DESCRIPTION:
Mapping XS c55e399f
END DESCRIPTION:
XS GIS Cut Line= 4
      3641164.89     10580247.43      3641243.01     10579683.23
      3640618.01     10577452.32      3639724.27     10576992.44
#Sta/Elev= 30
  3452.6  339.47  3477.6  340.65  3530.6  340.62  3621.4  335.56  3760.6  324.64
    3783  321.12  3936.2  309.57  4057.5  303.21  4295.4   300.7  4876.9  301.09
  4977.8   298.5  4998.5  294.82  5001.3  294.32  5004.5  294.82  5017.8   297.6
  5027.8  299.55  5032.7  299.71  5276.7  301.16    5957  298.28  6241.5  300.27
  6320.4  304.01  6526.1   322.6  6703.5  342.68  6798.3   348.1  6875.3  349.36
  6991.7  344.93  7080.4  344.82  7163.5  345.43  7246.6  349.33  7344.1   348.9
#Mann= 8 ,-1 , 0
  3452.6     .12       0  3477.6     .05       0  3760.6     .16       0
  3936.2     .12       0  4998.5     .07       0  5004.5     .12       0
  5017.8     .07       0  5027.8     .12       0
Bank Sta=4876.9,5032.7
XS Rating Curve= 0 ,0
Exp/Cntr=0.3,0.1

Type RM Length L Ch R = 1 ,249316  ,870,870,870
BEGIN DESCRIPTION:
Mapping XS b458eb0a
END DESCRIPTION:
XS GIS Cut Line= 4
      3641659.67     10580863.77       3641381.9     10578346.42
      3641008.63     10577261.35      3639949.57     10576237.01
#Sta/Elev= 30
  2949.1   353.9  3181.1  332.25  3343.8  321.47  3375.3  314.85  3390.1  316.58
  3425.6  311.87  3445.7     317  3606.7  316.45  3737.4  326.29  3760.3  324.22
  3858.2  323.02  4073.1  309.41  4172.2  305.99  4964.8  299.81  5002.6  295.14
  5005.4  294.64  5008.6  295.14  5035.3  300.26  5612.3  300.18  5840.2  298.93
  6869.8  300.73  7294.2   325.8  7591.1  316.61  7725.6  329.37    7768  337.75
  7824.4  343.63  7951.7  349.22  8045.4  346.61  8080.6  345.24  8102.6  345.27
#Mann= 13 ,-1 , 0
  2949.1     .16       0  3181.1     .12       0  3343.8     .05       0
  3390.1     .12       0  3760.3     .05       0  4073.1     .16       0
  4172.2     .12       0  5002.6     .07       0  5008.6     .12       0
  5612.3     .07       0  5840.2     .12       0  8045.4     .16       0
  8080.6     .05       0
Bank Sta=4964.8,5035.3
XS Rating Curve= 0 ,0
Exp/Cntr=0.3,0.1

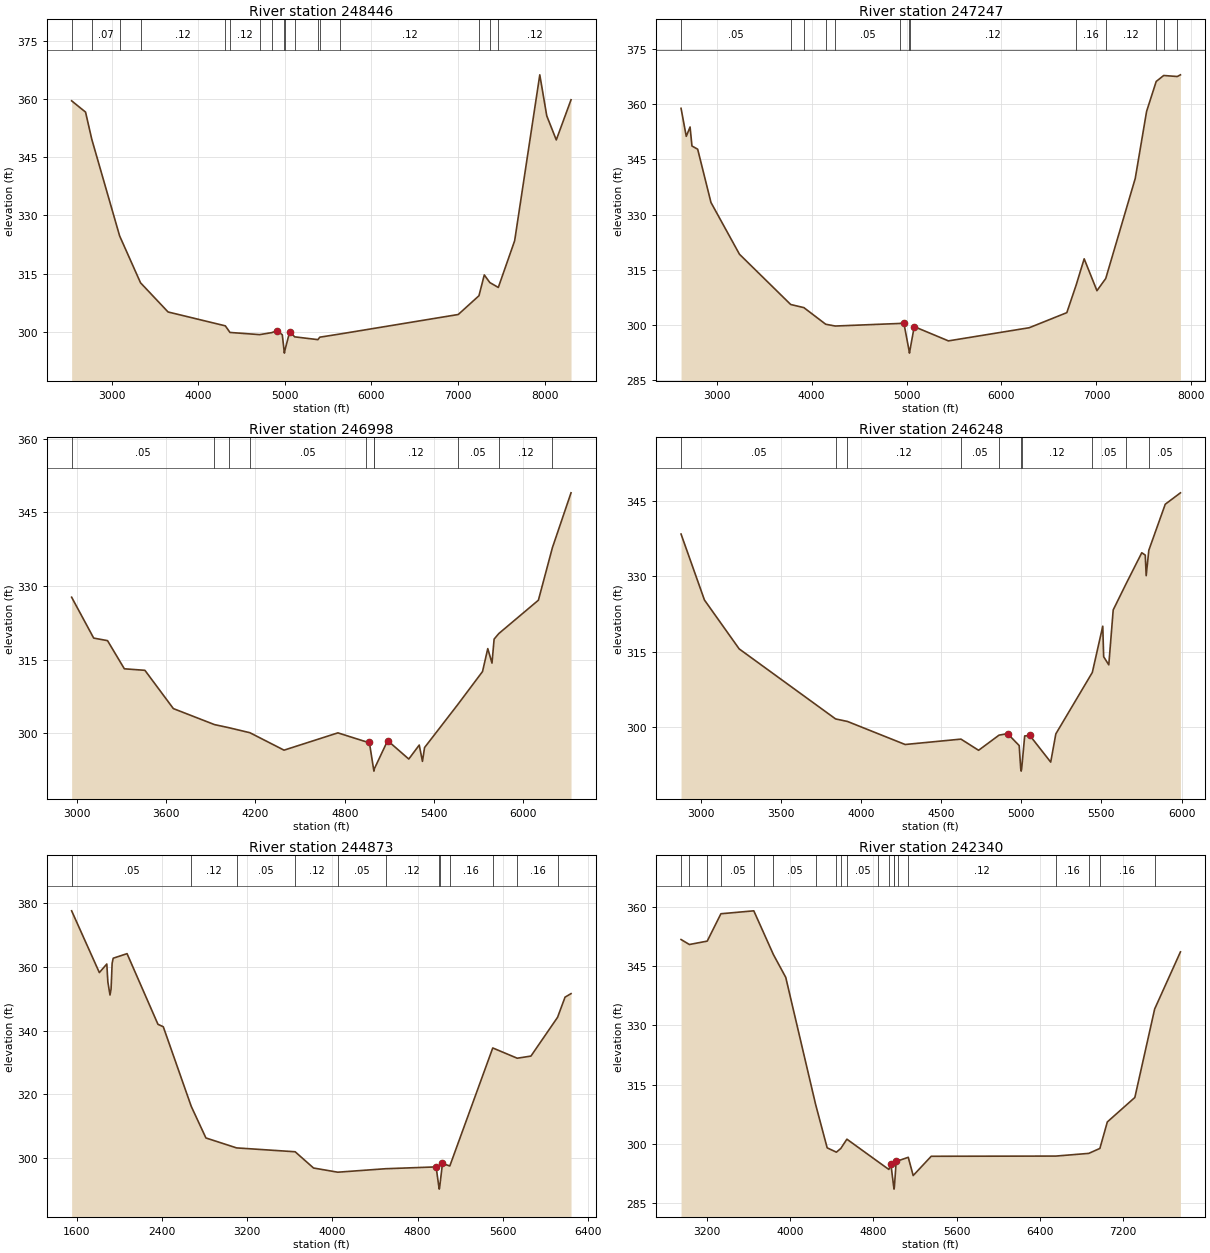
Type RM Length L Ch R = 1 ,248446  ,1199,1199,1199
BEGIN DESCRIPTION:
Mapping XS 7a85721f
END DESCRIPTION:
XS GIS Cut Line= 3
      3642449.62     10580586.05      3641763.84     10577599.89
      3641937.45     10574900.26
#Sta/Elev= 30
  2537.3  359.49    2698  356.59  2770.4  349.57  3091.6  324.74  3333.2  312.67
  3651.4  305.16  4312.7  301.59  4366.5  299.89  4709.2  299.33  4850.2  299.85
  4913.4  300.38  4971.1  299.28  4992.5  295.07  4995.3  294.57  4998.5  295.07
  5056.8  300.11  5113.7  298.76  5382.1  298.04  5404.1  298.67  5642.4  299.51
  7003.8  304.51  7242.9  309.34  7304.4  314.69  7368.3  312.73  7466.4  311.47
  7655.1  323.48  7945.6  366.18  8025.9  355.64  8136.1  349.43  8306.4  359.76
#Mann= 17 ,-1 , 0
  2537.3     .12       0  2770.4     .07       0  3091.6     .05       0
  3333.2     .12       0  4312.7     .05       0  4366.5     .12       0
  4709.2     .05       0  4850.2     .12       0  4992.5     .07       0
  4998.5     .12       0  5113.7     .07       0  5382.1     .12       0
  5404.1     .07       0  5642.4     .12       0  7242.9     .05       0
  7368.3     .16       0  7466.4     .12       0
Bank Sta=4913.4,5056.8
XS Rating Curve= 0 ,0
Exp/Cntr=0.3,0.1

Type RM Length L Ch R = 1 ,247247  ,249,249,249
BEGIN DESCRIPTION:
UPPER KEECHI CREEK 73.0
END DESCRIPTION:
XS GIS Cut Line= 3
      3642545.09      10580525.2      3642605.86     10577608.57
      3643004.88     10575301.18
#Sta/Elev= 30
  2625.6  358.81  2680.6  351.21  2720.6  353.75  2740.6  348.59  2800.7  347.72
  2940.7  333.27  3240.7  319.23  3780.3  305.59  3918.9  304.75  4148.7  300.24
  4249.7  299.75  4930.1  300.45  4971.1  300.69  5028.1   292.9  5030.9   292.4
  5034.1   292.9  5081.1  299.59  5441.2  295.72  6292.2  299.29    6688  303.38
  6786.5  310.89  6870.7  317.99  7005.2  309.34  7097.9  312.65  7408.5  339.79
    7528  357.98  7629.2   366.1  7707.9  367.72  7851.3  367.44  7884.5   367.9
#Mann= 13 ,-1 , 0
  2625.6     .05       0  3780.3     .16       0  3918.9     .05       0
  4148.7     .12       0  4249.7     .05       0  4930.1     .12       0
  5028.1     .07       0  5034.1     .12       0  6786.5     .16       0
  7097.9     .12       0  7629.2     .16       0  7707.9     .05       0
  7851.3     .16       0
Bank Sta=4971.1,5081.1
XS Rating Curve= 0 ,0
Exp/Cntr=0.3,0.1

Type RM Length L Ch R = 1 ,246998  ,750,750,750
BEGIN DESCRIPTION:
UPPER KEECHI CREEK 72.0
END DESCRIPTION:
XS GIS Cut Line= 3
      3642599.61     10580060.17      3642799.61     10578060.19
       3643699.6      10577060.2
#Sta/Elev= 30
  2965.3  327.73  3113.5  319.41  3206.5  318.89  3319.5  313.16  3457.7  312.85
  3648.7  305.06  3925.1   301.8  4023.3  301.16  4162.8  300.15  4392.4   296.6
  4754.2  300.12  4939.7  298.34  4965.2  298.28  4993.6  292.83  4996.3  292.33
  4999.6  292.83  5088.5  298.54  5230.5  294.79  5300.8  297.64  5322.4  294.32
  5336.6  297.13  5559.1  305.86    5726   312.6  5761.2  317.27  5789.6  314.32
  5803.8   319.2  5835.2  320.33  6101.3  327.12  6195.2  337.79  6320.6  348.98
#Mann= 10 ,-1 , 0
  2965.3     .05       0  3925.1     .07       0  4023.3     .12       0
  4162.8     .05       0  4939.7     .12       0  4993.6     .07       0
  4999.6     .12       0  5559.1     .05       0  5835.2     .12       0
  6195.2     .05       0
Bank Sta=4965.2,5088.5
XS Rating Curve= 0 ,0
Exp/Cntr=0.3,0.1

Type RM Length L Ch R = 1 ,246248  ,1375,1375,1375
BEGIN DESCRIPTION:
UPPER KEECHI CREEK 71.0
END DESCRIPTION:
XS GIS Cut Line= 3
      3642699.62     10580210.17      3643299.61     10578210.19
      3643799.61     10577310.19
#Sta/Elev= 30
  2875.7  338.41  3021.8   325.3  3238.5  315.59  3840.6  301.67  3914.6  301.17
  4274.7  296.59  4623.2  297.66  4733.2  295.44  4860.8  298.45  4914.1  298.75
  4986.6  296.38  4996.2   291.8    4999   291.3  5002.2   291.8  5020.9  298.29
    5053  298.39  5183.4  293.09  5215.4   298.7  5443.2  310.91  5508.3   320.1
    5514  314.03    5546  312.42  5573.5  323.33  5655.2  328.61  5751.9  334.69
  5773.7  334.23  5779.4  330.14  5795.9  335.19  5898.4  344.33  5993.3   346.6
#Mann= 10 ,-1 , 0
  2875.7     .05       0  3840.6     .07       0  3914.6     .12       0
  4623.2     .05       0  4860.8     .12       0  4996.2     .07       0
  5002.2     .12       0  5443.2     .05       0  5655.2     .16       0
  5795.9     .05       0
Bank Sta=4914.1,5053
XS Rating Curve= 0 ,0
Exp/Cntr=0.3,0.1

Type RM Length L Ch R = 1 ,244873  ,2533,2533,2533
BEGIN DESCRIPTION:
UPPER KEECHI CREEK 70.0
END DESCRIPTION:
XS GIS Cut Line= 3
       3643961.5     10581700.25       3644048.3     10578607.79
      3644004.93     10577013.96
#Sta/Elev= 30
  1551.5  377.54  1811.7  358.17  1881.7  360.86  1891.7   355.2  1911.7  351.14
  1921.7  353.01  1931.7   361.1  1941.7  362.67  2071.8  364.11  2361.9  341.95
  2411.9  341.18  2674.6  316.19  2812.1   306.3    3100  303.18  3649.7  301.97
  3822.5  296.87    4050  295.56  4499.6  296.65  4972.9  297.22  4999.9  290.75
  5002.7  290.25  5005.9  290.75  5032.9   298.3  5101.6  297.51  5504.8  334.53
  5734.6  331.31  5863.2  331.98  6113.4  344.15  6183.4  350.46  6239.6  351.57
#Mann= 12 ,-1 , 0
  1551.5     .05       0  2674.6     .12       0    3100     .05       0
  3649.7     .12       0    4050     .05       0  4499.6     .12       0
  4999.9     .07       0  5005.9     .12       0  5101.6     .16       0
  5504.8     .05       0  5734.6     .16       0  6113.4     .05       0
Bank Sta=4972.9,5032.9
XS Rating Curve= 0 ,0
Exp/Cntr=0.3,0.1

Type RM Length L Ch R = 1 ,242340  ,529,529,529
BEGIN DESCRIPTION:
UPPER KEECHI CREEK 69.0
END DESCRIPTION:
XS GIS Cut Line= 3
      3645806.11     10581266.19      3645263.58     10578586.09
       3644200.2      10576817.4
#Sta/Elev= 30
  2951.5  351.67  3031.8  350.41  3203.2  351.27  3334.4  358.18  3650.5  358.92
  3838.8  347.87  3957.5  342.11  4243.9  310.06  4355.4  299.04    4444  297.95
  4486.5  298.89  4544.9  301.23  4847.5  295.48  4948.3  293.58  4967.6  294.93
  4995.2  289.11  4997.9  288.61  5001.2  289.11  5018.6  295.61  5036.6  295.76
  5134.5  296.65  5181.8  292.04  5355.3  296.91  6552.3  296.96  6868.6  297.64
  6975.6  298.89  7047.3  305.59  7311.5  311.76    7502  334.12  7749.7  348.55
#Mann= 20 ,-1 , 0
  2951.5     .05       0  3031.8     .07       0  3203.2     .07       0
  3334.4     .05       0  3650.5     .07       0  3838.8     .05       0
  4243.9     .12       0    4444     .16       0  4486.5      .1       0
  4544.9     .05       0  4847.5     .07       0  4948.3     .12       0
  4995.2     .07       0  5001.2     .12       0  5036.6     .07       0
  5134.5     .12       0  6552.3     .16       0  6868.6     .12       0
  6975.6     .16       0    7502     .05       0
Bank Sta=4967.6,5018.6
XS Rating Curve= 0 ,0
Exp/Cntr=0.3,0.1

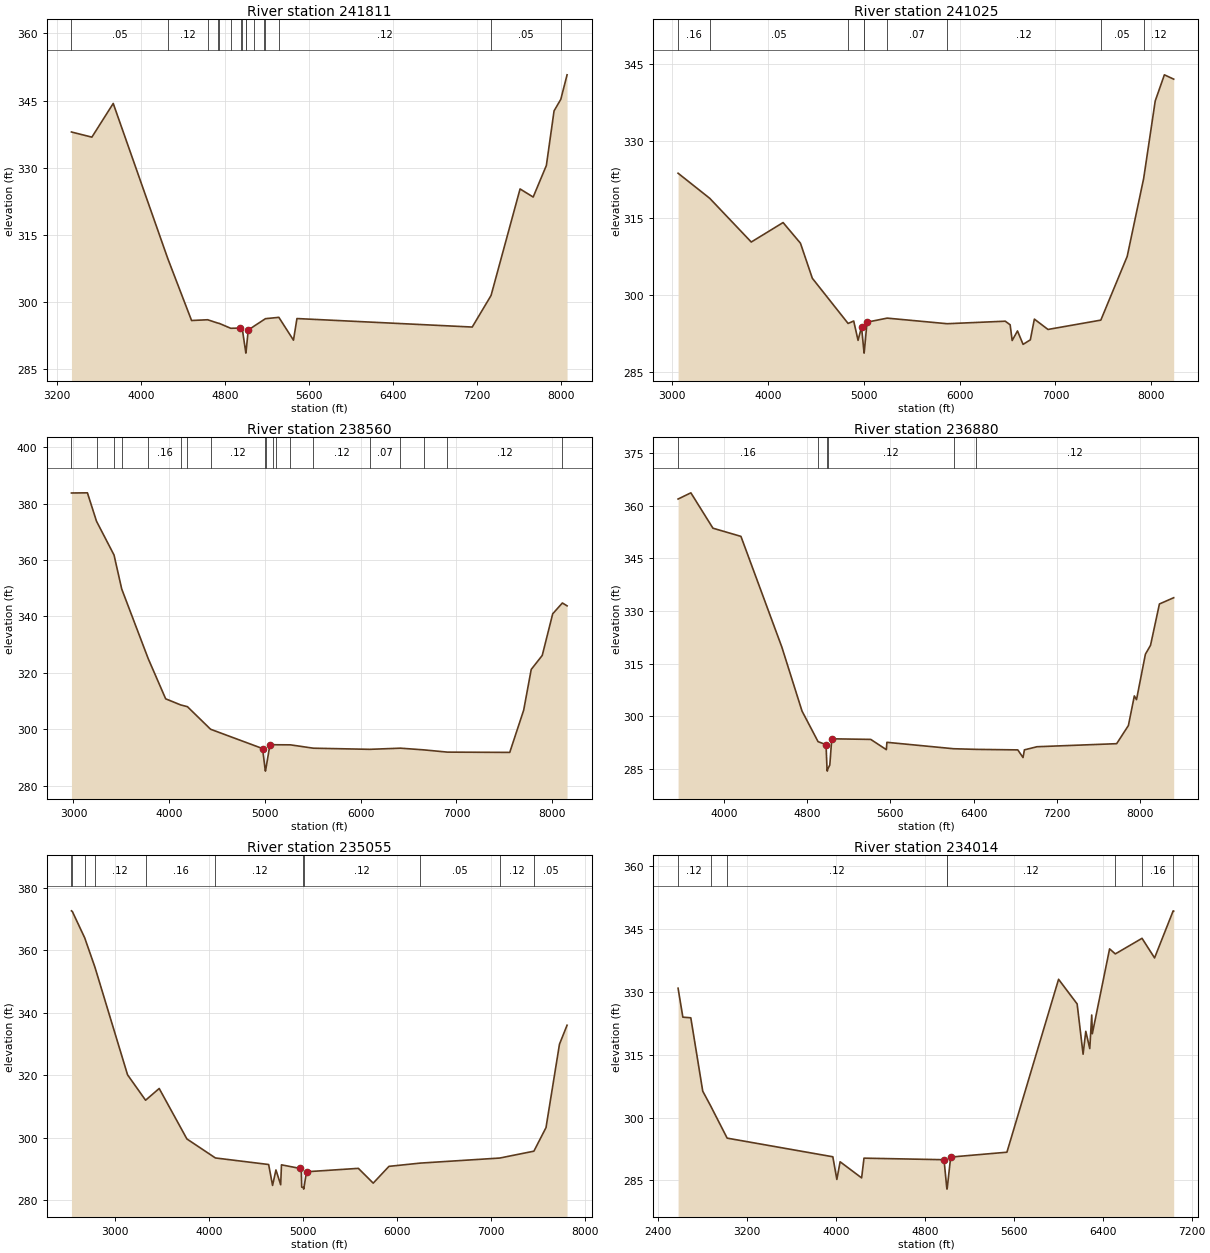
Type RM Length L Ch R = 1 ,241811  ,786,786,786
BEGIN DESCRIPTION:
UPPER KEECHI CREEK 68.0
END DESCRIPTION:
XS GIS Cut Line= 3
      3646500.56     10580506.66      3645675.91      10578716.3
      3644884.21     10576091.76
#Sta/Elev= 30
  3341.1  337.98  3535.4  336.83  3738.4  344.36  4256.3  309.74  4483.2  295.84
  4636.1  296.01  4734.8  295.25  4746.1   295.2    4856   294.1  4944.6  294.15
  4952.8  294.05    4966   293.9  4996.4  289.05  4999.2  288.55  5002.4  289.05
  5021.7  293.68    5076  294.56  5170.8  296.02  5185.9  296.25  5313.1  296.55
  5452.2  291.45  5485.2  296.28  7151.8  294.38  7330.9  301.44  7606.7  325.25
  7731.4  323.44  7856.8   330.5  7929.9   342.7    7994  345.29  8053.6  350.76
#Mann= 16 ,-1 , 0
  3341.1     .05       0  4256.3     .12       0  4636.1     .07       0
  4734.8     .05       0  4746.1     .07       0    4856     .05       0
  4952.8     .07       0    4966     .05       0  4996.4     .03       0
  5002.4     .05       0    5076     .07       0  5170.8     .12       0
  5185.9     .07       0  5313.1     .12       0  7330.9     .05       0
    7994     .08       0
Bank Sta=4944.6,5021.7
XS Rating Curve= 0 ,0
Exp/Cntr=0.3,0.1

Type RM Length L Ch R = 1 ,241025  ,2465,2465,2465
BEGIN DESCRIPTION:
UPPER KEECHI CREEK 67.0
END DESCRIPTION:
XS GIS Cut Line= 3
      3647520.52     10580495.81      3646370.35     10578727.15
      3645415.49     10575819.16
#Sta/Elev= 30
  3062.6  323.76    3393  318.86  3826.1  310.33  4158.2  314.13  4339.4   310.1
  4463.2  303.26  4836.3  294.44  4894.9  294.92  4940.3  291.14  4976.5  293.76
  5000.6  289.15  5003.3  288.65  5006.6  289.15  5033.8  294.69  5244.1  295.48
  5870.2  294.39  6476.2  294.88  6526.9  294.18    6548  291.11  6603.5  292.98
  6661.9  290.36  6737.4  291.24  6779.5  295.29  6921.7  293.27  7472.9  295.09
  7747.9  307.52    7920  322.76  8040.4  337.86  8135.9  342.96  8233.1  342.12
#Mann= 9 ,-1 , 0
  3062.6     .16       0    3393     .05       0  4836.3     .12       0
  5000.6     .07       0  5006.6     .12       0  5244.1     .07       0
  5870.2     .12       0  7472.9     .05       0    7920     .12       0
Bank Sta=4976.5,5033.8
XS Rating Curve= 0 ,0
Exp/Cntr=0.3,0.1

Type RM Length L Ch R = 1 ,238560  ,1680,1680,1680
BEGIN DESCRIPTION:
UPPER KEECHI CREEK 66.0
END DESCRIPTION:
XS GIS Cut Line= 3
      3648540.51      10580506.7      3647477.12      10577989.3
      3646164.39     10575927.99
#Sta/Elev= 30
  2978.7  383.76  3145.6  383.82  3240.4  373.75  3423.6  361.75  3503.6  349.73
  3780.7  324.99  3962.8  310.76    4119   308.6  4190.3  307.96  4432.1  299.96
  4975.2  293.11  5001.9  285.61  5004.7  285.11  5007.9  285.61  5051.8  294.48
  5078.9  294.53  5114.7  294.46    5266  294.43    5506  293.24  6096.1  292.84
  6414.6  293.25  6658.1  292.65  6906.1  291.85  7556.6  291.75  7702.2  306.75
  7780.9  321.18    7896  326.15  8005.2  340.91  8106.4  344.75  8155.3  343.73
#Mann= 19 ,-1 , 0
  2978.7     .16       0  3240.4     .12       0  3423.6     .16       0
  3503.6     .12       0  3780.7     .16       0    4119     .12       0
  4190.3     .16       0  4432.1     .12       0  5001.9     .07       0
  5007.9     .12       0  5078.9     .07       0  5114.7     .12       0
    5266     .07       0    5506     .12       0  6096.1     .07       0
  6414.6     .12       0  6658.1     .07       0  6906.1     .12       0
  8106.4     .16       0
Bank Sta=4975.2,5051.8
XS Rating Curve= 0 ,0
Exp/Cntr=0.3,0.1

Type RM Length L Ch R = 1 ,236880  ,1825,1825,1825
BEGIN DESCRIPTION:
UPPER KEECHI CREEK 65.0
END DESCRIPTION:
XS GIS Cut Line= 3
      3649093.88     10579844.78      3648356.03     10577728.89
      3646695.89     10575830.03
#Sta/Elev= 30
  3559.4   361.9  3682.4  363.67  3894.6  353.59  4163.6  351.26  4556.9   319.7
  4750.4   301.5  4904.8  292.77  4981.3   291.9    4991  284.87  4993.7  284.37
    4997  284.87  5017.7  286.12  5036.4  293.58    5411  293.41  5561.1  290.49
  5566.4  292.58  6207.6  290.75  6422.8  290.57  6824.2  290.42  6874.5  288.24
  6887.7  290.43  7008.3  291.32  7774.3  292.19  7887.2  297.36  7944.2   305.8
  7965.1  304.74  8050.5  317.68  8099.8  320.22  8185.3     332  8322.5  333.78
#Mann= 6 ,-1 , 0
  3559.4     .16       0  4904.8     .12       0    4991     .07       0
    4997     .12       0  6207.6     .07       0  6422.8     .12       0
Bank Sta=4981.3,5036.4
XS Rating Curve= 0 ,0
Exp/Cntr=0.3,0.1

Type RM Length L Ch R = 1 ,235055  ,1041,1041,1041
BEGIN DESCRIPTION:
UPPER KEECHI CREEK 64.0
END DESCRIPTION:
XS GIS Cut Line= 3
      3650849.62      10579360.2      3649449.61     10577360.19
      3647049.63      10575860.2
#Sta/Elev= 30
  2534.2  372.64  2544.1  372.41  2675.6  363.96  2784.5  354.55    3131  320.14
  3322.7     312  3467.6  315.76  3762.3   299.6  4065.2  293.52  4631.6  291.42
  4673.4  284.72  4709.2  289.68  4759.7  284.94    4768  291.32  4968.1  290.15
  4978.5  290.07  4983.2  284.19  5001.4  284.04  5004.2  283.54  5007.4  284.04
  5034.5   289.1  5585.8  290.19  5743.8  285.46  5911.3  290.83  6243.6  291.87
  7089.4  293.49  7452.8  295.69  7581.7  303.24  7724.9  329.94  7805.7  336.02
#Mann= 11 ,-1 , 0
  2534.2     .16       0  2544.1     .05       0  2675.6     .16       0
  2784.5     .12       0  3322.7     .16       0  4065.2     .12       0
  5001.4     .07       0  5007.4     .12       0  6243.6     .05       0
  7089.4     .12       0  7452.8     .05       0
Bank Sta=4968.1,5034.5
XS Rating Curve= 0 ,0
Exp/Cntr=0.3,0.1

Type RM Length L Ch R = 1 ,234014  ,918,918,918
BEGIN DESCRIPTION:
UPPER KEECHI CREEK 63.0
END DESCRIPTION:
XS GIS Cut Line= 4
       3650899.6     10578660.18      3649499.61     10576660.19
      3649799.61     10575760.19      3650201.58     10574770.81
#Sta/Elev= 30
  2580.1  330.87  2623.2  323.96  2694.7  323.81    2802   306.3  2873.2  302.78
  3021.6  295.09  3972.1  290.64  4008.3  285.23  4037.5  289.45    4231   285.6
  4252.4  290.31  4972.1  289.94  4996.2  283.42  4998.9  282.92  5002.2  283.42
  5031.9  290.57  5537.9  291.73  6002.5     333  6169.5  327.12  6223.1  315.12
  6247.2  320.59  6283.1  316.46  6300.7  324.48  6306.1     320  6461.4  340.26
    6513  339.06  6753.1  342.78    6866   338.1  7033.4  349.34    7038  349.27
#Mann= 8 ,-1 , 0
  2580.1     .12       0  2873.2     .16       0  3021.6     .12       0
  4996.2     .07       0  5002.2     .12       0    6513     .05       0
  6753.1     .16       0  7033.4     .05       0
Bank Sta=4972.1,5031.9
XS Rating Curve= 0 ,0
Exp/Cntr=0.3,0.1

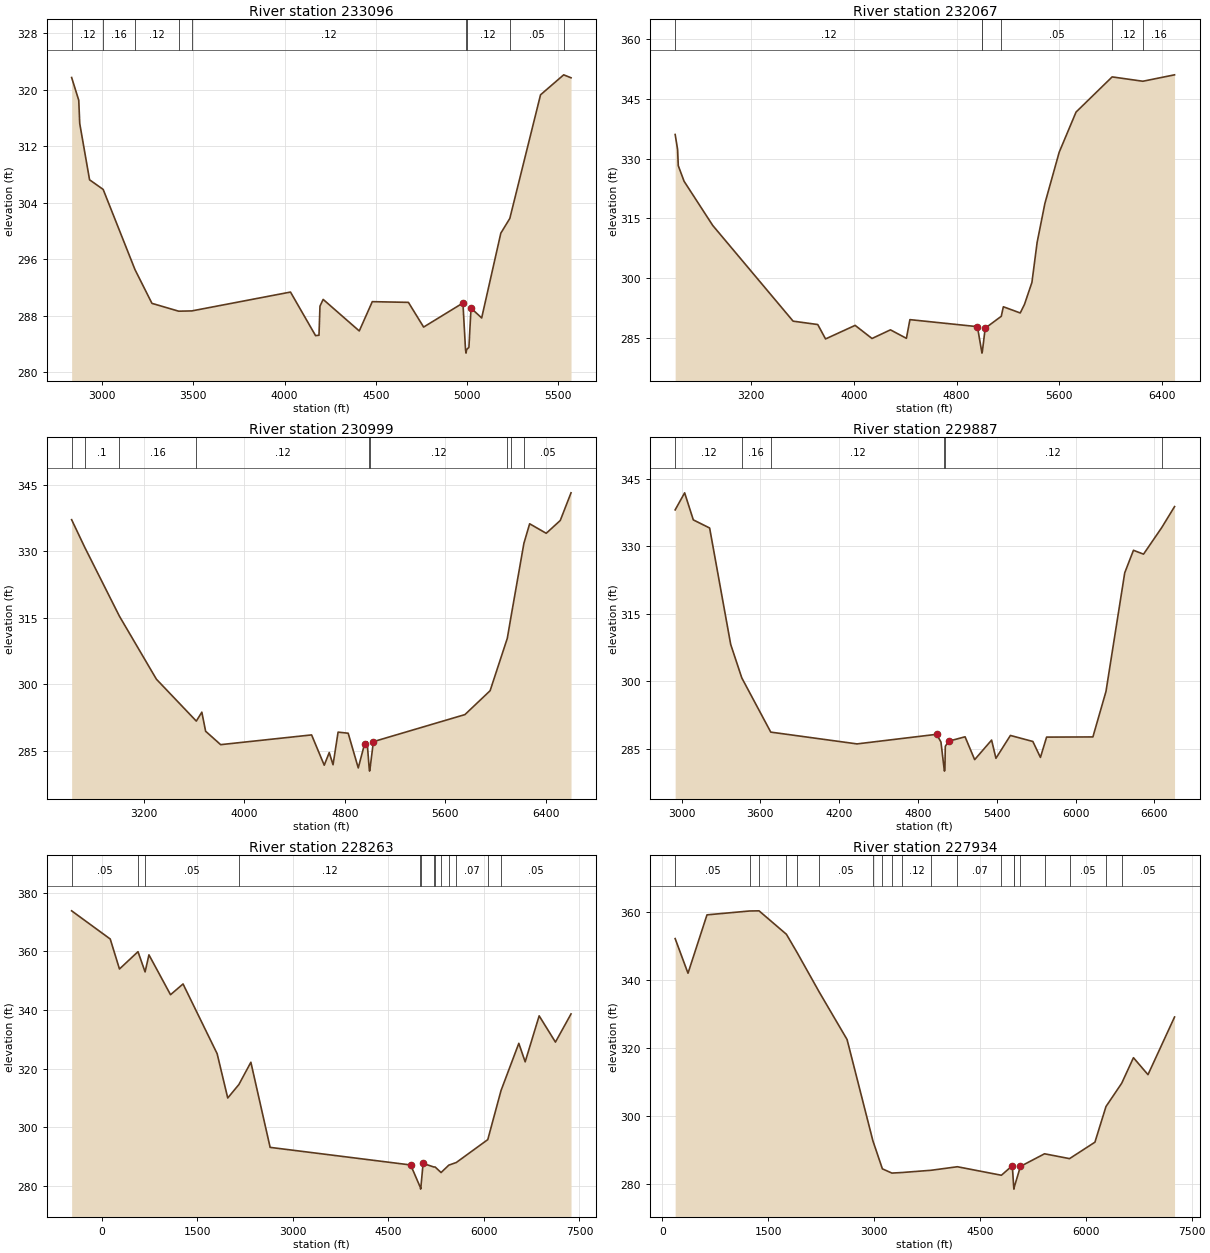
Type RM Length L Ch R = 1 ,233096  ,1029,1029,1029
BEGIN DESCRIPTION:
UPPER KEECHI CREEK 62.0
END DESCRIPTION:
XS GIS Cut Line= 3
       3651149.6     10578560.18      3650349.61     10576560.19
      3650049.63     10576060.23
#Sta/Elev= 30
  2832.6  321.73  2871.6  318.51    2877  315.21  2930.9  307.24  3005.4  305.88
    3180  294.51  3272.8  289.74  3419.2  288.63  3491.5  288.67  4032.1  291.34
  4169.5  285.17  4188.3  285.22  4193.7  289.34  4211.2   290.3  4409.1  285.83
  4480.4  289.98  4678.4  289.88  4761.8  286.38  4977.2  289.79  4991.4  283.19
  4994.2  282.69  4997.4  283.19    5010   283.5  5021.6  289.07  5079.9  287.67
  5184.9  299.68  5234.2  301.77  5402.6  319.28  5529.5  322.11  5569.7  321.69
#Mann= 9 ,-1 , 0
  2832.6     .12       0  3005.4     .16       0    3180     .12       0
  3419.2     .07       0  3491.5     .12       0  4991.4     .07       0
  4997.4     .12       0  5234.2     .05       0  5529.5     .12       0
Bank Sta=4977.2,5021.6
XS Rating Curve= 0 ,0
Exp/Cntr=0.3,0.1

Type RM Length L Ch R = 1 ,232067  ,1068,1068,1068
BEGIN DESCRIPTION:
Mapping XS 955f998a
END DESCRIPTION:
XS GIS Cut Line= 3
       3651578.4     10578978.88      3651057.56     10575593.47
      3650668.53     10575334.12
#Sta/Elev= 30
  2606.9  336.07  2625.8  332.34  2631.3  328.24  2676.4  324.34  2899.5  313.27
  3526.3  289.25  3718.5   288.4  3779.2  284.79  4009.9  288.19  4141.4   284.9
  4285.1  287.07  4409.5  284.94  4436.9  289.63    4963  287.87  4995.9  281.73
  4998.6  281.23  5001.9  281.73  5023.7  287.48    5149  290.47  5165.3  292.86
  5296.9   291.3  5330.2  293.48  5387.9  298.97  5428.4  308.98  5489.1  318.79
  5600.4  331.61  5731.9  341.69  6013.3  350.51  6252.8  349.42  6499.7  351.03
#Mann= 6 ,-1 , 0
  2606.9     .12       0  4995.9     .07       0  5001.9     .12       0
    5149     .05       0  6013.3     .12       0  6252.8     .16       0
Bank Sta=4963,5023.7
XS Rating Curve= 0 ,0
Exp/Cntr=0.3,0.1

Type RM Length L Ch R = 1 ,230999  ,1112,1112,1112
BEGIN DESCRIPTION:
Mapping XS b17011be
END DESCRIPTION:
XS GIS Cut Line= 3
      3652381.34     10579022.24      3652099.23     10576157.71
      3651904.48     10575075.79
#Sta/Elev= 30
  2623.3  337.18  2726.9  330.99  3003.4  315.41  3298.6  301.15  3616.4  291.69
  3660.3  293.71  3690.5   289.4  3810.2  286.37  4534.6  288.57  4635.3  281.73
  4675.2  284.59  4705.4  281.83  4745.6   289.2    4826  288.95  4906.3  281.11
  4956.6  286.55  4976.7  287.01  4993.8  280.89  4996.5  280.39  4999.8  280.89
  5026.9  287.05  5755.9  293.16  5956.4  298.55  6093.4  310.39  6125.5  315.69
  6225.8  331.86  6271.4  336.26  6403.5  334.11  6515.2     337    6601  343.25
#Mann= 9 ,-1 , 0
  2623.3     .12       0  2726.9      .1       0  3003.4     .16       0
  3616.4     .12       0  4993.8     .07       0  4999.8     .12       0
  6093.4     .16       0  6125.5     .12       0  6225.8     .05       0
Bank Sta=4956.6,5026.9
XS Rating Curve= 0 ,0
Exp/Cntr=0.3,0.1

Type RM Length L Ch R = 1 ,229887  ,1624,1624,1624
BEGIN DESCRIPTION:
Mapping XS 9a463745
END DESCRIPTION:
XS GIS Cut Line= 3
      3652945.59     10579022.25      3653054.09     10577351.28
      3652446.45     10575311.35
#Sta/Elev= 30
  2951.1  338.13  3023.3  341.92  3089.4  335.91  3213.7   334.1  3374.1  308.23
  3458.6  300.79  3679.2  288.74  4336.1  286.12    4942  288.25  4975.2  286.54
  4999.4  280.57  5002.1  280.07  5005.4  280.57  5008.3  285.58  5033.7  286.72
  5158.9   287.7  5231.9  282.62  5360.9  286.97    5394  282.92    5504     288
    5675  286.66  5732.8  283.12  5779.7  287.63  6132.3  287.67  6231.8  297.76
  6374.8  324.15  6441.2  329.15  6517.9  328.29  6656.6   334.2  6754.1  338.86
#Mann= 6 ,-1 , 0
  2951.1     .12       0  3458.6     .16       0  3679.2     .12       0
  4999.4     .07       0  5005.4     .12       0  6656.6     .05       0
Bank Sta=4942,5033.7
XS Rating Curve= 0 ,0
Exp/Cntr=0.3,0.1

Type RM Length L Ch R = 1 ,228263  ,329,329,329
BEGIN DESCRIPTION:
Mapping XS b9000805
END DESCRIPTION:
XS GIS Cut Line= 4
      3656613.12     10581083.93      3653726.83     10576613.44
      3653477.27       10576136.      3652186.06     10574638.64
#Sta/Elev= 30
  -468.8  373.85   136.8  364.24     282  354.01   572.7  359.92     684  353.01
   744.5  358.84  1083.1  345.24  1279.7  348.91  1814.8  325.12  1981.1  310.02
  2155.2  314.59    2344  322.21  2646.3  293.18  4851.4  287.18  5005.4  279.44
  5008.2  278.94  5011.4  279.44  5046.9   287.7  5215.7  286.49  5235.1   286.5
  5328.7   284.6  5451.1  287.13  5567.1  288.01  6061.7  295.82  6269.9  312.57
    6549  328.66  6648.8  322.35  6868.2  338.04  7123.8  329.08  7368.4  338.69
#Mann= 13 ,-1 , 0
  -468.8     .05       0   572.7     .16       0     684     .05       0
  2155.2     .12       0  5005.4     .07       0  5011.4     .12       0
  5215.7     .05       0  5235.1     .12       0  5328.7     .07       0
  5451.1     .05       0  5567.1     .07       0  6061.7     .12       0
  6269.9     .05       0
Bank Sta=4851.4,5046.9
XS Rating Curve= 0 ,0
Exp/Cntr=0.3,0.1

Type RM Length L Ch R = 1 ,227934  ,3644,3644,3644
BEGIN DESCRIPTION:
Mapping XS 9ae33397
END DESCRIPTION:
XS GIS Cut Line= 6
      3657068.85     10580237.57      3654562.34     10577351.28
      3653867.89     10576396.42      3653466.42     10575745.38
      3653119.19     10575354.75      3652513.09     10574856.89
#Sta/Elev= 30
   182.5  352.15   364.5  341.99   633.6  359.12  1236.2  360.25  1370.7   360.3
  1759.1  353.41  1908.5  348.12  2224.3  336.45  2618.3  322.53  2984.2   292.8
  3118.6  284.58  3253.1  283.34  3394.9   283.5  3812.3  284.17  4180.7   285.2
  4804.8   282.7  4959.2  285.51  4979.4  279.13  4982.1  278.63  4985.4  279.13
  5065.3  284.67  5074.3   285.3  5415.8     289    5770  287.58  6129.6   292.4
  6286.4  302.87  6508.9   309.7  6675.5   317.2  6881.5  312.22  7257.8  329.14
#Mann= 20 ,-1 , 0
   182.5     .05       0  1236.2     .08       0  1370.7     .08       0
  1759.1     .05       0  1908.5     .12       0  2224.3     .05       0
  2984.2     .07       0  3118.6     .12       0  3253.1     .07       0
  3394.9     .12       0  3812.3     .12       0  4180.7     .07       0
  4804.8     .07       0  4979.4     .07       0  4985.4     .12       0
  5065.3     .05       0  5415.8     .05       0    5770     .05       0
  6286.4     .05       0  6508.9     .05       0
Bank Sta=4959.2,5074.3
XS Rating Curve= 0 ,0
Exp/Cntr=0.3,0.1

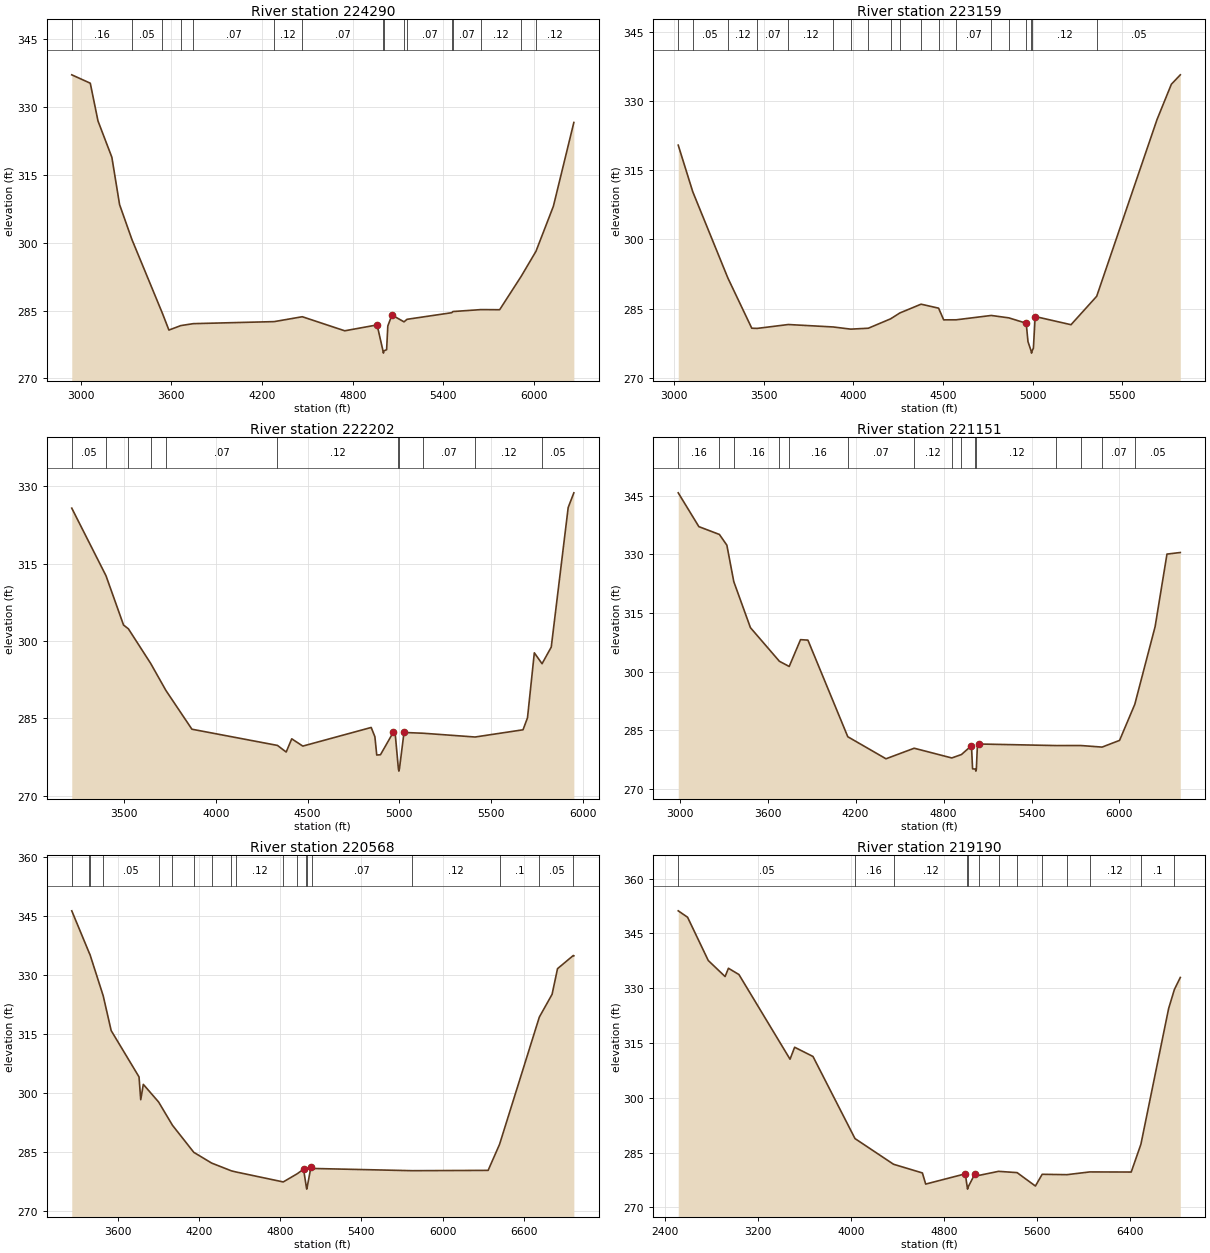
Type RM Length L Ch R = 1 ,224290  ,1131,1131,1131
BEGIN DESCRIPTION:
UPPER KEECHI CREEK 61.0
END DESCRIPTION:
XS GIS Cut Line= 3
      3656249.61     10577960.21      3655849.61     10575960.19
      3655049.58     10574960.15
#Sta/Elev= 30
  2942.2  337.15  3064.6   335.3  3115.6  326.95  3207.4  318.91  3258.4  308.44
  3339.8  300.74  3541.5  284.41  3584.7  280.69  3663.1  281.68  3745.9  282.11
  4281.2  282.56  4466.7  283.64  4747.3  280.53  4961.4  281.83  5000.4  276.09
  5003.2  275.59  5006.4  276.09  5024.3  276.34  5032.3  281.59  5059.5  284.02
  5139.4  282.51  5159.2  283.07  5454.7  284.53  5463.2  284.79    5649  285.22
  5771.8  285.19  5914.7   292.6    6012  298.11  6127.2  308.08  6262.5  326.61
#Mann= 16 ,-1 , 0
  2942.2     .16       0  3339.8     .05       0  3541.5     .07       0
  3663.1     .12       0  3745.9     .07       0  4281.2     .12       0
  4466.7     .07       0  5000.4     .07       0  5006.4     .07       0
  5139.4     .12       0  5159.2     .07       0  5454.7     .12       0
  5463.2     .07       0    5649     .12       0  5914.7     .07       0
    6012     .12       0
Bank Sta=4961.4,5059.5
XS Rating Curve= 0 ,0
Exp/Cntr=0.3,0.1

Type RM Length L Ch R = 1 ,223159  ,957,957,957
BEGIN DESCRIPTION:
UPPER KEECHI CREEK 60.0
END DESCRIPTION:
XS GIS Cut Line= 3
      3656399.61     10577660.18      3656494.35     10575646.19
      3656499.61     10574860.22
#Sta/Elev= 30
    3022  320.41    3103  310.34    3299  291.67  3432.4   280.8  3462.4  280.76
  3636.6   281.6  3887.1  281.07  3985.1   280.6  4083.1   280.8  4207.2  282.83
  4258.9   284.1  4377.2     286  4475.2  285.14  4503.6  282.61  4573.2  282.62
  4769.2  283.56  4867.2  283.04  4964.1  281.88  4965.3   281.4  4974.1  277.89
  4991.2  275.91  4993.9  275.41  4997.2  275.91  5004.2  276.47  5014.2  283.33
  5214.2  281.56  5357.5  287.71  5694.2  325.95  5774.2  333.59  5824.2  335.63
#Mann= 19 ,-1 , 0
    3022     .16       0    3103     .05       0    3299     .12       0
  3462.4     .07       0  3636.6     .12       0  3887.1     .07       0
  3985.1     .12       0  4083.1     .05       0  4207.2     .07       0
  4258.9     .05       0  4377.2     .07       0  4475.2     .05       0
  4573.2     .07       0  4769.2     .12       0  4867.2     .07       0
  4965.3     .12       0  4991.2     .07       0  4997.2     .12       0
  5357.5     .05       0
Bank Sta=4964.1,5014.2
XS Rating Curve= 0 ,0
Exp/Cntr=0.3,0.1

Type RM Length L Ch R = 1 ,222202  ,1051,1051,1051
BEGIN DESCRIPTION:
UPPER KEECHI CREEK 59.0
END DESCRIPTION:
XS GIS Cut Line= 3
      3657449.61     10577510.23      3657249.61     10575710.19
      3657449.61     10574810.17
#Sta/Elev= 30
  3216.4  325.74  3402.8  312.64  3498.2   303.1  3524.7  302.36  3645.9  295.66
  3728.9  290.42  3870.4  282.91  4336.2  279.77  4383.6  278.49  4413.8  281.05
  4474.1  279.64  4846.4  283.25  4866.5  281.45  4876.6  277.91  4896.7  277.96
  4967.2  282.35  4977.2  281.98  4994.3  275.29  4997.1  274.79  5000.3  275.29
    5025  282.28  5129.6  282.13  5411.9   281.4  5672.9   282.8  5697.2  285.12
  5734.4  297.71  5776.4   295.6  5826.5  298.82  5918.7  325.86  5949.5  328.71
#Mann= 11 ,-1 , 0
  3216.4     .05       0  3402.8     .16       0  3524.7     .12       0
  3645.9     .16       0  3728.9     .07       0  4336.2     .12       0
  4994.3     .07       0  5000.3     .12       0  5129.6     .07       0
  5411.9     .12       0  5776.4     .05       0
Bank Sta=4967.2,5025
XS Rating Curve= 0 ,0
Exp/Cntr=0.3,0.1

Type RM Length L Ch R = 1 ,221151  ,583,583,583
BEGIN DESCRIPTION:
UPPER KEECHI CREEK 58.0
END DESCRIPTION:
XS GIS Cut Line= 3
      3657749.61     10578010.16      3657949.61     10576010.19
       3657749.6     10574610.15
#Sta/Elev= 30
  2990.7  345.75  3131.4   337.1  3271.4   335.1  3322.3  332.36  3369.6  323.03
  3483.1  311.25  3680.6  302.65  3747.5  301.32  3824.8  308.18  3875.1  308.06
  4147.1  283.34  4407.7   277.7    4600   280.4  4856.4  277.91  4922.4  278.79
  4990.6  281.05  4998.1  275.14  5017.8  275.04  5020.6  274.54  5023.8  275.04
  5030.9  280.92  5041.1  281.48    5570  281.08  5736.9  281.09  5881.5  280.69
  6000.7  282.41  6104.4  291.63  6243.1  311.52  6323.9  330.07  6414.9  330.48
#Mann= 15 ,-1 , 0
  2990.7     .16       0  3271.4     .05       0  3369.6     .16       0
  3680.6     .12       0  3747.5     .16       0  4147.1     .07       0
    4600     .12       0  4856.4     .07       0  4922.4     .12       0
  5017.8     .07       0  5023.8     .12       0    5570     .07       0
  5736.9     .12       0  5881.5     .07       0  6104.4     .05       0
Bank Sta=4990.6,5041.1
XS Rating Curve= 0 ,0
Exp/Cntr=0.3,0.1

Type RM Length L Ch R = 1 ,220568  ,1378,1378,1378
BEGIN DESCRIPTION:
UPPER KEECHI CREEK 57.0
END DESCRIPTION:
XS GIS Cut Line= 3
       3657899.6     10577860.22      3658501.73     10576112.77
      3658699.61     10574260.19
#Sta/Elev= 30
  3259.3  346.25  3389.3  335.46  3393.8  335.14  3491.7  324.63  3550.6  315.78
  3756.5     304  3769.1   298.2  3788.2   302.1  3901.2  297.62  4003.6   291.7
  4161.4  284.81  4293.1  282.08    4440  280.09  4475.6   279.8  4822.6  277.28
  4924.9  279.34  4972.8  280.51  4993.4  275.95  4996.2  275.45  4999.4  275.95
  5027.7  281.13  5037.6  280.71  5775.5  280.14  6337.1  280.22  6421.5  286.84
  6715.5  319.21  6809.8  325.01    6850  331.53  6966.8  334.89  6970.7  334.81
#Mann= 19 ,-1 , 0
  3259.3     .16       0  3389.3     .05       0  3393.8     .16       0
  3491.7     .05       0  3901.2     .07       0  4003.6     .12       0
  4161.4     .05       0  4293.1     .12       0    4440     .07       0
  4475.6     .12       0  4822.6     .07       0  4924.9     .12       0
  4993.4     .07       0  4999.4     .12       0  5037.6     .07       0
  5775.5     .12       0  6421.5      .1       0  6715.5     .05       0
  6966.8     .12       0
Bank Sta=4972.8,5027.7
XS Rating Curve= 0 ,0
Exp/Cntr=0.3,0.1

Type RM Length L Ch R = 1 ,219190  ,1742,1742,1742
BEGIN DESCRIPTION:
UPPER KEECHI CREEK 56.0
END DESCRIPTION:
XS GIS Cut Line= 3
      3658035.16     10578532.44      3659055.11     10576438.29
      3659249.61     10574460.16
#Sta/Elev= 30
  2512.5   351.2  2592.9  349.44  2770.8  337.59  2915.4   333.2  2944.2  335.47
  3034.4  333.75  3473.8  310.56  3513.3  313.84  3671.1  311.31  4032.4  288.82
  4363.8  281.79    4612  279.41  4640.1  276.36  4980.6  279.17  4997.7  275.48
  5000.4  274.98  5003.7  275.48    5061  278.99    5099  278.75  5266.7  279.85
  5426.2   279.5  5583.5  275.83  5641.8  279.04  5854.6  278.94    6051  279.69
  6407.4  279.66  6490.6  287.26    6729  324.43  6778.6  329.66  6829.5  332.95
#Mann= 13 ,-1 , 0
  2512.5     .05       0  4032.4     .16       0  4363.8     .12       0
  4997.7     .07       0  5003.7     .12       0    5099     .07       0
  5266.7     .12       0  5426.2     .07       0  5641.8     .12       0
  5854.6     .05       0    6051     .12       0  6490.6      .1       0
  6778.6     .05       0
Bank Sta=4980.6,5061
XS Rating Curve= 0 ,0
Exp/Cntr=0.3,0.1