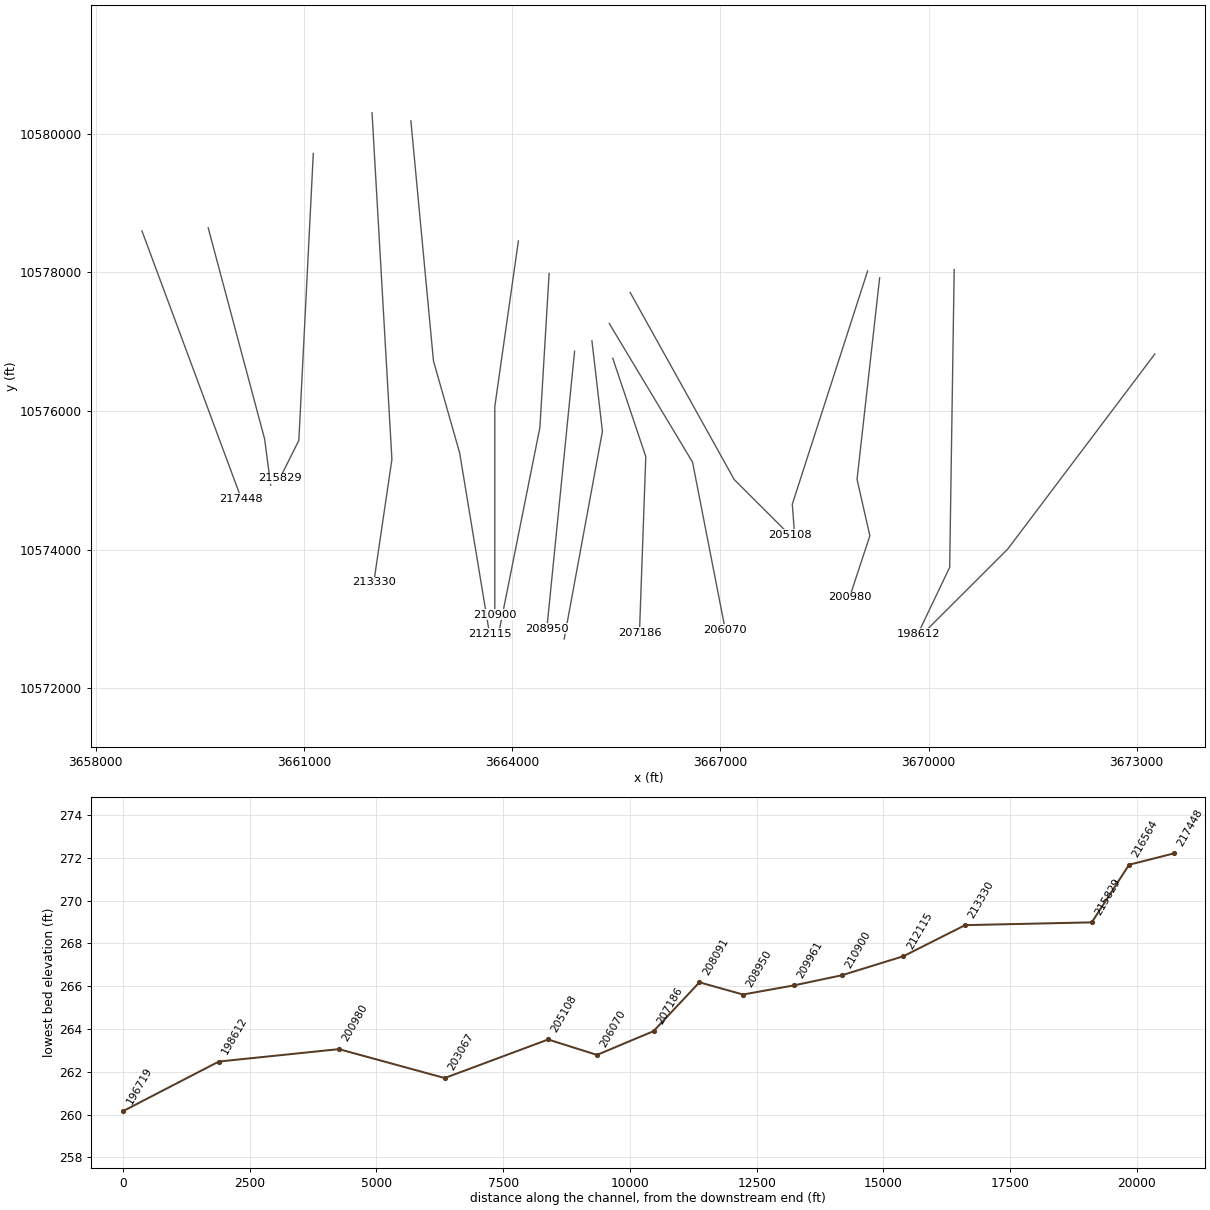
HEC-RAS study UPPER KEECHI CREEK.prj: UPPER KEECHI CREEK Base Level Engineering

--- UPPER KEECHI CREEK.g01 (geometry) --- (continued)

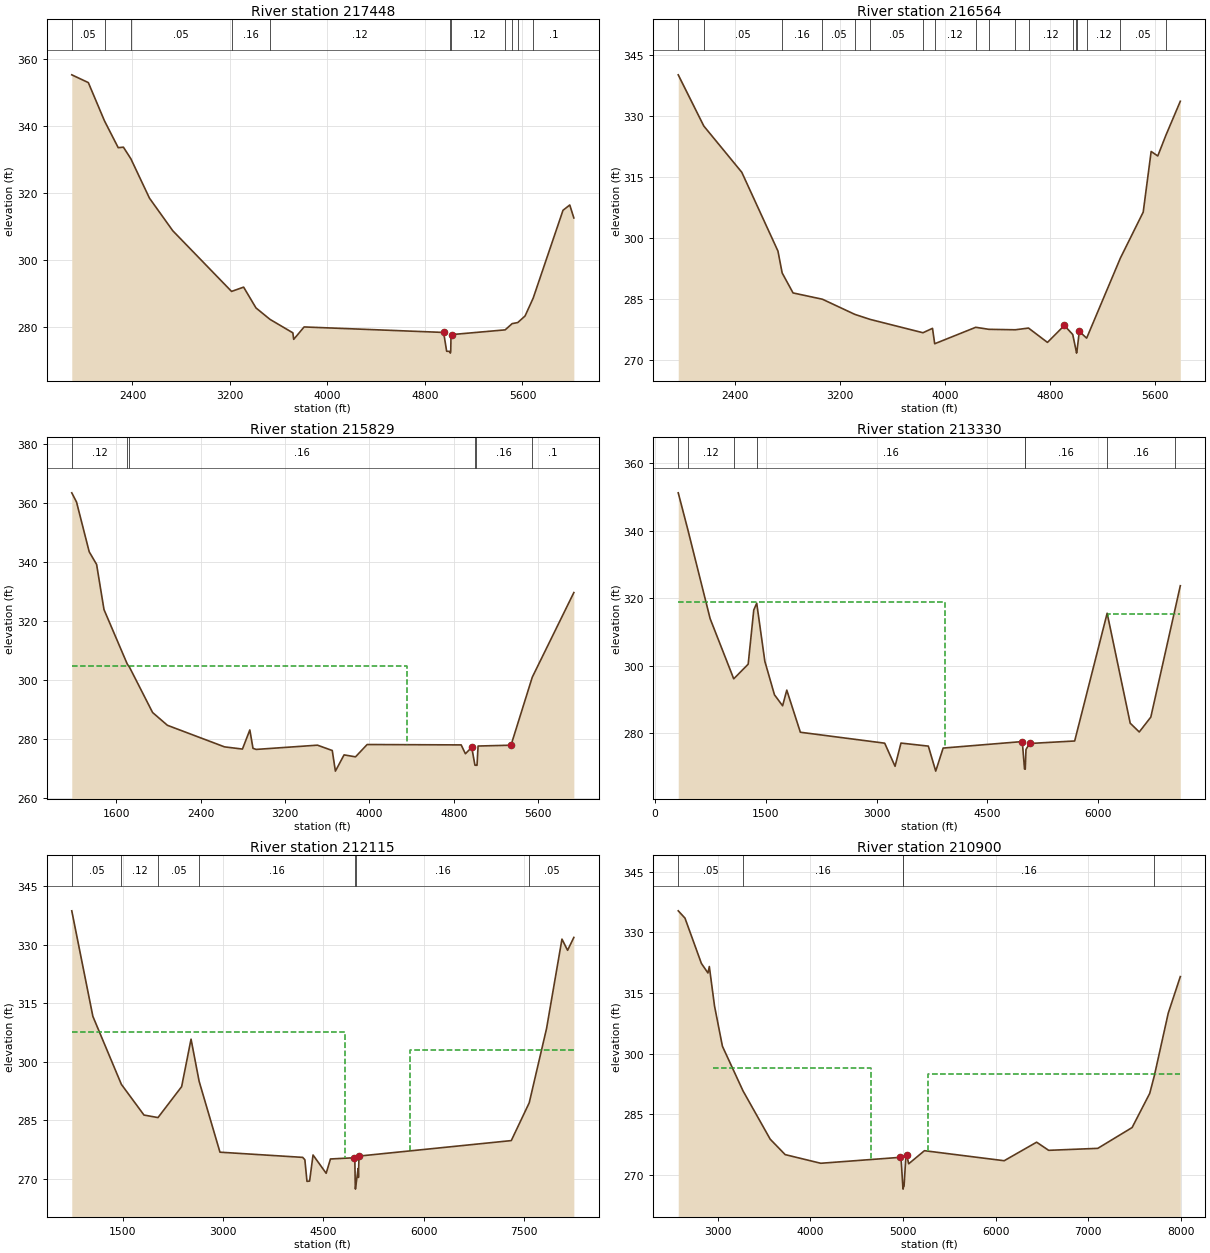
Type RM Length L Ch R = 1 ,217448  ,884,884,884
BEGIN DESCRIPTION:
UPPER KEECHI CREEK 55.0
END DESCRIPTION:
XS GIS Cut Line= 2
      3658664.49     10578597.57       3660096.7     10574734.94
#Sta/Elev= 30
  1902.1  355.32    2038     353  2170.9  341.54  2283.3  333.56  2325.9  333.71
  2387.1  330.24  2539.9  318.47  2731.2  308.74  3213.2  290.63  3312.2  291.91
  3413.8  285.69  3528.7  282.28  3716.2  278.26  3723.1  276.31  3808.4  280.02
  4953.2  278.38  4978.2  272.76  5005.6   272.7  5008.3   272.2  5011.6   272.7
  5013.9  277.49  5024.2  277.75  5458.3  279.15  5515.5  281.01  5561.4  281.33
  5621.5   283.3    5688  288.62  5932.8  314.86  5988.2  316.45  6021.7  312.58
#Mann= 11 ,-1 , 0
  1902.1     .05       0  2170.9     .16       0  2387.1     .05       0
  3213.2     .16       0  3528.7     .12       0  5005.6     .07       0
  5011.6     .12       0  5458.3     .07       0  5515.5     .12       0
  5561.4     .07       0    5688      .1       0
Bank Sta=4953.2,5024.2
XS Rating Curve= 0 ,0
Exp/Cntr=0.3,0.1

Type RM Length L Ch R = 1 ,216564  ,735,735,735
BEGIN DESCRIPTION:
UPPER KEECHI CREEK 54.0
END DESCRIPTION:
XS GIS Cut Line= 3
      3659619.36     10578640.95      3660433.15     10575591.94
      3660519.95     10574930.06
#Sta/Elev= 30
  1966.9  340.19  2161.8  327.58  2450.8   316.2  2726.2   296.8  2758.3  291.41
  2841.3  286.49  3064.9  284.94  3311.7  281.21  3428.6  279.97  3830.5  276.69
  3903.2  277.77  3919.9  273.98  4232.4  278.03  4332.9  277.53  4533.8  277.42
  4634.3  277.84  4778.5  274.31  4907.1  278.48  4971.1  276.25  4997.3  272.17
    5000  271.67  5003.3  272.17    5021  277.01    5077  275.36  5333.3  295.03
  5507.7  306.39  5568.2  321.32  5618.6  320.21  5680.3   325.3  5790.2  333.68
#Mann= 18 ,-1 , 0
  1966.9     .16       0  2161.8     .05       0  2758.3     .16       0
  3064.9     .05       0  3311.7     .16       0  3428.6     .05       0
  3830.5     .07       0  3919.9     .12       0  4232.4     .16       0
  4332.9     .05       0  4533.8     .16       0  4634.3     .12       0
  4971.1     .07       0  4997.3     .07       0  5003.3     .07       0
    5077     .12       0  5333.3     .05       0  5680.3      .1       0
Bank Sta=4907.1,5021
XS Rating Curve= 0 ,0
Exp/Cntr=0.3,0.1

Type RM Length L Ch R = 1 ,215829  ,2499,2499,2499
BEGIN DESCRIPTION:
UPPER KEECHI CREEK 53.0
END DESCRIPTION:
XS GIS Cut Line= 3
       3661134.1     10579715.23      3660925.77     10575574.58
      3660652.34     10575027.72
#Sta/Elev= 30
  1179.5  363.34  1224.6  360.22  1344.8  343.35  1414.8  339.06  1484.9  323.75
  1705.4  305.28  1725.2  304.31  1945.5  288.85  2085.7  284.52  2626.4  277.21
  2796.6  276.46  2866.7  282.94  2896.7  276.71  2926.8  276.34  3507.5  277.78
  3647.7  275.97  3677.5  268.98  3759.6  274.49  3867.9  273.82  3978.1     278
  4869.2  277.87  4909.3  274.87  4969.3  277.06  4999.4  271.01  5009.4  270.96
  5019.4  270.97  5029.4  277.49  5341.5  277.77  5542.7  300.81  5936.8  329.52
#Mann= 6 ,-1 , 0
  1179.5     .12       0  1705.4     .05       0  1725.2     .16       0
  4999.4     .07       0  5009.4     .16       0  5542.7      .1       0
#XS Ineff= 2 , 0
         4352.27  304.61
Permanent Ineff=
       F       F
Bank Sta=4969.3,5341.5
XS Rating Curve= 0 ,0
Exp/Cntr=0.3,0.1

Type RM Length L Ch R = 1 ,213330  ,1215,1215,1215
BEGIN DESCRIPTION:
Mapping XS c1f39d3a
END DESCRIPTION:
XS GIS Cut Line= 3
      3661980.46     10580301.12      3662266.92     10575301.14
      3662006.49     10573530.26
#Sta/Elev= 30
   312.7  351.31   442.4  340.43   744.3  314.05  1064.1   296.2  1259.8  300.54
  1335.3  316.59  1375.4   318.6  1485.5  301.38  1615.8  291.46  1725.9  288.21
  1782.5  292.85  1966.3  280.37  3108.2  277.13  3248.4  270.28  3328.6  277.16
  3699.2  276.26  3799.1  268.85  3899.5  275.68  4971.3  277.61  5001.3   269.5
  5011.3   269.4  5021.3  275.26  5071.4  277.04  5680.5  277.78  6120.3  315.63
  6432.5  283.05    6555  280.45  6711.5  284.86  7045.1  317.35  7110.8  323.78
#Mann= 8 ,-1 , 0
   312.7     .16       0   442.4     .12       0  1064.1     .16       0
  1375.4     .16       0  5001.3     .07       0  5011.3     .16       0
  6120.3     .16       0  7045.1      .1       0
#XS Ineff= 2 ,-1
     250 3927.27  318.82 6131.82 7613.64  315.32
Permanent Ineff=
       F       F
Bank Sta=4971.3,5071.4
XS Rating Curve= 0 ,0
Exp/Cntr=0.3,0.1

Type RM Length L Ch R = 1 ,212115  ,1215,1215,1215
BEGIN DESCRIPTION:
Mapping XS 7c6b9c70
END DESCRIPTION:
XS GIS Cut Line= 4
      3662540.36     10580183.91      3662865.87     10576720.41
      3663243.48     10575392.29      3663673.17     10572788.12
#Sta/Elev= 30
   740.6  338.74  1055.7  311.69  1481.4  294.26  1819.1  286.39  2028.4  285.74
  2381.5  293.67  2522.1  305.84  2642.7  295.05    2954  276.87  4189.5  275.54
  4222.1  274.93  4253.6  269.39  4292.7  269.46  4344.3  276.15  4540.3  271.46
  4604.3  275.13  4957.7  275.44  4968.1  275.42    4975   267.9  4977.7   267.4
    4981   267.9    5017  272.67  5022.2  270.39  5030.5  275.87    7305  279.84
  7573.1  289.53    7832  308.58  8062.1  331.49  8146.2  328.62  8239.5  331.92
#Mann= 7 ,-1 , 0
   740.6     .05       0  1481.4     .12       0  2028.4     .05       0
  2642.7     .16       0    4975     .07       0    4981     .16       0
  7573.1     .05       0
#XS Ineff= 2 ,-1
  710.23 4818.18  307.76 5789.77 8511.36  303.15
Permanent Ineff=
       F       F
Bank Sta=4957.7,5030.5
XS Rating Curve= 0 ,0
Exp/Cntr=0.3,0.1

Type RM Length L Ch R = 1 ,210900  ,939,939,939
BEGIN DESCRIPTION:
UPPER KEECHI CREEK 52.0
END DESCRIPTION:
XS GIS Cut Line= 3
      3664089.83     10578452.16      3663749.61     10576060.19
      3663749.61     10573060.24
#Sta/Elev= 30
  2575.5   335.3  2648.2   333.5  2825.3   322.3  2896.1  319.94  2910.8  321.53
    2967  311.77  3052.2  301.82  3274.4  290.79  3567.4  278.86    3729  275.04
  4112.8   272.9  4971.3  274.37  4981.4  273.29  4998.5  267.01  5001.3  266.51
  5004.5  267.01  5011.5  267.23  5031.5  274.77  5041.5  274.84  5061.5  272.77
  5231.5  276.01  6091.5  273.53  6441.5  278.11  6571.5   276.1  7101.5  276.59
  7471.5  281.73  7661.5  290.17  7711.5  294.55  7861.5  310.02  7991.5  319.04
#Mann= 5 ,-1 , 0
  2575.5     .05       0  3274.4     .16       0  4998.5     .07       0
  5004.5     .16       0  7711.5     .05       0
#XS Ineff= 2 ,-1
 2947.73 4659.09  296.55 5265.91  7991.5  295.04
Permanent Ineff=
       F       F
Bank Sta=4971.3,5041.5
XS Rating Curve= 0 ,0
Exp/Cntr=0.3,0.1

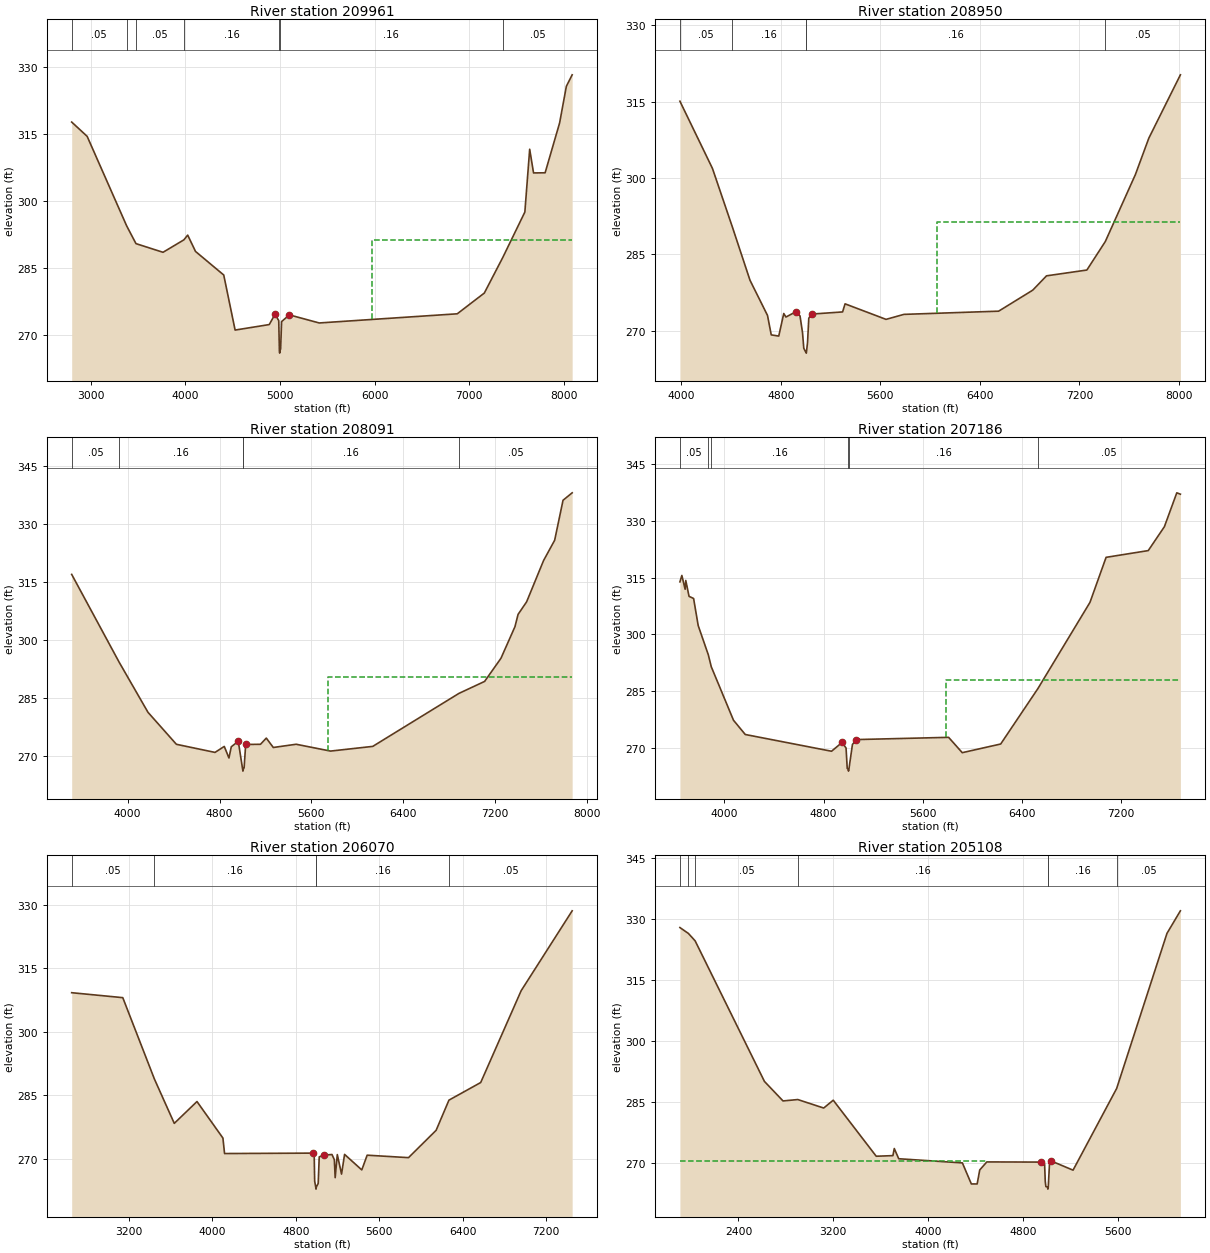
Type RM Length L Ch R = 1 ,209961  ,1011,1011,1011
BEGIN DESCRIPTION:
UPPER KEECHI CREEK 51.0
END DESCRIPTION:
XS GIS Cut Line= 3
      3664532.54     10577983.39      3664399.61     10575760.19
      3663799.61     10572760.17
#Sta/Elev= 30
    2799  317.74  2962.5  314.54  3379.6  294.52  3478.1  290.54  3763.9   288.6
  3984.3  291.39  4024.4  292.45  4107.1  288.79  4405.1  283.52  4525.3   271.2
  4885.9  272.43  4946.7  274.73  4986.1  273.32  4993.1  266.54  4995.9  266.04
  4999.1  266.54  5006.1  266.99  5016.2  273.09  5097.6   274.6  5413.7  272.79
    6872  274.84  7157.6  279.48  7351.3  287.38  7585.9   297.6  7636.9  311.66
  7677.7  306.36    7800  306.39    7953  317.54  8024.4  325.75  8085.6  328.31
#Mann= 7 ,-1 , 0
    2799     .05       0  3379.6     .08       0  3478.1     .05       0
  3984.3     .16       0  4993.1     .07       0  4999.1     .16       0
  7351.3     .05       0
#XS Ineff= 2 , 0
                          5973.3          291.45
Permanent Ineff=
       F       F
Bank Sta=4946.7,5097.6
XS Rating Curve= 0 ,0
Exp/Cntr=0.3,0.1

Type RM Length L Ch R = 1 ,208950  ,859,859,859
BEGIN DESCRIPTION:
UPPER KEECHI CREEK 50.0
END DESCRIPTION:
XS GIS Cut Line= 3
      3664899.61     10576860.18      3664799.61     10575860.19
      3664499.61     10572860.23
#Sta/Elev= 30
  3990.6  315.09  4251.9  301.89  4412.7  290.33  4553.4  279.93  4694.1  273.02
  4724.2  269.19  4784.5  268.96  4824.7  273.39  4842.3   272.7  4925.2  273.77
  4955.4   272.9  4975.5  269.62  4985.5  266.57  5005.4  265.61  5005.9  265.61
  5015.7  267.69  5025.7  272.46  5048.3  273.28  5297.1   273.7  5317.2  275.29
  5646.3  272.24  5789.5  273.22  6550.8  273.85  6824.7  277.98  6935.2  280.79
  7259.3  281.93  7407.5  287.53  7648.7  300.66  7756.8  307.82  8010.5  320.27
#Mann= 5 ,-1 , 0
  3990.6     .05       0  4412.7     .16       0  5005.4     .07       0
  5005.9     .16       0  7407.5     .05       0
#XS Ineff= 2 , 0
                         6054.55          291.45
Permanent Ineff=
       F       F
Bank Sta=4925.2,5048.3
XS Rating Curve= 0 ,0
Exp/Cntr=0.3,0.1

Type RM Length L Ch R = 1 ,208091  ,905,905,905
BEGIN DESCRIPTION:
UPPER KEECHI CREEK 49.0
END DESCRIPTION:
XS GIS Cut Line= 3
      3665149.61     10577010.21      3665300.77     10575704.79
      3664749.62     10572710.23
#Sta/Elev= 30
  3512.3  316.93  3925.1  294.31  4176.7  281.36  4424.3   273.1  4760.6  271.01
  4841.3  272.55    4882  269.57  4902.3  272.46  4963.3  273.88    5001  266.68
  5003.7  266.18    5007  266.68  5014.1  267.05  5027.8  273.06  5156.5   273.1
  5207.3   274.7  5268.3  272.28  5467.4  273.11  5766.6  271.35  6134.4  272.56
  6885.1  286.23  7108.8  289.32  7251.1  295.29  7373.1  303.44  7400.2  306.61
  7474.8  309.86  7622.5  320.52  7718.8  325.73  7791.8  336.05  7871.3  337.97
#Mann= 5 ,-1 , 0
  3512.3     .05       0  3925.1     .16       0    5001     .07       0
    5007     .16       0  6885.1     .05       0
#XS Ineff= 2 , 0
                         5747.16          290.34
Permanent Ineff=
       F       F
Bank Sta=4963.3,5027.8
XS Rating Curve= 0 ,0
Exp/Cntr=0.3,0.1

Type RM Length L Ch R = 1 ,207186  ,1116,1116,1116
BEGIN DESCRIPTION:
UPPER KEECHI CREEK 48.0
END DESCRIPTION:
XS GIS Cut Line= 3
      3665449.62     10576760.16      3665925.77      10575340.2
      3665834.62     10572801.11
#Sta/Elev= 30
  3641.2  313.86  3656.9  315.56  3683.2  311.91  3688.5  314.24  3714.8  310.04
  3751.6  309.48  3788.8  302.32  3870.5  294.59  3894.3  291.45  4073.6  277.33
  4168.5  273.57  4864.7  269.15  4950.4  271.49  4981.9  269.98  4991.2  264.62
  4998.8   264.4  5001.5   263.9  5004.8   264.4  5033.4  270.94  5065.1  272.23
  5809.3  272.82  5919.4  268.77  6229.6  271.06  6529.8  285.69    6950  308.45
  7080.1  320.34  7420.3  322.12  7550.4  328.42  7650.5  337.37  7679.6  337.01
#Mann= 6 ,-1 , 0
  3641.2     .05       0  3870.5     .16       0  3894.3     .16       0
  4998.8     .07       0  5004.8     .16       0  6529.8     .05       0
#XS Ineff= 2 , 0
                         5789.77          287.93
Permanent Ineff=
       F       F
Bank Sta=4950.4,5065.1
XS Rating Curve= 0 ,0
Exp/Cntr=0.3,0.1

Type RM Length L Ch R = 1 ,206070  ,962,962,962
BEGIN DESCRIPTION:
UPPER KEECHI CREEK 47.0
END DESCRIPTION:
XS GIS Cut Line= 3
      3665399.62     10577260.16      3666599.61     10575260.19
       3667071.6     10572840.24
#Sta/Elev= 30
  2651.5  309.21  3141.3  308.04  3444.5  288.81    3635  278.33  3852.6  283.49
  4101.4  274.86    4117   271.2  4960.5   271.3  4976.1  271.15  4980.9  264.67
    4991  263.29  4993.8  262.79    4997  263.29  5014.7  264.14  5024.6  270.41
  5066.3  270.83  5146.9  270.97  5169.5  269.74  5177.4   265.5  5197.8  270.95
  5238.6  266.34  5267.6     271  5432.6  267.33  5484.1  270.81  5880.4  270.23
  6145.3  276.69  6268.2  283.82  6572.6  287.98  6960.4  309.68  7449.4  328.56
#Mann= 5 ,-1 , 0
  2651.5     .05       0  3444.5     .16       0    4991     .07       0
    4997     .16       0  6268.2     .05       0
Bank Sta=4960.5,5066.3
XS Rating Curve= 0 ,0
Exp/Cntr=0.3,0.1

Type RM Length L Ch R = 1 ,205108  ,2041,2041,2041
BEGIN DESCRIPTION:
UPPER KEECHI CREEK 46.0
END DESCRIPTION:
XS GIS Cut Line= 3
      3665699.59     10577710.22      3667199.61     10575010.19
      3667999.61     10574210.18
#Sta/Elev= 30
  1906.5  327.93  1977.6  326.49  2034.8  324.66  2619.2  290.04  2775.9  285.23
  2900.6  285.57  3119.1  283.48  3199.2  285.41  3561.8  271.61  3702.5  271.76
    3714  273.51  3751.7  270.99  4288.3  269.97  4363.8  264.79  4412.9  264.78
  4434.7  268.23  4494.2  270.21  4949.5  270.17  4981.5  269.72  4987.2   265.4
  4992.4  264.14  5006.4  264.01  5009.1  263.51  5012.4  264.01  5023.5  270.09
  5037.6  270.44  5221.5  268.18  5589.2   288.3  6013.5   326.5  6126.6  332.05
#Mann= 7 ,-1 , 0
  1906.5     .16       0  1977.6      .1       0  2034.8     .05       0
  2900.6     .16       0  5006.4     .07       0  5012.4     .16       0
  5589.2     .05       0
#XS Ineff= 2 , 0
       0 4497.73  270.41               0
Permanent Ineff=
       T       F
Bank Sta=4949.5,5037.6
XS Rating Curve= 0 ,0
Exp/Cntr=0.3,0.1

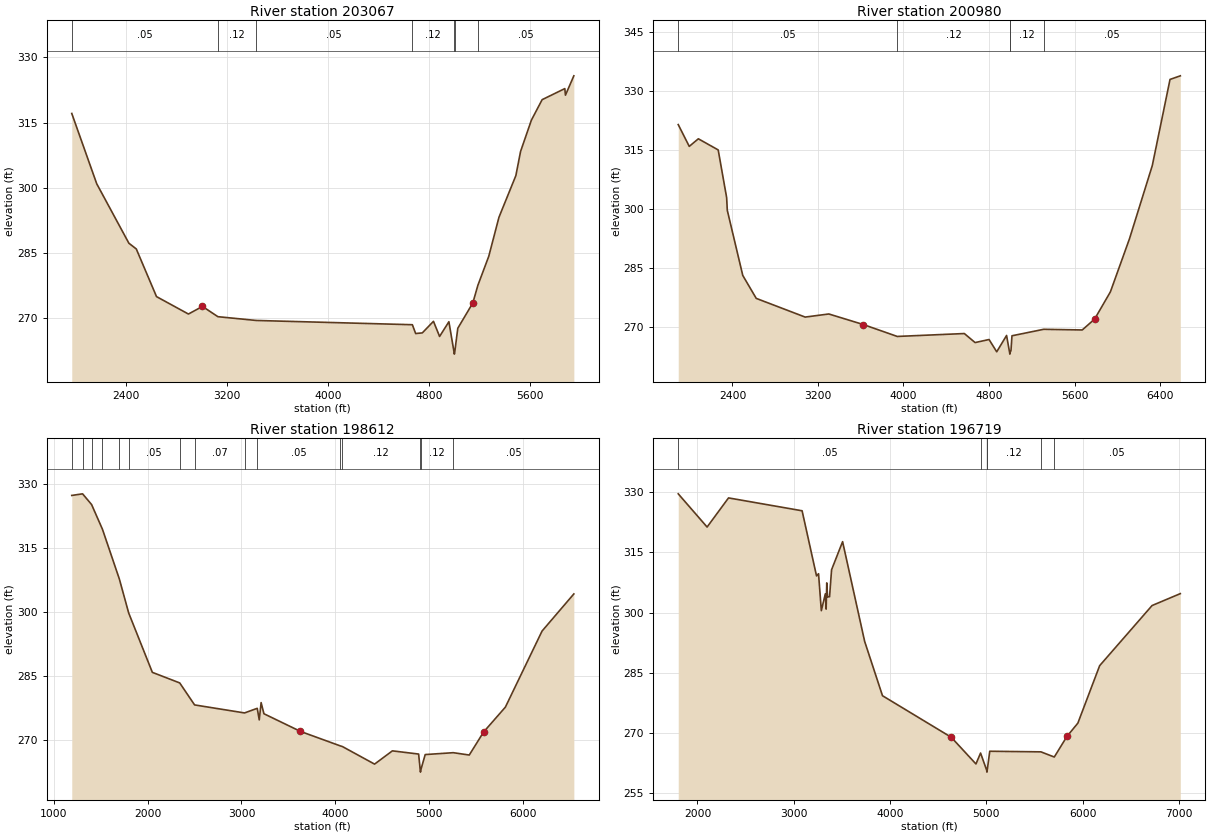
Type RM Length L Ch R = 1 ,203067  ,2087,2087,2087
BEGIN DESCRIPTION:
Mapping XS 857291e0
END DESCRIPTION:
XS GIS Cut Line= 3
      3669122.18     10578017.92      3668037.11     10574654.22
      3668069.66     10574220.22
#Sta/Elev= 30
    1975  317.12  2172.3  300.93  2426.4  287.25  2485.2  285.92  2645.1  274.95
  2897.3  270.94  3008.5  272.69  3130.3  270.33    3433  269.46  4667.9  268.48
    4694  266.45  4746.6   266.6  4834.7  269.26  4883.2  265.78  4956.7  269.17
  4997.2  262.21  4999.9  261.71  5003.2  262.21    5027  267.66  5145.9  273.49
  5185.6  277.53  5271.9  284.23  5352.7  293.23  5486.2  302.81  5523.4  308.37
  5609.1  315.59  5693.9  320.29  5873.2  322.84  5878.2  321.33  5944.6  325.78
#Mann= 7 ,-1 , 0
    1975     .05       0  3130.3     .12       0    3433     .05       0
  4667.9     .12       0  4997.2     .07       0  5003.2     .12       0
  5185.6     .05       0
Bank Sta=3008.5,5145.9
XS Rating Curve= 0 ,0
Exp/Cntr=0.3,0.1

Type RM Length L Ch R = 1 ,200980  ,2368,2368,2368
BEGIN DESCRIPTION:
Mapping XS e2bb7db4
END DESCRIPTION:
XS GIS Cut Line= 4
      3669295.79     10577920.28      3668970.27     10575012.29
      3669154.73     10574198.49      3668861.78     10573308.77
#Sta/Elev= 30
  1892.6  321.49  1995.7  315.94  2080.9  317.87  2266.4  315.04  2345.5  302.91
  2351.6  299.67  2496.4  283.09  2622.3  277.25  3080.1  272.49  3301.4  273.28
  3623.4   270.6  3941.7  267.56  4569.3   268.3  4669.9     266  4800.7  266.78
  4872.2  263.65  4964.5  267.81  4992.2  263.56    4995  263.06  4998.2  263.56
  5005.5  263.93    5015  267.73    5312  269.38  5672.5  269.21  5788.3  271.98
  5935.7   278.9  6114.6  292.44  6327.8  311.06  6493.7  332.98  6589.9   333.9
#Mann= 5 ,-1 , 0
  1892.6     .05       0  3941.7     .12       0  4992.2     .07       0
  4998.2     .12       0    5312     .05       0
Bank Sta=3623.4,5788.3
XS Rating Curve= 0 ,0
Exp/Cntr=0.3,0.1

Type RM Length L Ch R = 1 ,198612  ,1893,1893,1893
BEGIN DESCRIPTION:
Mapping XS b373e2bf
END DESCRIPTION:
XS GIS Cut Line= 3
      3670370.01     10578039.65      3670304.91     10573742.76
      3669849.19     10572787.92
#Sta/Elev= 30
  1190.4   327.4  1305.7  327.78    1402  325.26    1518  319.45  1698.1  307.78
  1797.7  299.81    2050  285.89  2341.9  283.41  2500.5  278.25  3033.3  276.37
  3168.8  277.45  3190.1  274.74  3210.1  278.79  3240.1  276.18  3630.1  272.03
    4054  268.64  4076.5  268.49  4420.2  264.36  4610.3  267.47  4890.3  266.72
  4907.3  262.98    4910  262.48  4913.3  262.98  4960.3   266.6  5259.8  267.04
  5430.3  266.49  5583.1  271.89  5815.5  277.73  6206.8  295.58  6545.8  304.29
#Mann= 15 ,-1 , 0
  1190.4     .05       0  1305.7     .16       0    1402     .12       0
    1518     .16       0  1698.1     .12       0  1797.7     .05       0
  2341.9     .12       0  2500.5     .07       0  3033.3     .12       0
  3168.8     .05       0    4054     .07       0  4076.5     .12       0
  4907.3     .07       0  4913.3     .12       0  5259.8     .05       0
Bank Sta=3630.1,5583.1
XS Rating Curve= 0 ,0
Exp/Cntr=0.3,0.1

Type RM Length L Ch R = 1 ,196719  ,447,447,447
BEGIN DESCRIPTION:
Mapping XS a2bf4676
END DESCRIPTION:
XS GIS Cut Line= 3
       3673260.8     10576819.59      3671143.15     10574008.61
      3669944.87     10572810.34
#Sta/Elev= 30
  1800.4  329.62  2100.1  321.33  2322.6   328.6  3086.7  325.39  3236.6  309.13
  3257.4  309.68  3286.5  300.46  3328.2  304.68  3336.5  300.85  3342.8  307.39
  3351.1  303.88  3371.9  303.94  3392.7  310.66  3507.3  317.68  3736.3  292.79
  3921.6  279.23  4635.7  268.86  4892.1   262.2  4940.2  264.92  5003.3  260.66
  5006.1  260.16  5009.3  260.66  5035.5  265.37    5567  265.22  5705.7  263.93
  5837.4  269.08  5950.5  272.39  6176.8  286.73  6721.2  301.74  7014.4  304.71
#Mann= 6 ,-1 , 0
  1800.4     .05       0  4940.2     .12       0  5003.3     .07       0
  5009.3     .12       0    5567     .16       0  5705.7     .05       0
Bank Sta=4635.7,5837.4
XS Rating Curve= 0 ,0
Exp/Cntr=0.3,0.1