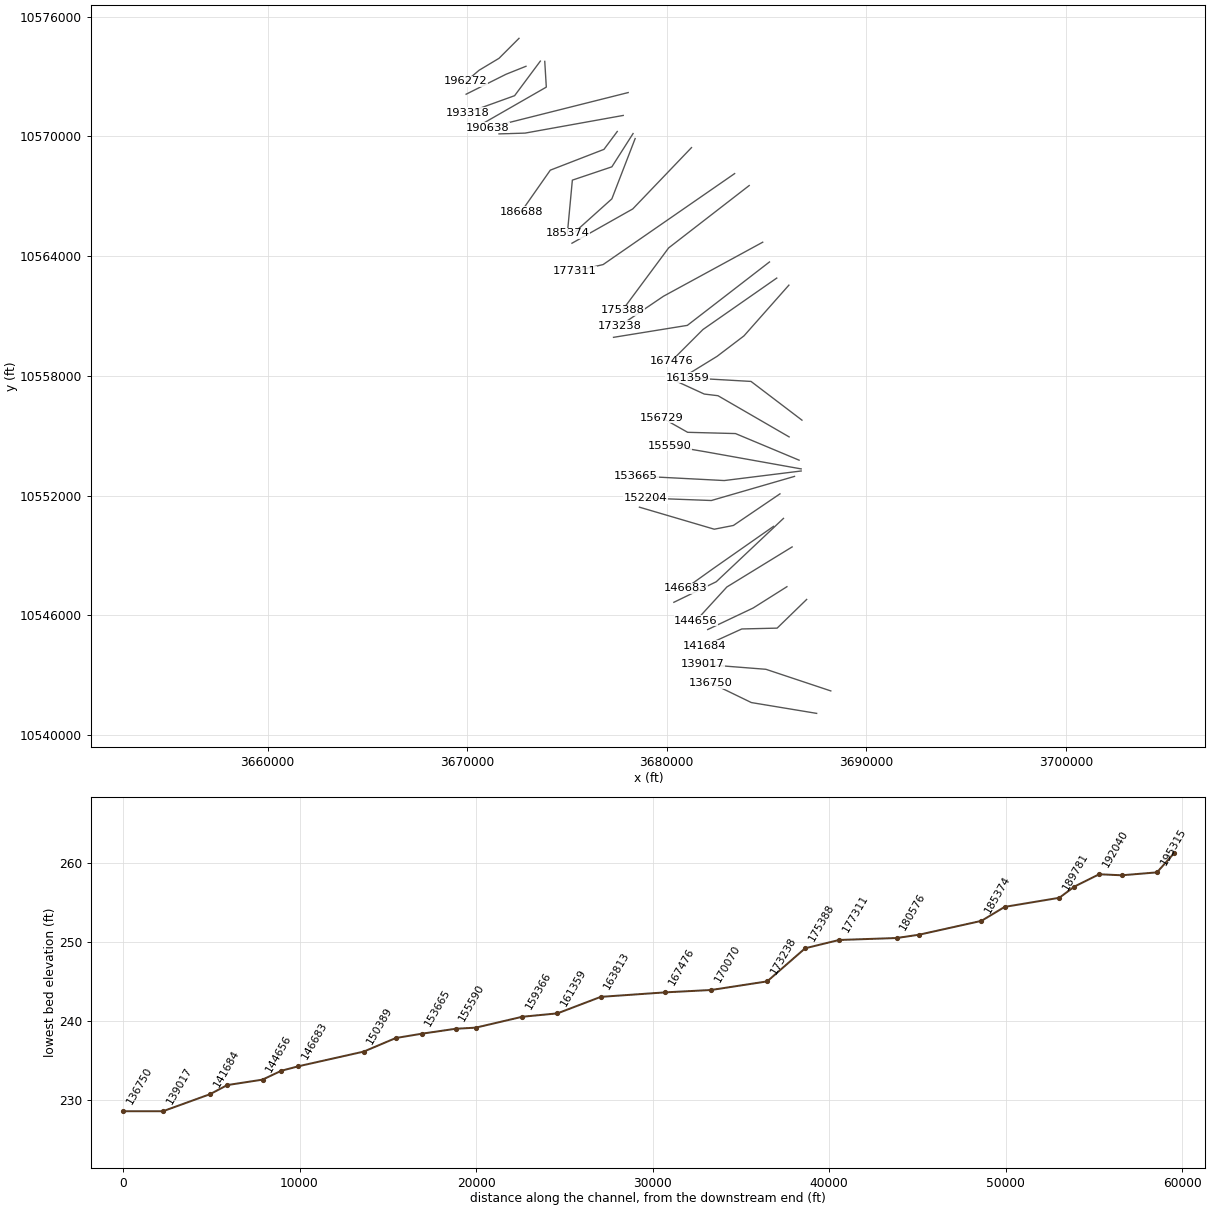
HEC-RAS study UPPER KEECHI CREEK.prj: UPPER KEECHI CREEK Base Level Engineering

--- UPPER KEECHI CREEK.g01 (geometry) --- (continued)

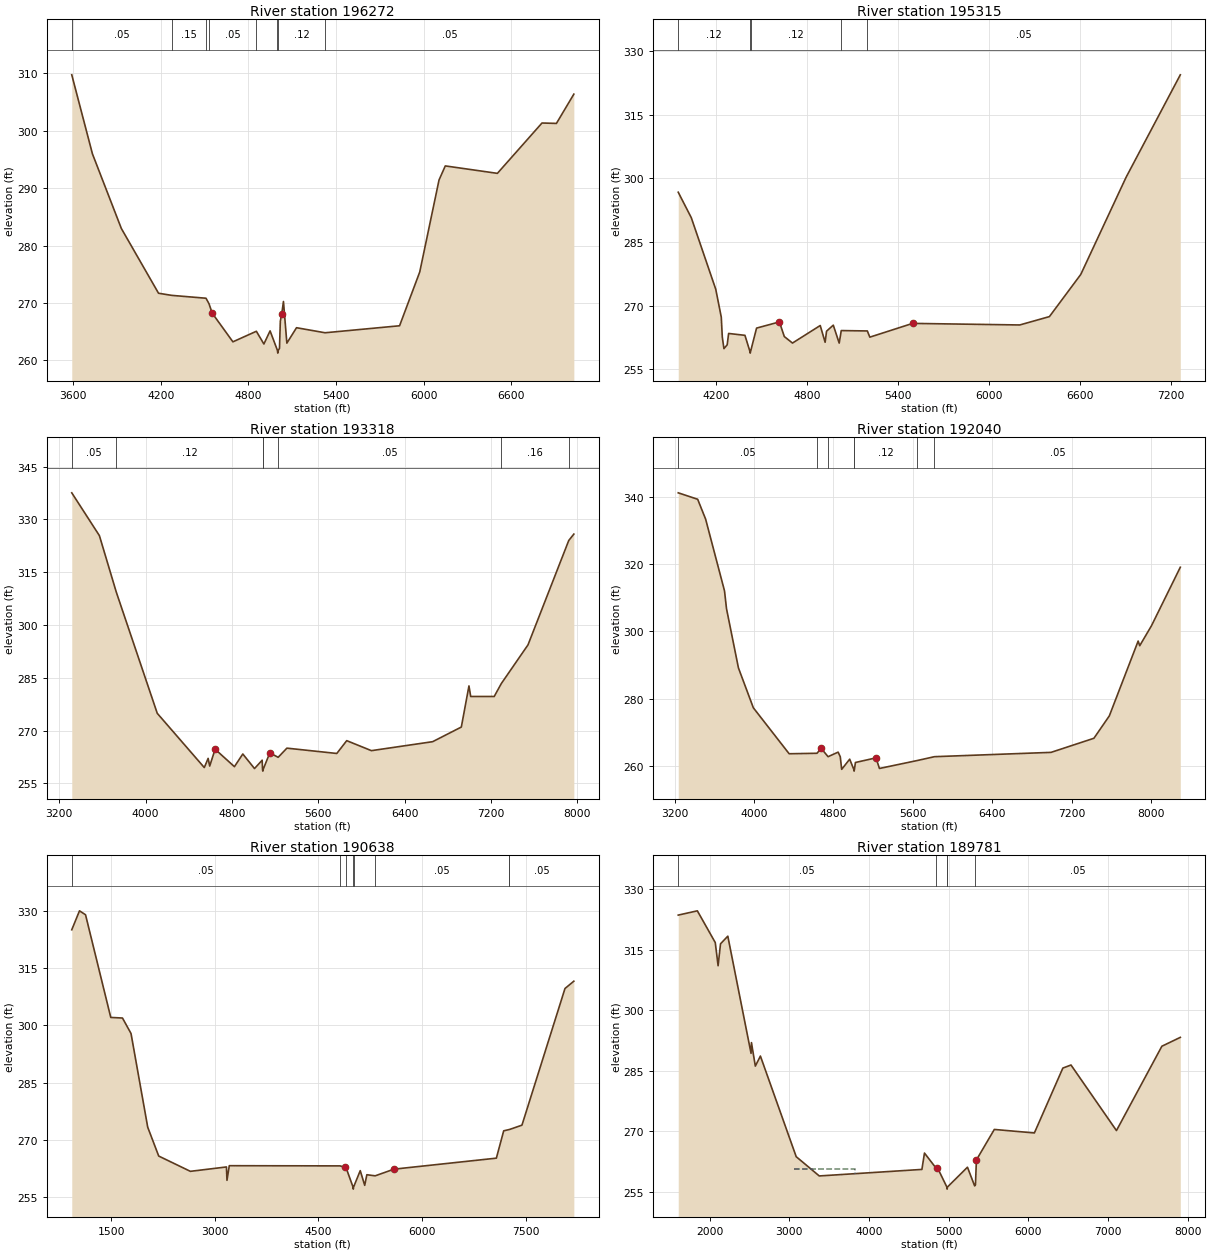
Type RM Length L Ch R = 1 ,196272  ,957,957,957
BEGIN DESCRIPTION:
UPPER KEECHI CREEK 45.0
END DESCRIPTION:
XS GIS Cut Line= 4
       3672599.6     10574910.18      3671599.61     10573910.19
      3670599.61     10573310.19      3669946.84     10572755.36
#Sta/Elev= 30
  3590.7  309.76  3732.1  295.99  3930.1  282.97  4184.7  271.68  4274.8  271.31
  4509.7  270.81  4530.3  269.84  4552.4   268.2  4693.8  263.21  4854.4  265.05
  4905.9  262.83  4948.3  265.12  4998.4  261.74  5001.1  261.24  5004.4  261.74
  5012.7  262.06  5018.5  266.82  5028.2  268.08  5039.9  270.24  5063.2  262.98
  5129.3  265.67  5324.7  264.79  5834.8  266.01  5972.8  275.38    6105  291.43
  6147.8  293.88  6504.4  292.58  6809.8  301.36  6908.6  301.29  7027.8  306.39
#Mann= 8 ,-1 , 0
  3590.7     .05       0  4274.8     .15       0  4509.7      .1       0
  4530.3     .05       0  4854.4     .12       0  4998.4     .07       0
  5004.4     .12       0  5324.7     .05       0
Bank Sta=4552.4,5028.2
XS Rating Curve= 0 ,0
Exp/Cntr=0.3,0.1

Type RM Length L Ch R = 1 ,195315  ,1997,1997,1997
BEGIN DESCRIPTION:
UPPER KEECHI CREEK 44.0
END DESCRIPTION:
XS GIS Cut Line= 3
      3672949.57     10573510.17      3671949.61     10573110.19
      3669949.57     10572110.17
#Sta/Elev= 30
  3950.8  296.72  4036.9  290.73  4198.5  273.86  4234.8  267.32  4241.6  262.62
  4252.3   259.9  4273.9   260.8  4283.3  263.47    4391  263.03    4423  259.34
  4425.7  258.84    4429  259.34  4467.7  264.73 4618.44  266.19  4650.8  262.74
  4704.7  261.21  4887.8  265.34  4920.1   261.4  4929.5     264  4973.9  265.43
    5013   261.2  5026.6  264.15  5198.7  264.06  5215.1   262.6  5497.4  265.84
  6204.5  265.47  6400.2  267.44    6607  277.36  6906.1  300.24  7263.9  324.36
#Mann= 5 ,-1 , 0
  3950.8     .12       0    4423     .07       0    4429     .12       0
  5026.6     .16       0  5198.7     .05       0
Bank Sta=4618.44,5497.4
XS Rating Curve= 0 ,0
Exp/Cntr=0.3,0.1

Type RM Length L Ch R = 1 ,193318  ,1278,1278,1278
BEGIN DESCRIPTION:
Mapping XS a1ebd5df
END DESCRIPTION:
XS GIS Cut Line= 3
      3673668.62     10573768.79      3672379.56     10572037.03
      3670035.85     10571190.69
#Sta/Elev= 30
    3316  337.57  3571.9  325.41  3728.1  309.38  4107.9   274.9  4543.7  259.48
  4579.2   262.1  4593.8  259.91  4643.8  264.69  4822.7  259.74  4900.3  263.34
  5008.8   259.2  5079.7  261.58    5083  258.97  5085.7  258.47    5089  258.97
  5150.6  263.66  5227.8   262.4  5308.9     265  5770.9  263.49    5863  267.13
  6091.5  264.29  6659.1  266.84  6924.5     271  6995.2  282.69  7011.2  279.69
  7229.1  279.69  7294.3  283.33    7542  294.35  7919.5  324.02  7966.7  325.84
#Mann= 7 ,-1 , 0
    3316     .05       0  3728.1     .12       0    5083     .07       0
    5089     .12       0  5227.8     .05       0  7294.3     .16       0
  7919.5     .05       0
Bank Sta=4643.8,5150.6
XS Rating Curve= 0 ,0
Exp/Cntr=0.3,0.1

Type RM Length L Ch R = 1 ,192040  ,1402,1402,1402
BEGIN DESCRIPTION:
Mapping XS 57192e8f
END DESCRIPTION:
XS GIS Cut Line= 3
      3673889.98     10573755.74       3673968.1     10572466.72
      3670699.84      10570591.7
#Sta/Elev= 30
  3236.6  341.09  3432.5  339.18  3512.7  333.29    3703  312.02    3723  306.75
  3843.3  289.19  3993.5  277.37  4354.2  263.75  4634.9  263.89  4676.8  265.35
  4746.5  262.88  4847.9  264.23  4869.5  262.85  4883.6  259.13  4964.3  262.14
    5006   259.1  5008.8   258.6    5012   259.1    5022  261.16  5229.1  262.53
  5264.1  259.39  5638.7   261.7  5818.3  262.88  6993.4  264.16  7425.3  268.34
  7580.6  274.97  7871.1  297.15  7886.9  295.77  8004.9  301.67  8295.9  319.03
#Mann= 7 ,-1 , 0
  3236.6     .05       0  4634.9     .07       0  4746.5     .12       0
    5006     .07       0    5012     .12       0  5638.7     .16       0
  5818.3     .05       0
Bank Sta=4676.8,5229.1
XS Rating Curve= 0 ,0
Exp/Cntr=0.3,0.1

Type RM Length L Ch R = 1 ,190638  ,857,857,857
BEGIN DESCRIPTION:
UPPER KEECHI CREEK 43.0
END DESCRIPTION:
XS GIS Cut Line= 2
      3678069.64     10572193.28      3671025.41     10570422.45
#Sta/Elev= 30
   931.1  325.12  1042.9  330.09  1130.3  329.06  1495.3  302.11    1665  301.95
  1788.4  297.88    2030  273.29  2189.1  265.72    2647  261.71  3168.7  262.86
  3176.5  259.35  3209.9  263.19  4813.3  263.14  4890.6  262.72  4902.4   262.5
    5001  257.54  5003.8  257.04    5007  257.54  5104.5  261.89    5169  258.03
  5199.9  260.82  5320.5  260.53  5591.8  262.28  7073.6  265.17  7179.7  272.34
  7259.3  272.68  7261.7  272.68  7443.8  273.83  8066.4   309.7  8194.5  311.62
#Mann= 8 ,-1 , 0
   931.1     .05       0  4813.3     .07       0  4902.4     .12       0
    5001     .07       0    5007     .12       0  5320.5     .05       0
  7259.3     .15       0  7261.7     .05       0
#XS Ineff= 1 ,-1
 1996.24 3212.73  263.17
Permanent Ineff=
       T
Bank Sta=4890.6,5591.8
XS Rating Curve= 0 ,0
Exp/Cntr=0.3,0.1

Type RM Length L Ch R = 1 ,189781  ,3093,3093,3093
BEGIN DESCRIPTION:
UPPER KEECHI CREEK 42.0
END DESCRIPTION:
XS GIS Cut Line= 3
      3677822.23     10571047.44      3672900.39     10570162.03
      3671598.32     10570122.97
#Sta/Elev= 30
  1605.6  323.62  1845.6  324.68  2070.4  316.81  2106.1  311.06  2136.6   316.5
  2228.1  318.39  2519.8  289.32  2524.9  291.98  2573.5  286.15  2637.3  288.64
  3086.7  263.67  3376.2  258.89  4664.9  260.51  4697.1  264.57  4839.7  260.91
  4859.6  260.96  4978.6  256.12  4981.3  255.62  4984.6  256.12  5236.9  261.06
  5326.8  256.42  5337.2  256.68  5349.2  262.86    5574  270.43    6077  269.56
  6434.5  285.66  6536.7  286.42  7107.4  270.15  7677.7  291.08  7909.1  293.28
#Mann= 5 ,-1 , 0
  1605.6     .05       0  4839.7     .12       0  4978.6     .07       0
  4984.6     .12       0  5326.8     .05       0
#XS Ineff= 1 ,-1
 3055.33 3821.99  260.72
Permanent Ineff=
       T
Bank Sta=4859.6,5349.2
XS Rating Curve= 0 ,0
Exp/Cntr=0.3,0.1

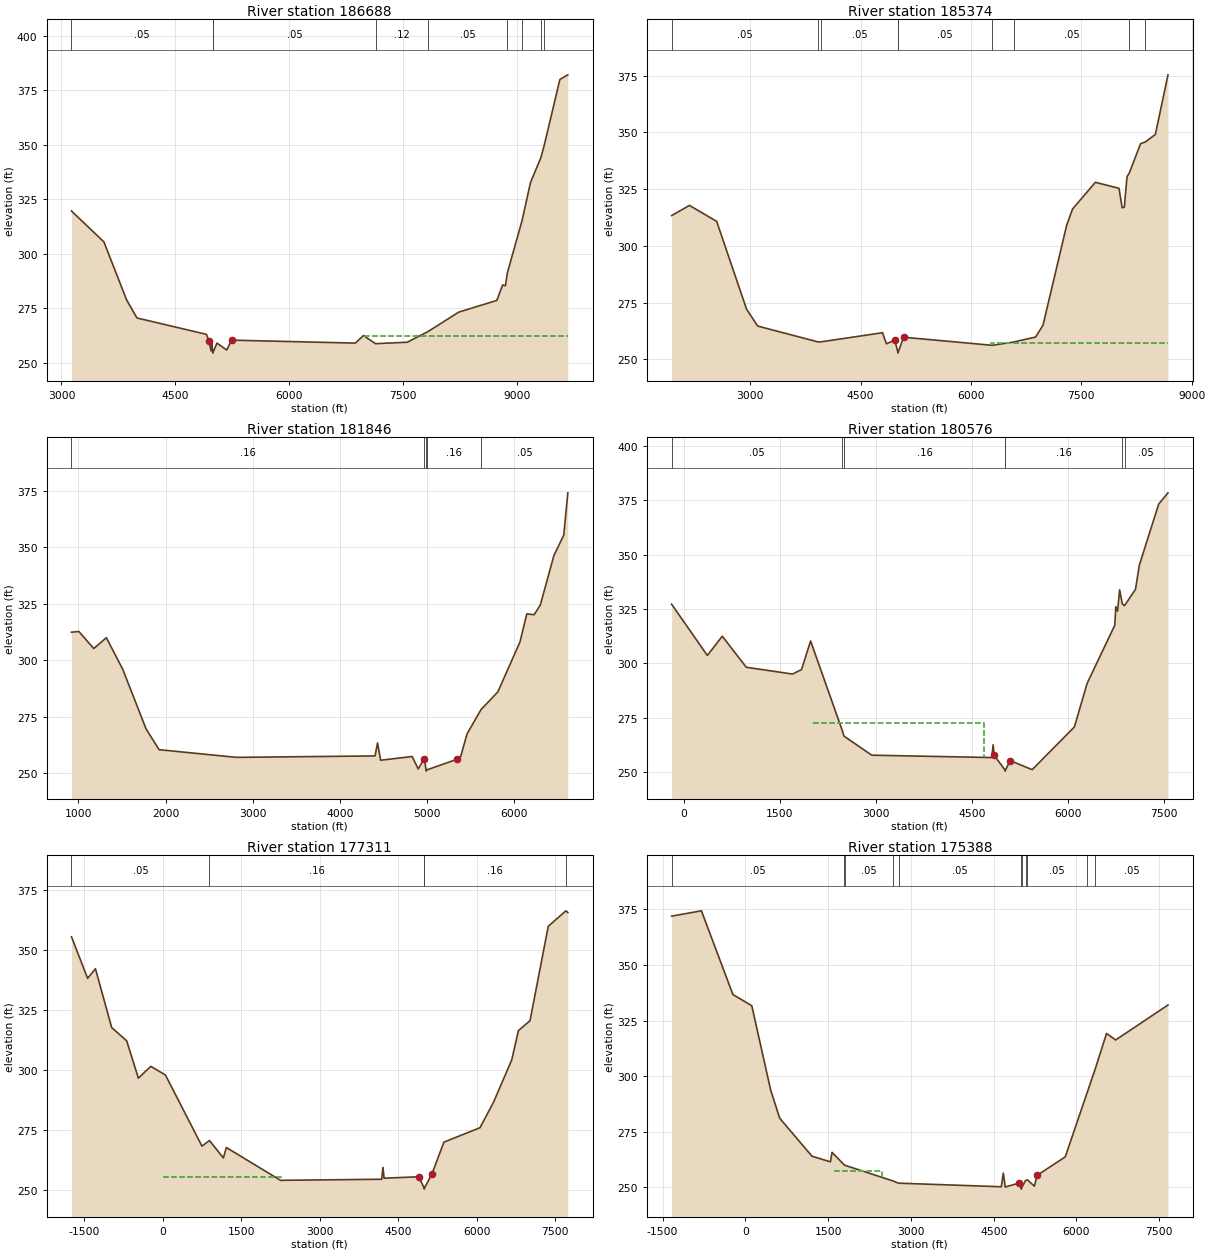
Type RM Length L Ch R = 1 ,186688  ,1314,1314,1314
BEGIN DESCRIPTION:
UPPER KEECHI CREEK 41.0
END DESCRIPTION:
XS GIS Cut Line= 4
      3677522.79     10570243.63      3676856.12      10569347.8
      3674168.62     10568306.13      3672711.11     10566223.96
#Sta/Elev= 30
  3131.9   319.6  3559.1  305.46  3859.2  278.81    3995  270.58  4909.8  263.09
    4942  260.24    4972  255.47  4977.4  259.64  4992.6  254.97  4995.3  254.47
  4998.6  254.97  5049.2  259.06  5177.9  255.89  5242.3  260.42  6872.4  259.06
  6979.7  262.53  7138.7   258.8  7557.8  259.47  7833.8  264.42  8233.6  273.24
  8736.6  278.63  8814.2  285.75    8850  285.33    8875  291.17  9070.1   315.3
  9180.4  332.66  9317.6   344.1  9360.7  349.59  9567.6   379.9  9672.5  382.03
#Mann= 9 ,-1 , 0
  3131.9     .05       0  4992.6     .03       0  4998.6     .05       0
  7138.7     .12       0  7833.8     .05       0    8875     .12       0
  9070.1     .16       0  9317.6     .12       0  9360.7     .16       0
#XS Ineff= 2 , 0
       0                 7001.86       0  262.49
Permanent Ineff=
       F       T
Bank Sta=4942,5242.3
XS Rating Curve= 0 ,0
Exp/Cntr=0.3,0.1

Type RM Length L Ch R = 1 ,185374  ,3528,3528,3528
BEGIN DESCRIPTION:
Mapping XS b1bb2c61
END DESCRIPTION:
XS GIS Cut Line= 4
      3678314.45     10570139.46      3677251.96      10568472.8
      3675272.79     10567806.13      3675022.79     10565139.48
#Sta/Elev= 30
  1934.2   313.3  2176.1  317.79  2545.9  310.75  2952.2  272.06  3103.7  264.62
  3922.3  257.65  3964.6  257.68  4799.6  261.69  4852.3   256.8  4965.7  258.44
  5007.6   253.2  5010.4   252.7  5013.6   253.2  5084.5  259.71  6289.8  256.14
    6581   257.6  6878.9  259.79  6979.4  264.99  7300.8  309.02  7381.1   316.2
  7690.6  327.96  8012.1  325.32  8054.1  316.77  8084.2  317.01  8120.9  330.39
  8152.7  332.15  8305.2  344.97  8369.9  345.76    8506  349.04  8677.5  375.32
#Mann= 9 ,-1 , 0
  1934.2     .05       0  3922.3     .07       0  3964.6     .05       0
  5007.6     .03       0  5013.6     .05       0  6289.8     .12       0
    6581     .05       0  8152.7     .16       0  8369.9     .05       0
#XS Ineff= 2 , 0
       0                 6274.88       0  257.35
Permanent Ineff=
       F       T
Bank Sta=4965.7,5084.5
XS Rating Curve= 0 ,0
Exp/Cntr=0.3,0.1

Type RM Length L Ch R = 1 ,181846  ,1270,1270,1270
BEGIN DESCRIPTION:
UPPER KEECHI CREEK 40.0
END DESCRIPTION:
XS GIS Cut Line= 3
      3678418.63     10569889.48      3677251.96     10566868.63
      3675419.98     10565224.01
#Sta/Elev= 30
   919.5  312.44  1004.5  312.75  1175.6   305.2    1320  310.02  1508.3  296.01
  1776.3  269.63  1925.5  260.44  2814.5  257.04    4406  257.68  4434.4  263.43
    4470  255.77  4831.4  257.42  4901.6  251.94  4967.2  256.17  4972.6  256.44
  4991.1  251.45  4993.9  250.95  4997.1  251.45  5341.2  256.11  5390.5  257.58
  5461.5  267.36  5624.5  278.28  5815.1  285.95    6070   308.1  6148.5  320.54
    6233  320.17    6304  324.52  6459.5  346.32  6573.1  355.45  6619.7  374.12
#Mann= 5 ,-1 , 0
   919.5     .16       0  4967.2     .12       0  4991.1     .07       0
  4997.1     .16       0  5624.5     .05       0
Bank Sta=4972.6,5341.2
XS Rating Curve= 0 ,0
Exp/Cntr=0.3,0.1

Type RM Length L Ch R = 1 ,180576  ,3265,3265,3265
BEGIN DESCRIPTION:
Mapping XS 0623f591
END DESCRIPTION:
XS GIS Cut Line= 3
      3681241.52     10569436.31      3678298.83     10566363.42
      3675253.76     10564645.69
#Sta/Elev= 30
  -191.6  327.21   365.8  303.67   599.2  312.51     974  298.25  1695.5  295.12
    1837   297.2  1978.2  310.32  2472.5  269.22  2498.2  266.66    2933  257.85
  4807.6  256.77  4829.3  262.64  4842.9  257.84  5015.5  251.03  5018.2  250.53
  5021.5  251.03  5093.6  255.38  5438.8  251.21  6097.4  270.82  6296.8  290.85
  6728.7  317.58  6744.6  326.09    6772  324.02  6803.8  333.84  6845.8  327.35
  6880.2  326.53  7052.2  334.08  7111.4  345.11  7413.4  373.17  7559.2  378.38
#Mann= 7 ,-1 , 0
  -191.6     .05       0  2472.5     .08       0  2498.2     .16       0
  5015.5     .03       0  5021.5     .16       0  6845.8     .08       0
  6880.2     .05       0
#XS Ineff= 1 ,-1
 2022.73  4687.5  272.65
Permanent Ineff=
       T
Bank Sta=4842.9,5093.6
XS Rating Curve= 0 ,0
Exp/Cntr=0.3,0.1

Type RM Length L Ch R = 1 ,177311  ,1923,1923,1923
BEGIN DESCRIPTION:
Mapping XS 637cf698
END DESCRIPTION:
XS GIS Cut Line= 3
      3683402.97     10568134.23      3676814.46     10563576.96
      3675383.36      10563238.7
#Sta/Elev= 30
 -1741.5  355.53 -1433.4  338.19 -1283.8  342.21  -973.6  317.66  -687.1  312.15
  -463.4  296.56  -227.5  301.49      53  297.89   751.1  268.21   894.3  270.56
  1159.9  263.29  1217.3  267.63    2252  253.95  4185.5   254.4  4208.4  259.37
  4230.1  254.83  4889.7  255.43  4995.8  250.78  4998.5  250.28  5001.8  250.78
  5143.1  256.55  5372.9  269.87  6062.2  275.89  6320.8  286.51  6669.3  304.22
  6796.2  316.39  7017.9  320.53  7366.5   359.9    7703  366.35  7740.1  365.66
#Mann= 5 ,-1 , 0
 -1741.5     .05       0   894.3     .16       0  4995.8     .03       0
  5001.8     .16       0    7703     .16       0
#XS Ineff= 2 , 0
       0 2268.56  255.24               0
Permanent Ineff=
       T       F
Bank Sta=4889.7,5143.1
XS Rating Curve= 0 ,0
Exp/Cntr=0.3,0.1

Type RM Length L Ch R = 1 ,175388  ,2150,2150,2150
BEGIN DESCRIPTION:
Mapping XS 84dbf269
END DESCRIPTION:
XS GIS Cut Line= 3
       3684132.2     10567535.32      3680095.71      10564410.3
      3677777.99     10561285.29
#Sta/Elev= 30
   -1337     372    -797  374.39  -226.6  336.74   115.7   331.7   457.9  293.74
   621.8  281.11  1206.7  264.03  1540.8  261.51  1569.8  265.76  1795.5  260.04
  1803.6  259.96  2669.2  252.95  2774.8  251.91  4637.9   250.3  4673.4  256.44
  4708.8   250.2  4959.2  251.93  4997.9  249.73  5000.7  249.23  5003.9  249.73
  5076.8   253.1  5110.5  253.41  5237.1  250.57  5286.9  255.44    5796  263.71
  6185.4  292.01  6344.6  303.65    6545  319.25  6709.9   316.3  7658.5  332.04
#Mann= 11 ,-1 , 0
   -1337     .05       0  1795.5     .08       0  1803.6     .05       0
  2669.2     .07       0  2774.8     .05       0  4997.9     .03       0
  5003.9     .05       0  5076.8     .07       0  5110.5     .05       0
  6185.4     .08       0  6344.6     .05       0
#XS Ineff= 1 ,-1
 1597.71  2468.7  257.35
Permanent Ineff=
       T
Bank Sta=4959.2,5286.9
XS Rating Curve= 0 ,0
Exp/Cntr=0.3,0.1

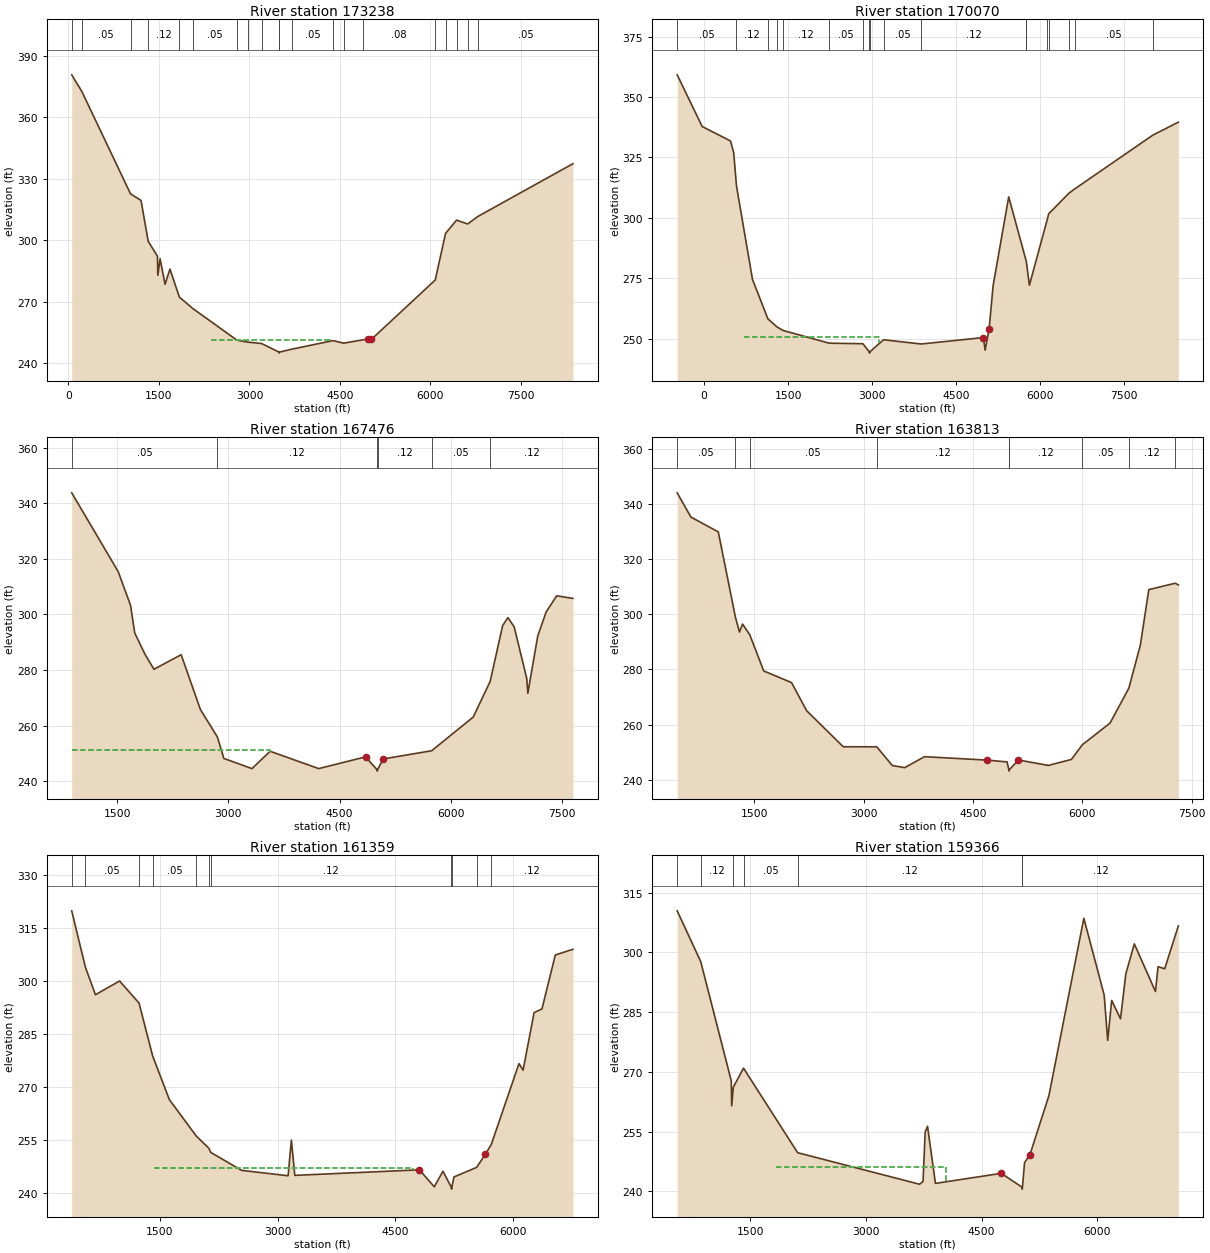
Type RM Length L Ch R = 1 ,173238  ,3168,3168,3168
BEGIN DESCRIPTION:
Mapping XS 22a86992
END DESCRIPTION:
XS GIS Cut Line= 3
      3684809.26     10564696.76      3679835.29     10561988.42
      3677648.62     10560504.61
#Sta/Elev= 30
    54.6   380.8   223.5   372.6  1029.1  322.76  1203.3  319.52  1322.1  299.56
  1475.8  292.32  1481.5  283.03  1519.5  291.06  1601.2   278.6  1682.4  286.06
  1839.5  272.32  2067.9  266.67    2796   251.3  2980.4  250.39    3201  249.73
    3490  245.54  3492.7  245.04    3496  245.54  3712.1  247.03  4385.7  251.14
  4562.9   249.9  4879.2  251.52  4961.7  251.94  5019.1  251.69  6079.5  280.71
  6250.1  303.42    6433  309.92  6616.4  308.03  6786.3  311.71  8360.7  337.43
#Mann= 20 ,-1 , 0
    54.6     .05       0   223.5     .05       0  1029.1     .08       0
  1322.1     .12       0  1839.5     .05       0  2067.9     .05       0
    2796     .12       0  2980.4     .16       0    3201     .12       0
    3490     .07       0    3496     .12       0  3712.1     .05       0
  4385.7     .12       0  4562.9     .12       0  4879.2     .08       0
  6079.5     .08       0  6250.1     .05       0    6433     .08       0
  6616.4     .16       0  6786.3     .05       0
#XS Ineff= 1 ,-1
 2356.13  4330.6  251.27
Permanent Ineff=
       T
Bank Sta=4961.7,5019.1
XS Rating Curve= 0 ,0
Exp/Cntr=0.3,0.1

Type RM Length L Ch R = 1 ,170070  ,2594,2594,2594
BEGIN DESCRIPTION:
Mapping XS 810efcaa
END DESCRIPTION:
XS GIS Cut Line= 3
      3685147.83      10563707.2      3681033.21     10560530.09
      3677335.27     10559931.13
#Sta/Elev= 30
  -480.6   359.2   -34.9   337.8   471.4  331.82   527.9     327   577.8  313.17
   863.5  274.45    1138  258.15  1300.1  254.81  1407.9  253.35  2231.5  248.07
  2833.3  247.85    2950  244.45  2952.8  243.95    2956  244.45  3202.5  249.49
  3873.4  247.73  4984.9   250.4  5015.3  245.19  5086.2   253.8  5157.1  271.75
  5436.1  308.66  5751.3  281.83  5752.3  281.54  5805.5  272.08  6121.8  299.09
  6149.8  301.65    6511  310.17  6622.5  312.08  8005.4  334.18    8464   339.6
#Mann= 18 ,-1 , 0
  -480.6     .05       0   577.8     .12       0    1138     .05       0
  1300.1     .07       0  1407.9     .12       0  2231.5     .05       0
  2833.3     .12       0    2950     .07       0    2956     .12       0
  3202.5     .05       0  3873.4     .12       0  5751.3     .07       0
  5752.3     .12       0  6121.8     .07       0  6149.8     .12       0
    6511     .16       0  6622.5     .05       0  8005.4     .08       0
#XS Ineff= 1 ,-1
  713.64 3127.27  250.81
Permanent Ineff=
       T
Bank Sta=4984.9,5086.2
XS Rating Curve= 0 ,0
Exp/Cntr=0.3,0.1

Type RM Length L Ch R = 1 ,167476  ,3663,3663,3663
BEGIN DESCRIPTION:
Mapping XS df5b569f
END DESCRIPTION:
XS GIS Cut Line= 3
      3685512.35     10562899.87      3681814.46     10560321.75
      3680226.93     10558734.22
#Sta/Elev= 30
   889.7  343.73  1515.4  315.43    1682  303.28  1738.7  293.34  1875.7  285.72
  1997.9  280.28  2364.3  285.52  2623.5  265.81  2851.3  255.98  2939.3  248.21
  3318.9  244.56  3562.7  250.79  4217.5  244.56  4849.2  248.77  5004.1  244.15
  5006.9  243.65  5010.1  244.15  5086.6  248.02  5740.1  250.98  6300.2  263.11
  6528.2  275.92  6696.1  295.99  6766.8  298.87  6851.7  295.52  7021.4  276.93
  7035.5  271.65  7169.9  292.33    7283  300.91  7424.5  306.69  7642.7  305.77
#Mann= 6 ,-1 , 0
   889.7     .05       0  2851.3     .12       0  5004.1     .07       0
  5010.1     .12       0  5740.1     .05       0  6528.2     .12       0
#XS Ineff= 2 , 0
       0 3556.63  251.17               0
Permanent Ineff=
       T       F
Bank Sta=4849.2,5086.6
XS Rating Curve= 0 ,0
Exp/Cntr=0.3,0.1

Type RM Length L Ch R = 1 ,163813  ,2454,2454,2454
BEGIN DESCRIPTION:
Mapping XS 9ed4bd6d
END DESCRIPTION:
XS GIS Cut Line= 4
      3686120.32     10562545.16      3683870.34      10560003.5
      3682518.78     10558975.73      3680999.72     10558042.59
#Sta/Elev= 30
   442.7  344.08     631  335.28  1006.6  329.91  1241.2  298.97  1296.8  293.57
  1339.4  296.44    1438  292.59  1629.7  279.45  2011.9   275.2  2217.7  265.03
  2720.4  251.93    3180   251.9  3393.7  245.12  3563.5  244.34    3836  248.32
  4696.1  247.08  4968.4  246.42  4992.5  243.58  4995.2  243.08  4998.5  243.58
  5124.4  247.11  5535.1  245.15    5851  247.33  6001.4  252.67  6380.9  260.52
  6638.1  273.16  6796.4  288.77  6912.4  308.94    7274  311.27  7317.9  310.66
#Mann= 9 ,-1 , 0
   442.7     .05       0  1241.2     .16       0    1438     .05       0
    3180     .12       0  4992.5     .07       0  4998.5     .12       0
  6001.4     .05       0  6638.1     .12       0    7274     .05       0
#XS Ineff= 1 ,-1
  2568.4 3839.06  248.31
Permanent Ineff=
       T
Bank Sta=4696.1,5124.4
XS Rating Curve= 0 ,0
Exp/Cntr=0.3,0.1

Type RM Length L Ch R = 1 ,161359  ,1993,1993,1993
BEGIN DESCRIPTION:
UPPER KEECHI CREEK 39.0
END DESCRIPTION:
XS GIS Cut Line= 3
      3686775.15       10555782.      3684223.06     10557722.11
      3681045.99      10557904.4
#Sta/Elev= 30
   377.1  319.91   551.5  303.91   679.5  296.12     987  300.01  1235.3  293.74
  1407.7  278.82  1621.5  266.38  1963.9  256.06  2123.2  252.63  2149.4   251.4
  2542.7  246.31    3135  244.78  3176.9   254.9  3220.6  244.89  4808.4  246.46
  4998.7  241.65  5108.9  246.06    5216  241.49  5218.8  240.99    5222  241.49
  5249.1  244.43  5538.1  247.15 5647.73  250.81  5725.3  253.67  6078.1  276.59
  6130.5  274.72  6270.8  291.05  6370.9  292.09  6541.2  307.39  6765.2     309
#Mann= 11 ,-1 , 0
   377.1     .16       0   551.5     .05       0  1235.3     .16       0
  1407.7     .05       0  1963.9     .12       0  2123.2     .16       0
  2149.4     .12       0    5216     .07       0    5222     .12       0
  5538.1     .05       0  5725.3     .12       0
#XS Ineff= 1 ,-1
 1426.53 4728.47  246.98
Permanent Ineff=
       T
Bank Sta=4808.4,5647.73
XS Rating Curve= 0 ,0
Exp/Cntr=0.3,0.1

Type RM Length L Ch R = 1 ,159366  ,2637,2637,2637
BEGIN DESCRIPTION:
Mapping XS 92656432
END DESCRIPTION:
XS GIS Cut Line= 4
      3686131.93     10554943.45      3682569.41     10557005.96
      3681881.91      10557089.3      3680340.27     10557797.62
#Sta/Elev= 30
   548.8  310.43   854.2  297.68  1250.7  267.74  1256.5  261.47  1277.2  266.15
  1409.9  270.93  2111.9  249.71  3694.4  241.79  3740.3  242.48  3767.6  254.85
  3798.4  256.33    3901     242  4755.7  244.52  5024.7  241.06  5027.5  240.56
  5030.7  241.06  5057.9  247.22  5128.5  249.25  5374.4  264.05  5827.5  308.55
  6091.3   289.3  6137.3  277.91  6188.8  287.93  6303.7  283.31  6372.6  294.62
  6482.9  302.13  6756.8  290.18    6791  296.41  6877.2  295.88  7054.4  306.65
#Mann= 7 ,-1 , 0
   548.8     .05       0   854.2     .12       0  1277.2     .16       0
  1409.9     .05       0  2111.9     .12       0  5024.7     .07       0
  5030.7     .12       0
#XS Ineff= 1 ,-1
  1837.5 4035.51  246.14
Permanent Ineff=
       T
Bank Sta=4755.7,5128.5
XS Rating Curve= 0 ,0
Exp/Cntr=0.3,0.1

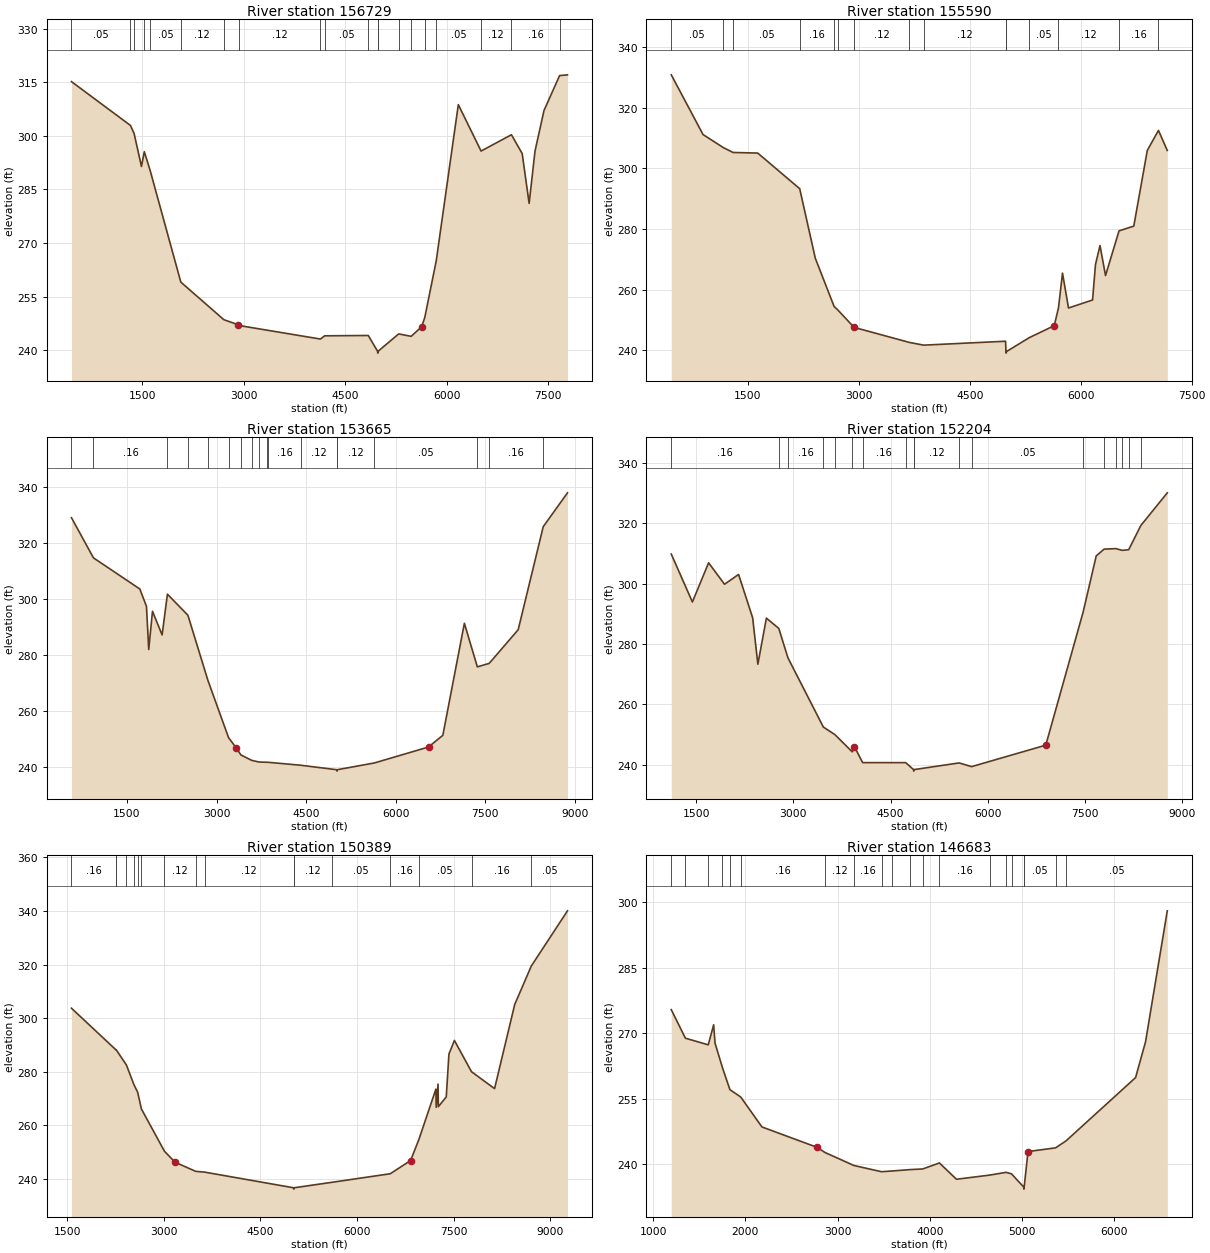
Type RM Length L Ch R = 1 ,156729  ,1139,1139,1139
BEGIN DESCRIPTION:
UPPER KEECHI CREEK 38.0
END DESCRIPTION:
XS GIS Cut Line= 4
      3686631.96     10553776.78      3683444.41     10555110.13
      3681048.58     10555172.63      3679756.91      10555901.8
#Sta/Elev= 30
   450.9  315.18  1322.9  302.92  1377.1  300.67    1486  291.42    1528  295.57
  1614.8  290.29  2068.1  259.06  2704.4  248.54  2908.6  247.17  2922.3  246.93
  4132.7  243.12  4195.2  244.02  4839.7  244.12  4978.2  239.68    4981  239.18
  4984.2  239.68  5289.6  244.56  5474.7  243.88  5630.2  246.57  5676.1   249.2
  5845.2  265.03  6171.7  308.74  6508.1  295.74  6957.5  300.31  7116.4  295.03
  7218.9  281.09  7305.5   295.7  7438.4  307.08  7669.1  316.86    7786  317.08
#Mann= 20 ,-1 , 0
   450.9     .05       0  1322.9     .16       0  1377.1     .05       0
    1528     .16       0  1614.8     .05       0  2068.1     .12       0
  2704.4     .16       0  2922.3     .12       0  4132.7     .16       0
  4195.2     .05       0  4839.7     .12       0  4978.2     .07       0
  4984.2     .12       0  5289.6     .16       0  5474.7     .05       0
  5676.1     .16       0  5845.2     .05       0  6508.1     .12       0
  6957.5     .16       0  7669.1     .05       0
Bank Sta=2908.6,5630.2
XS Rating Curve= 0 ,0
Exp/Cntr=0.3,0.1

Type RM Length L Ch R = 1 ,155590  ,1925,1925,1925
BEGIN DESCRIPTION:
UPPER KEECHI CREEK 37.0
END DESCRIPTION:
XS GIS Cut Line= 3
      3686736.03      10553339.3      3681965.25     10554193.46
      3680133.22     10554505.74
#Sta/Elev= 30
   465.4  330.77   894.8  311.09    1169  306.79  1300.4  305.18  1634.4  304.98
  2201.5  293.24  2412.3  270.33  2666.1  254.45  2723.4   253.1  2936.6  247.53
  3682.3  242.58  3877.6  241.67  4984.5  242.96  4989.7  239.54  4992.4  239.04
  4995.7  239.54  5304.7  244.14  5642.4  248.09  5699.8  253.97    5754  265.41
  5835.1  253.91  6160.2  256.55  6200.3   268.3  6261.2   274.5  6335.6  264.61
  6518.3  279.34  6717.7  280.91  6900.3  305.84  7051.1  312.45  7170.5  305.85
#Mann= 15 ,-1 , 0
   465.4     .05       0    1169     .16       0  1300.4     .05       0
  2201.5     .16       0  2666.1     .05       0  2723.4     .16       0
  2936.6     .12       0  3682.3     .16       0  3877.6     .12       0
  4989.7     .07       0  4995.7     .12       0  5304.7     .05       0
  5699.8     .12       0  6518.3     .16       0  7051.1      .1       0
Bank Sta=2936.6,5642.4
XS Rating Curve= 0 ,0
Exp/Cntr=0.3,0.1

Type RM Length L Ch R = 1 ,153665  ,1461,1461,1461
BEGIN DESCRIPTION:
Mapping XS b49bf218
END DESCRIPTION:
XS GIS Cut Line= 4
      3686736.07     10553235.13      3682881.91     10552755.96
      3682090.25     10552797.63      3678465.29     10552985.13
#Sta/Elev= 30
   570.3     329   938.8  314.64  1715.5  303.51  1826.4   297.3  1864.2  281.89
  1927.1  295.55  2088.4  287.09    2177  301.67  2520.3  294.13  2854.2  270.92
  3200.6   250.4  3329.3   246.7  3407.6   244.2    3589  242.25  3711.6  241.67
  3841.4  241.58  3865.7  241.56  4415.4   240.5  5014.2  238.91    5017  238.41
  5020.2  238.91  5642.9  241.33  6549.3  247.03  6789.6  251.22  7150.1  291.25
  7367.3  275.68  7565.7  276.92  8051.3  288.96  8470.5  325.78  8876.7  337.89
#Mann= 18 ,-1 , 0
   570.3     .05       0   938.8     .16       0    2177     .05       0
  2520.3     .16       0  2854.2     .05       0  3200.6     .12       0
  3407.6     .16       0    3589     .12       0  3711.6     .16       0
  3841.4     .12       0  3865.7     .16       0  4415.4     .12       0
  5014.2     .07       0  5020.2     .12       0  5642.9     .05       0
  7367.3     .12       0  7565.7     .16       0  8470.5     .05       0
Bank Sta=3329.3,6549.3
XS Rating Curve= 0 ,0
Exp/Cntr=0.3,0.1

Type RM Length L Ch R = 1 ,152204  ,1815,1815,1815
BEGIN DESCRIPTION:
UPPER KEECHI CREEK 36.0
END DESCRIPTION:
XS GIS Cut Line= 3
       3686402.7     10552964.28      3682236.08     10551755.96
      3678924.13     10551880.94
#Sta/Elev= 30
  1117.7  309.84  1443.7  293.95  1693.8  306.94  1939.2  299.83  2156.3  303.08
  2373.3   288.7  2453.7  273.32  2585.2  288.59    2777  285.18  2917.8  275.42
  3464.1  252.48  3641.7  249.99  3909.9  244.26  3942.6  246.01  4070.4  240.69
  4734.1  240.68  4855.8  238.37  4858.6  237.87  4861.8  238.37    5558  240.59
  5750.9  239.36 6895.76  246.48  7471.6  290.57    7674  309.23  7795.3  311.47
  7976.9  311.64    8076  311.06  8175.1  311.28  8362.1   319.3  8770.3  330.14
#Mann= 18 ,-1 , 0
  1117.7     .16       0    2777     .05       0  2917.8     .16       0
  3464.1     .05       0  3641.7     .16       0  3909.9     .12       0
  4070.4     .16       0  4734.1     .12       0  4855.8     .07       0
  4861.8     .12       0    5558     .16       0  5750.9     .05       0
  7471.6     .16       0  7795.3     .05       0  7976.9     .16       0
    8076     .12       0  8175.1     .08       0  8362.1     .05       0
Bank Sta=3942.6,6895.76
XS Rating Curve= 0 ,0
Exp/Cntr=0.3,0.1

Type RM Length L Ch R = 1 ,150389  ,3706,3706,3706
BEGIN DESCRIPTION:
UPPER KEECHI CREEK 35.0
END DESCRIPTION:
XS GIS Cut Line= 4
      3685673.57     10552089.29      3683340.25     10550505.96
      3682381.91     10550318.46      3678633.25     10551422.24
#Sta/Elev= 30
  1566.1  303.69  2259.1   288.1  2260.8  288.18  2419.5  282.49    2536  275.17
  2593.9  272.34  2652.4  266.08  3010.1  250.31  3174.2  246.21  3495.6  242.79
  3634.5   242.5  5016.2  236.65  5018.9  236.15  5022.2  236.65  5607.2  238.68
  6517.7  241.89  6833.6  246.83  6962.8  254.72  7226.4  273.49  7231.6  266.69
  7259.7  275.34    7265  266.94  7387.2  270.57  7428.9  286.57    7514  291.65
  7779.6  279.98  8137.7  273.67  8450.5  305.06  8708.2  319.43  9270.2  340.04
#Mann= 17 ,-1 , 0
  1566.1     .16       0  2259.1     .12       0  2260.8     .16       0
  2419.5     .05       0    2536     .16       0  2593.9     .05       0
  2652.4     .16       0  3010.1     .12       0  3495.6     .16       0
  3634.5     .12       0  5016.2     .07       0  5022.2     .12       0
  5607.2     .05       0  6517.7     .16       0  6962.8     .05       0
  7779.6     .16       0  8708.2     .05       0
Bank Sta=3174.2,6833.6
XS Rating Curve= 0 ,0
Exp/Cntr=0.3,0.1

Type RM Length L Ch R = 1 ,146683  ,968,968,968
BEGIN DESCRIPTION:
UPPER KEECHI CREEK 34.0
END DESCRIPTION:
XS GIS Cut Line= 3
      3685349.61     10550460.19      3682349.61     10548360.19
      3680949.64     10547360.21
#Sta/Elev= 30
  1195.4  275.42  1348.7  268.88  1596.7  267.36  1655.3  271.95  1670.1  267.77
    1751  262.12  1831.7  257.09  1949.2   255.4  2179.3  248.54  2774.8  243.89
  2865.7  242.66  3178.3   239.7  3476.9  238.28  3594.4  238.45    3784  238.76
  3924.2  238.91  4105.3  240.29  4290.2  236.55  4652.1  237.51  4829.7  238.14
  4887.3  237.79    5019  234.79  5021.8  234.29    5025  234.79  5066.3   242.9
  5365.5  243.75  5478.5  245.34  6233.7  259.85  6341.9  268.06  6577.8  298.07
#Mann= 20 ,-1 , 0
  1195.4     .16       0  1348.7     .05       0  1596.7     .16       0
    1751     .05       0  1831.7     .16       0  1949.2     .16       0
  2865.7     .12       0  3178.3     .16       0  3476.9     .05       0
  3594.4     .16       0    3784     .05       0  3924.2     .16       0
  4105.3     .16       0  4652.1     .05       0  4829.7     .12       0
  4887.3     .05       0    5019     .03       0    5025     .05       0
  5365.5     .08       0  5478.5     .05       0
Bank Sta=2774.8,5066.3
XS Rating Curve= 0 ,0
Exp/Cntr=0.3,0.1

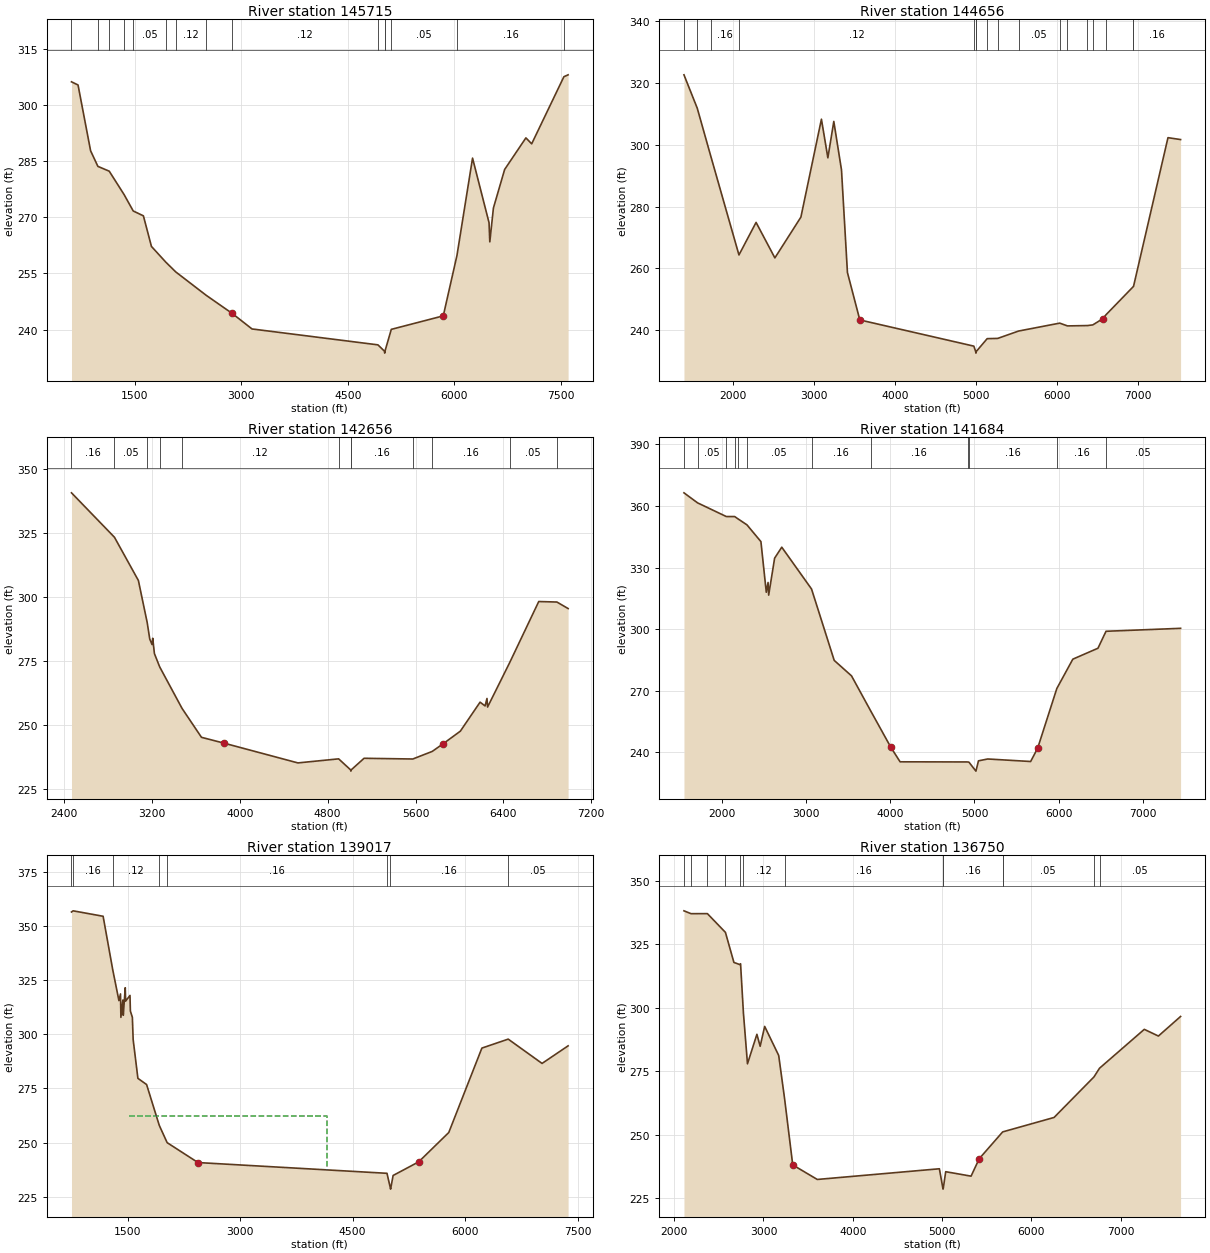
Type RM Length L Ch R = 1 ,145715  ,1059,1059,1059
BEGIN DESCRIPTION:
UPPER KEECHI CREEK 33.0
END DESCRIPTION:
XS GIS Cut Line= 3
      3685849.61     10550860.19      3682480.87     10547685.65
      3680358.45     10546656.99
#Sta/Elev= 30
   612.8  306.22   704.8  305.38   881.6  287.79   984.1  283.63  1143.6  282.34
  1350.9  276.15  1481.6   271.7  1624.5  270.41  1737.7  262.23  1937.9  258.07
  2079.2  255.43  2508.2  249.17    2873  244.34  3152.6  240.18  4924.4  235.93
  5017.1  234.22  5019.9  233.72  5023.1  234.22  5112.5  240.07  5843.8  243.68
  6036.5  259.84  6255.7  285.83  6487.6  268.58  6498.5  263.46  6549.2  272.49
  6707.2   282.8  7006.3  291.24  7087.7  289.65  7540.8  307.58  7600.2  308.09
#Mann= 15 ,-1 , 0
   612.8     .16       0   984.1     .05       0  1143.6     .16       0
  1350.9     .08       0  1481.6     .05       0  1937.9     .16       0
  2079.2     .12       0  2508.2     .16       0    2873     .12       0
  4924.4     .16       0  5017.1     .07       0  5023.1     .16       0
  5112.5     .05       0  6036.5     .16       0  7540.8     .12       0
Bank Sta=2873,5843.8
XS Rating Curve= 0 ,0
Exp/Cntr=0.3,0.1

Type RM Length L Ch R = 1 ,144656  ,2000,2000,2000
BEGIN DESCRIPTION:
UPPER KEECHI CREEK 32.0
END DESCRIPTION:
XS GIS Cut Line= 3
      3686282.96     10549430.44      3683014.72     10547425.23
       3681466.5     10545733.89
#Sta/Elev= 30
  1396.2  322.58  1560.4  311.77  1723.7  296.59  2074.6  264.34  2285.9  274.86
  2517.9  263.39  2838.9  276.57  3092.2  308.23  3171.7  295.74  3244.9  307.51
  3339.7  291.85  3413.1  258.66  3565.9  243.33    4973  234.86  4995.6   233.1
  4998.4   232.6  5001.6   233.1  5137.3  237.28  5267.7  237.36  5524.9  239.74
  6032.3   242.3  6127.7   241.4  6373.8  241.51  6440.6  241.73  6561.4  243.68
  6606.2  245.08  6939.5  254.09  6942.5  254.13    7368  302.26  7523.5  301.65
#Mann= 17 ,-1 , 0
  1396.2     .16       0  1560.4     .05       0  1723.7     .16       0
  2074.6     .12       0    4973     .16       0  4995.6     .07       0
  5001.6     .16       0  5137.3     .12       0  5267.7     .16       0
  5524.9     .05       0  6032.3     .16       0  6127.7     .12       0
  6373.8     .16       0  6440.6     .05       0  6606.2     .16       0
  6939.5     .05       0  6942.5     .16       0
Bank Sta=3565.9,6561.4
XS Rating Curve= 0 ,0
Exp/Cntr=0.3,0.1

Type RM Length L Ch R = 1 ,142656  ,972,972,972
BEGIN DESCRIPTION:
UPPER KEECHI CREEK 31.0
END DESCRIPTION:
XS GIS Cut Line= 3
      3686022.56     10547438.27      3684329.83     10546370.55
      3682052.89     10545290.62
#Sta/Elev= 30
  2467.8  340.71    2859  323.34  3076.8  306.44  3156.5  290.11  3180.3  283.56
  3201.5  281.38  3207.4  283.85  3222.7  277.87  3270.6  272.67  3474.2  256.44
  3651.1  245.13  3860.6   242.8  4529.3  235.12  4900.1  236.71  5008.7  232.41
  5011.5  231.91  5014.7  232.41  5131.5  236.93  5575.2  236.65  5751.9  239.61
  5852.9  242.66  6007.8  247.52  6187.8  258.87  6233.2  257.39  6250.5  260.31
    6256  256.96  6457.1  274.32  6721.8  298.21  6886.9  298.02  6989.2  295.47
#Mann= 12 ,-1 , 0
  2467.8     .16       0    2859     .05       0  3156.5     .12       0
  3270.6     .16       0  3474.2     .12       0  4900.1     .16       0
  5008.7     .07       0  5014.7     .16       0  5575.2     .05       0
  5751.9     .16       0  6457.1     .05       0  6886.9     .16       0
Bank Sta=3860.6,5852.9
XS Rating Curve= 0 ,0
Exp/Cntr=0.3,0.1

Type RM Length L Ch R = 1 ,141684  ,2667,2667,2667
BEGIN DESCRIPTION:
UPPER KEECHI CREEK 30.0
END DESCRIPTION:
XS GIS Cut Line= 4
      3687011.22      10546800.2      3685532.09     10545362.73
      3683761.25     10545321.07      3681886.23     10544466.89
#Sta/Elev= 30
  1552.2   366.4  1713.7  361.51  2054.9  354.84  2153.5  354.84  2187.8  353.87
  2300.1  350.78  2465.6  342.62  2529.3  317.94  2550.5  322.71  2557.6  316.54
  2628.2  334.56    2713   339.9  3066.4  319.52  3335.5  284.72  3540.5  277.21
  3767.3   260.2  4007.3   242.4  4117.4   235.3  4920.7  235.23    4935  235.11
  5017.4  230.76  5047.6  235.77  5157.7  236.68  5666.9  235.45  5750.5  241.98
  5977.5  271.01  6167.4  285.32    6466  290.66  6561.5  298.92  7446.5  300.36
#Mann= 12 ,-1 , 0
  1552.2     .16       0  1713.7     .05       0  2054.9     .08       0
  2153.5     .05       0  2187.8     .08       0  2300.1     .05       0
  3066.4     .16       0  3767.3     .16       0  4920.7     .07       0
    4935     .16       0  5977.5     .16       0  6561.5     .05       0
Bank Sta=4007.3,5750.5
XS Rating Curve= 0 ,0
Exp/Cntr=0.3,0.1

Type RM Length L Ch R = 1 ,139017  ,2267,2267,2267
BEGIN DESCRIPTION:
Mapping XS cb2f9e41
END DESCRIPTION:
XS GIS Cut Line= 3
      3688219.59      10542216.9      3684969.59     10543300.23
      3681783.38     10543550.13
#Sta/Elev= 30
   751.5  356.34   773.3  356.88  1173.1  354.37  1301.3  329.73  1383.9  315.49
    1405  318.58  1410.2  307.77  1436.6  315.77  1441.9  308.72  1468.2  321.43
  1473.5  315.27  1531.5  317.88  1536.7  310.68  1563.1   307.8  1573.7  297.55
  1636.9  279.66  1752.8  276.81  1921.5  258.02  2026.9  250.02    2438  240.85
  4958.2  235.89  5003.4   229.1  5006.2   228.6  5039.9  234.89    5381  241.17
  5782.2   254.7  6223.6  293.61  6574.6  297.74    7026  286.54  7373.3  294.65
#Mann= 8 ,-1 , 0
   751.5     .08       0   773.3     .16       0  1301.3     .12       0
  1921.5     .16       0  2026.9     .16       0  4958.2     .05       0
  5003.4     .16       0  6574.6     .05       0
#XS Ineff= 1 ,-1
 1522.73 4154.55  262.23
Permanent Ineff=
       F
Bank Sta=2438,5381
XS Rating Curve= 0 ,0
Exp/Cntr=0.3,0.1

Type RM Length L Ch R = 1 ,136750  ,2271,2271,2271
BEGIN DESCRIPTION:
Mapping XS 885258b9
END DESCRIPTION:
XS GIS Cut Line= 3
      3687511.27      10541091.9      3684240.42     10541633.57
      3682219.55     10542612.75
#Sta/Elev= 30
  2109.6  338.26  2188.2  337.14  2372.1  337.15  2573.9  329.77  2668.8  317.93
  2734.6  317.08  2743.3   317.4  2775.6  297.89  2820.8  277.98  2926.3   289.6
  2962.7  284.89  3013.4  292.71  3170.4  281.27  3236.5   264.2  3327.6  238.14
  3602.5  232.41  4969.7  236.62  5007.9   229.1  5010.6   228.6  5013.9   229.1
  5040.6  235.47  5324.5  233.71  5415.7  240.58  5678.5  251.15    6254  256.84
  6700.1  272.79  6762.7  276.23  7264.2  291.56  7422.2  288.92  7670.6  296.63
#Mann= 13 ,-1 , 0
  2109.6     .05       0  2188.2     .16       0  2372.1     .05       0
  2573.9     .12       0  2734.6     .05       0  2775.6     .12       0
  3236.5     .16       0  5007.9     .07       0  5013.9     .16       0
  5678.5     .16       0  5678.5     .05       0  6700.1     .16       0
  6762.7     .05       0
Bank Sta=3327.6,5415.7
XS Rating Curve= 0 ,0
Exp/Cntr=0.3,0.1