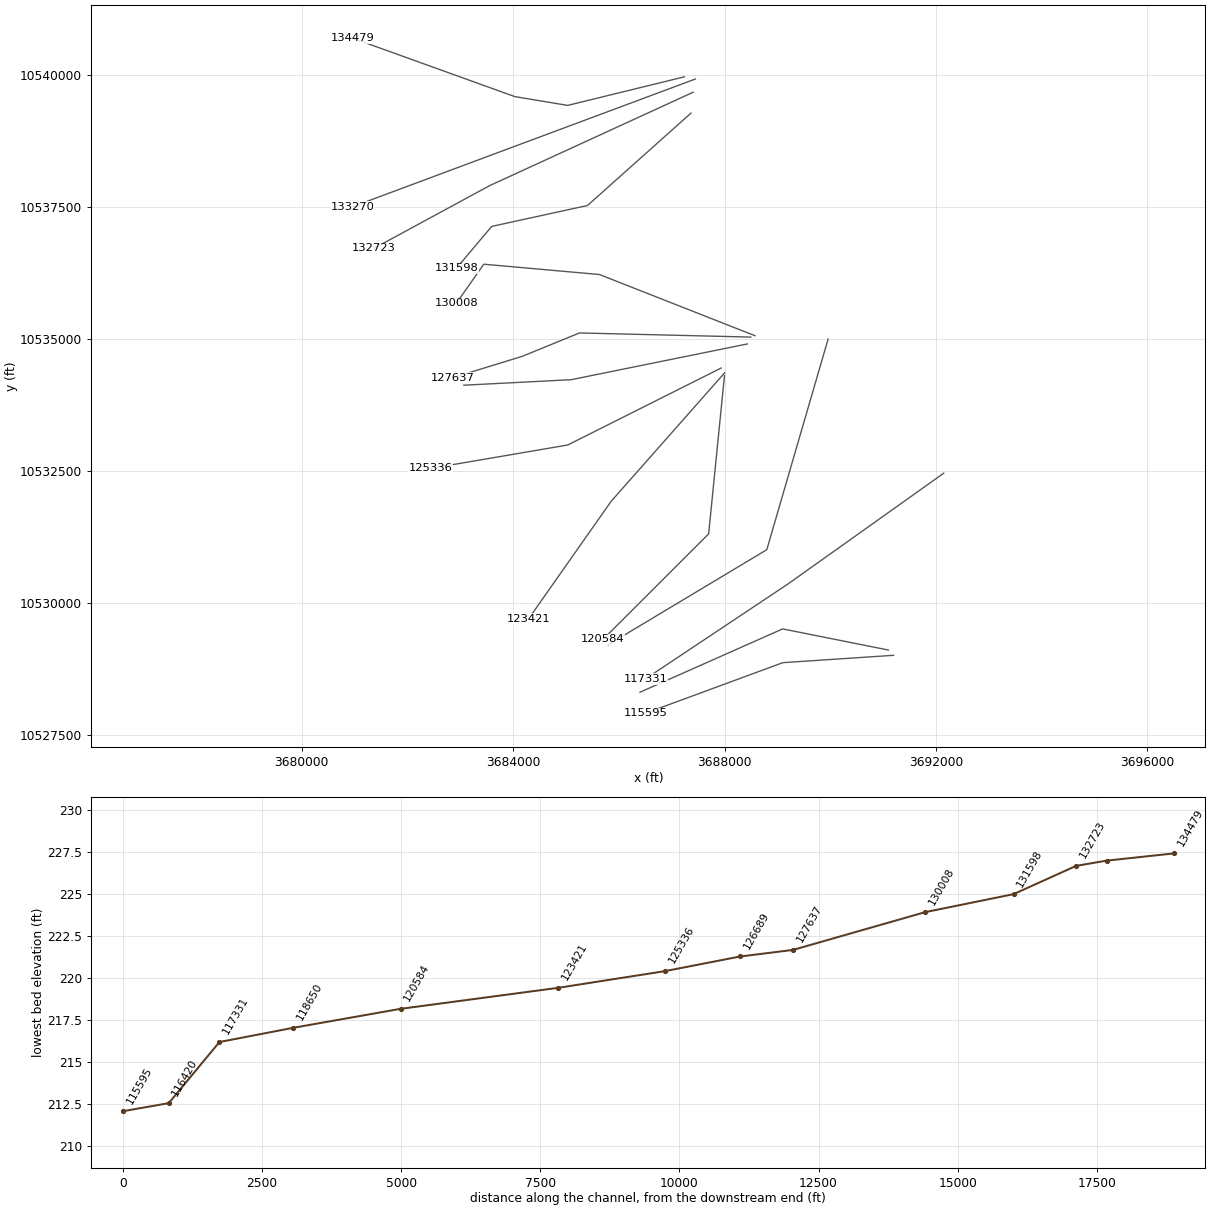
HEC-RAS study UPPER KEECHI CREEK.prj: UPPER KEECHI CREEK Base Level Engineering

--- UPPER KEECHI CREEK.g01 (geometry) --- (continued)

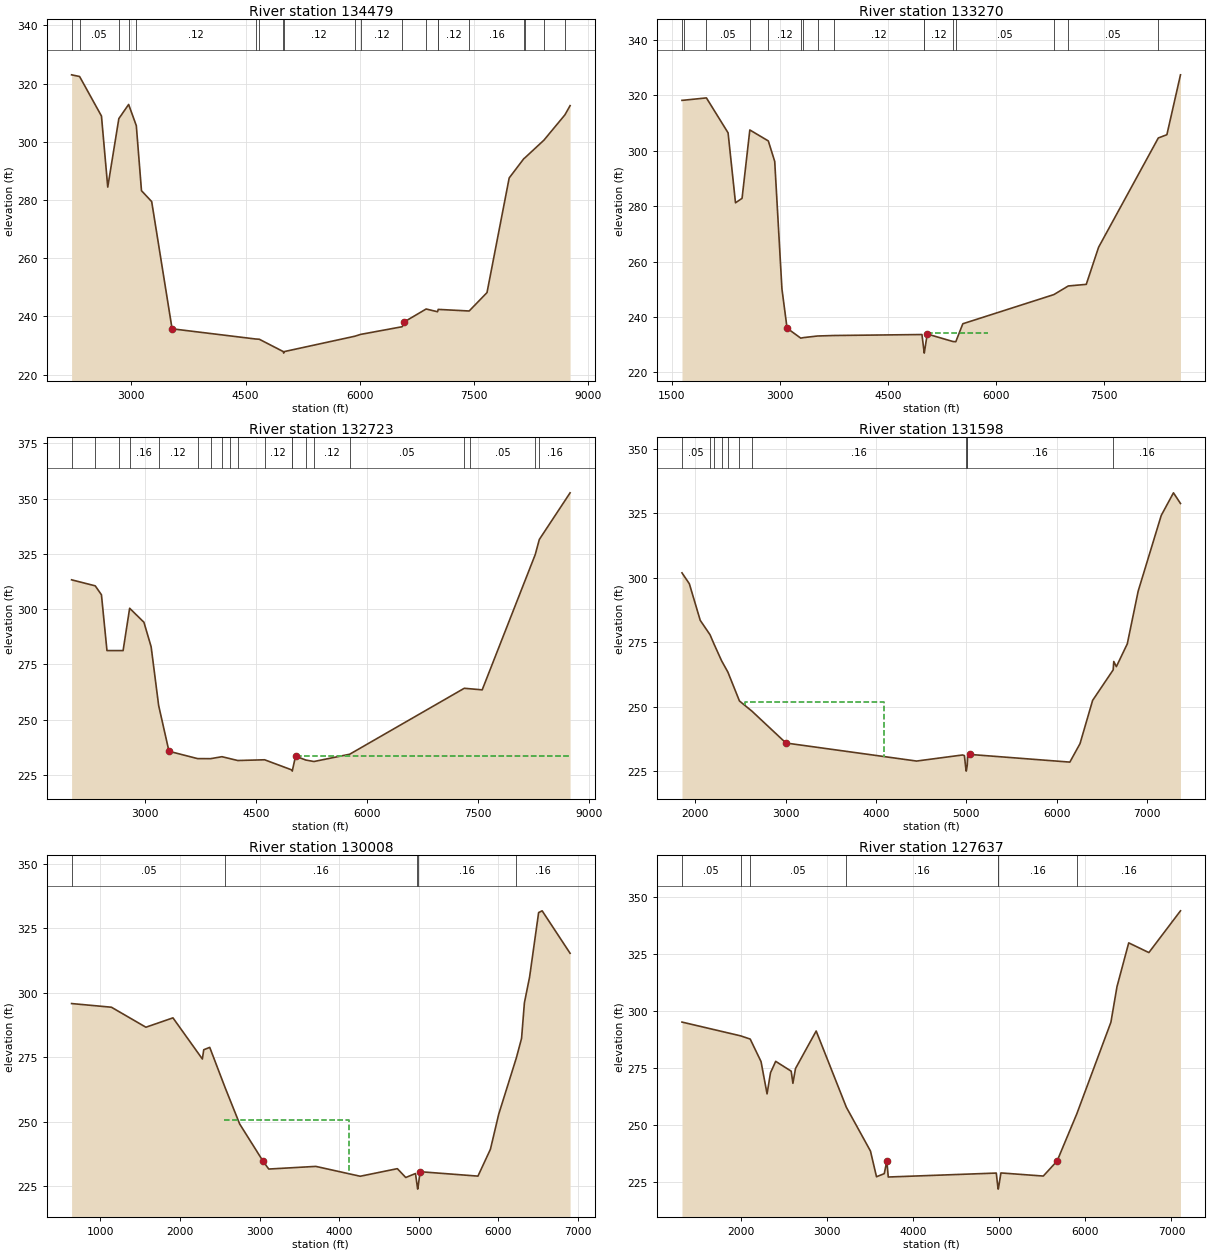
Type RM Length L Ch R = 1 ,134479  ,1209,1209,1209
BEGIN DESCRIPTION:
Mapping XS 19d933a9
END DESCRIPTION:
XS GIS Cut Line= 4
      3687240.45     10539966.91      3685032.09     10539425.23
      3684032.09      10539591.9       3680970.8     10540695.63
#Sta/Elev= 30
  2217.1  322.98  2322.3   322.4  2609.2  308.82  2691.6  284.42  2837.2  307.94
  2965.7   312.8  3066.5  305.52  3134.3  283.19  3268.2  279.44  3535.9  235.75
  4632.9  232.25  4680.3  232.17  4997.3   227.9  5000.1   227.4  5003.3   227.9
    5930  233.18  6011.3  233.84  6556.2  236.47  6581.1   238.1  6869.6  242.55
  7020.1  241.61  7028.2  242.42  7434.4  241.87  7668.6  248.19  7959.6  287.56
  8151.5  294.18    8168  294.53  8414.4  300.51  8690.3  309.21  8758.9  312.39
#Mann= 20 ,-1 , 0
  2217.1     .16       0  2322.3     .05       0  2837.2     .16       0
  2965.7     .05       0  3066.5     .12       0  4632.9     .16       0
  4680.3     .12       0  4997.3     .07       0  5003.3     .12       0
    5930     .16       0  6011.3     .12       0  6556.2     .16       0
  6869.6     .12       0  7020.1     .16       0  7028.2     .12       0
  7434.4     .16       0  8151.5     .05       0    8168     .16       0
  8414.4     .05       0  8690.3     .05       0
Bank Sta=3535.9,6581.1
XS Rating Curve= 0 ,0
Exp/Cntr=0.3,0.1

Type RM Length L Ch R = 1 ,133270  ,547,547,547
BEGIN DESCRIPTION:
Mapping XS 78895c45
END DESCRIPTION:
XS GIS Cut Line= 2
      3687448.72     10539925.22      3680969.55     10537508.55
#Sta/Elev= 30
  1644.4   318.2  1666.5  318.25  1983.4  319.09  2283.8  306.48  2386.8  281.23
  2477.8  282.84  2585.5  307.52    2842  303.56  2930.8  296.16  3030.9  250.15
  3102.1  235.97  3291.9  232.38  3328.8  232.57  3524.9  233.15  3753.3  233.33
  4973.4  233.68  5002.4  227.47  5005.2  226.97  5008.4  227.47  5046.2  233.87
    5403  231.16  5442.8  231.09  5540.2  237.57  6803.2   248.1  7003.3  251.21
  7252.5  251.79  7423.8   265.2  8251.9  304.63  8370.8   305.8  8559.6  327.42
#Mann= 16 ,-1 , 0
  1644.4     .05       0  1666.5     .16       0  1983.4     .05       0
  2585.5     .16       0    2842     .12       0  3291.9     .16       0
  3328.8     .12       0  3524.9     .16       0  3753.3     .12       0
  5002.4     .07       0  5008.4     .12       0    5403     .07       0
  5442.8     .05       0  6803.2     .12       0  7003.3     .05       0
  8251.9     .16       0
#XS Ineff= 1 ,-1
 5076.52 5894.47 234.094
Permanent Ineff=
       T
Bank Sta=3102.1,5046.2
XS Rating Curve= 0 ,0
Exp/Cntr=0.3,0.1

Type RM Length L Ch R = 1 ,132723  ,1125,1125,1125
BEGIN DESCRIPTION:
Mapping XS 48867b4c
END DESCRIPTION:
XS GIS Cut Line= 3
      3687407.11     10539675.25      3683552.92      10537904.4
       3681365.4     10536716.89
#Sta/Elev= 30
  2011.7  313.27    2331  310.54  2414.8   306.5  2489.3  281.23  2652.5  281.23
  2707.1  281.23  2795.6  300.39  2988.4  294.05  3085.8  282.95  3187.1  256.38
  3326.6  235.65  3712.3  232.33  3888.8   232.3  4042.4  233.19  4149.3  232.32
  4256.2  231.46  4617.5   231.8  4988.3  227.16  4991.1  226.66  4994.3  227.16
  5035.3  233.44  5173.9  231.68  5283.9  231.01    5766   234.3  7313.8  264.17
  7390.5  263.94  7555.5  263.45  8272.1  324.73  8326.6  331.52  8742.3  352.65
#Mann= 20 ,-1 , 0
  2011.7     .16       0    2331     .05       0  2652.5      .1       0
  2795.6     .16       0  3187.1     .12       0  3712.3     .12       0
  3888.8     .12       0  4042.4     .16       0  4149.3     .16       0
  4256.2     .05       0  4617.5     .12       0  4988.3     .07       0
  4994.3     .12       0  5173.9     .16       0  5283.9     .12       0
    5766     .05       0  7313.8      .1       0  7390.5     .05       0
  8272.1     .05       0  8326.6     .16       0
#XS Ineff= 2 , 0
       0                 5035.41       0  233.57
Permanent Ineff=
       F       T
Bank Sta=3326.6,5035.3
XS Rating Curve= 0 ,0
Exp/Cntr=0.3,0.1

Type RM Length L Ch R = 1 ,131598  ,1590,1590,1590
BEGIN DESCRIPTION:
Mapping XS de994d67
END DESCRIPTION:
XS GIS Cut Line= 4
      3687365.45     10539279.43      3685407.09      10537529.4
      3683594.59     10537133.57      3682927.89     10536341.87
#Sta/Elev= 30
  1854.4  301.93  1935.9   297.7  2056.3   283.5  2164.2  277.95    2208  274.38
  2292.4  267.83  2361.9  263.45  2490.4  252.21  2629.8  248.21  3005.1  235.89
  4450.5  228.89  4959.3  231.25  4979.7  231.01  4997.2  225.48    5000  224.98
  5003.2  225.48  5011.1  227.31  5015.8  230.57  5041.1  231.46  6146.6  228.48
  6259.2  235.65  6398.6  252.43  6626.2  264.28  6632.7  267.53  6661.3  265.53
  6782.3  274.38  6902.6  294.82  7158.1  324.23  7293.3  332.99    7371  328.86
#Mann= 11 ,-1 , 0
  1854.4     .05       0  2164.2     .16       0    2208     .05       0
  2292.4     .16       0  2361.9     .05       0  2490.4     .16       0
  2629.8     .16       0  4997.2     .07       0  5003.2     .12       0
  5011.1     .16       0  6626.2     .16       0
#XS Ineff= 1 ,-1
 2551.14 4086.36  251.63
Permanent Ineff=
       F
Bank Sta=3005.1,5041.1
XS Rating Curve= 0 ,0
Exp/Cntr=0.3,0.1

Type RM Length L Ch R = 1 ,130008  ,2371,2371,2371
BEGIN DESCRIPTION:
Mapping XS cf82646e
END DESCRIPTION:
XS GIS Cut Line= 4
      3688575.06      10535063.5      3685632.35     10536222.36
      3683444.85     10536417.67      3682924.29     10535675.88
#Sta/Elev= 30
   637.1  295.81  1137.8  294.39  1571.1  286.64  1911.2  290.27  2280.6  274.33
  2298.1  277.91  2373.3  278.84  2566.8  263.22  2749.5  249.15  3044.2   234.7
  3114.9  231.69    3706  232.72  4264.4   228.9  4731.2  231.84  4836.6  228.42
  4959.1  229.95  4984.2  224.41    4987  223.91  4990.2  224.41  5017.3  230.66
  5744.2  228.95  5900.8  239.35  6005.1  252.95  6226.9  274.78  6292.3  282.32
    6328  296.11  6393.4  306.12  6506.7  331.06  6551.1  331.74  6902.2  315.29
#Mann= 5 ,-1 , 0
   637.1     .05       0  2566.8     .16       0  4984.2     .07       0
  4990.2     .16       0  6226.9     .16       0
#XS Ineff= 1 ,-1
 2549.43 4120.45  250.72
Permanent Ineff=
       F
Bank Sta=3044.2,5017.3
XS Rating Curve= 0 ,0
Exp/Cntr=0.3,0.1

Type RM Length L Ch R = 1 ,127637  ,948,948,948
BEGIN DESCRIPTION:
Mapping XS 56a52eb4
END DESCRIPTION:
XS GIS Cut Line= 4
      3688496.92     10535037.47      3685254.74     10535115.59
      3684174.01     10534672.88      3682858.87     10534269.23
#Sta/Elev= 30
  1318.4  295.02  1998.2  288.98  2110.2  287.56    2236  277.68    2306   263.5
    2346  272.78    2406  277.78  2586.1  273.46  2606.1  268.13  2636.1  274.62
  2876.2   291.1  3226.3  257.63  3506.3  238.39  3576.4   227.1  3666.4  228.47
  3696.4  233.99    3713  226.99  4966.9  228.72  4986.3  222.17    4989  221.67
  4992.3  222.17  5020.9  228.78  5512.5  227.41  5672.6     234  5901.4  254.72
  6297.3  294.93    6368  310.57  6504.1   329.8  6738.2  325.54  7105.1  343.87
#Mann= 7 ,-1 , 0
  1318.4     .05       0  1998.2     .16       0  2110.2     .05       0
  3226.3     .16       0  4986.3     .07       0  4992.3     .16       0
  5901.4     .16       0
Bank Sta=3696.4,5672.6
XS Rating Curve= 0 ,0
Exp/Cntr=0.3,0.1

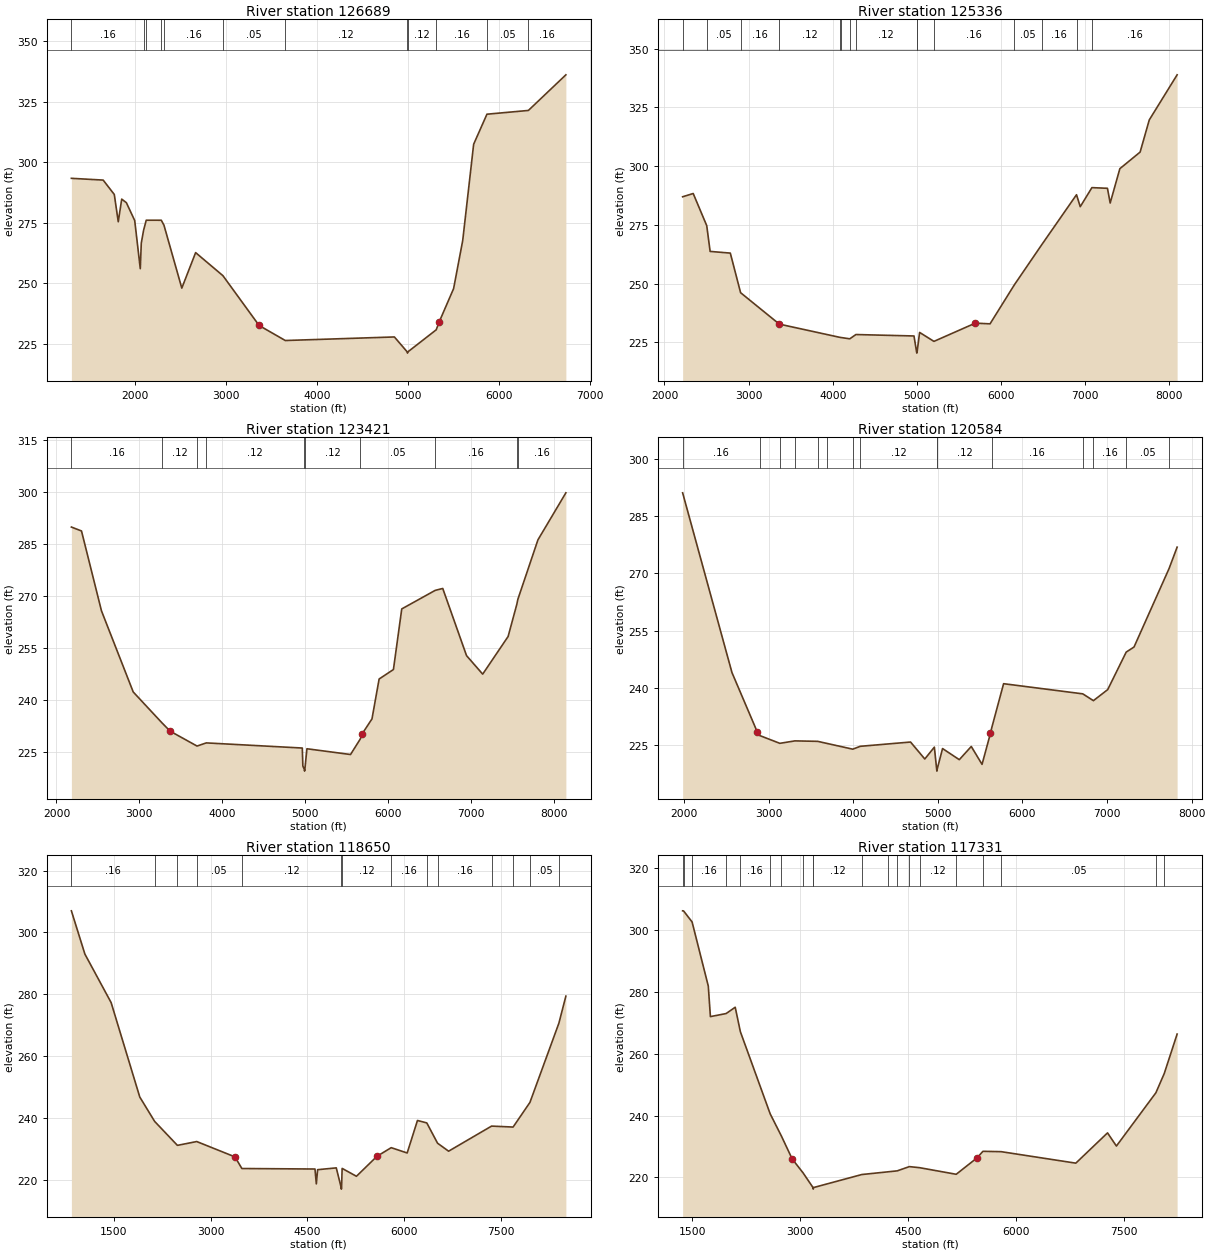
Type RM Length L Ch R = 1 ,126689  ,1353,1353,1353
BEGIN DESCRIPTION:
UPPER KEECHI CREEK 29.0
END DESCRIPTION:
XS GIS Cut Line= 3
      3688431.79     10534907.25      3685098.49     10534230.17
      3683067.23     10534126.01
#Sta/Elev= 30
  1299.8  293.37    1649  292.64  1771.4  286.71  1814.9  275.46  1853.1  284.79
  1904.1  283.33  1995.9  275.95  2057.1  256.09  2068.1  266.66  2093.8  272.02
  2122.5  276.09  2287.9  276.08  2317.3  274.05  2513.5  248.09  2665.4  262.73
  2965.7  253.21  3363.3  232.68  3651.1  226.48  4850.2  227.95  4991.6  221.78
  4994.4  221.28  4997.6  221.78    5310   230.9  5340.9  233.99  5501.1  247.89
  5601.2  267.72  5721.4  307.43  5867.5  319.81    6323  321.36  6735.1  336.05
#Mann= 12 ,-1 , 0
  1299.8     .16       0  2093.8     .12       0  2122.5     .16       0
  2287.9     .12       0  2317.3     .16       0  2965.7     .05       0
  3651.1     .12       0  4991.6     .07       0  4997.6     .12       0
    5310     .16       0  5867.5     .05       0    6323     .16       0
Bank Sta=3363.3,5340.9
XS Rating Curve= 0 ,0
Exp/Cntr=0.3,0.1

Type RM Length L Ch R = 1 ,125336  ,1915,1915,1915
BEGIN DESCRIPTION:
UPPER KEECHI CREEK 28.0
END DESCRIPTION:
XS GIS Cut Line= 3
      3687937.05     10534451.54      3685033.39      10532993.2
      3682443.43     10532550.69
#Sta/Elev= 30
    2216  286.94  2341.7  288.33  2502.5  274.65  2542.7  263.69  2782.7  262.97
  2904.9  246.12  3365.3  232.75  4083.7  227.13  4094.2  227.07  4202.8   226.5
  4275.6  228.32  4965.5  227.71  4996.5  220.91  4999.3  220.41  5002.5  220.91
  5032.5  229.22  5202.7  225.41  5694.2  233.17  5869.5  232.87  6158.7  249.49
  6484.1  266.55    6897  287.81  6941.6  282.72  7080.1  290.83  7264.8  290.55
  7297.2  284.28  7412.4   298.9  7652.9  305.95  7761.9  319.64  8092.8  338.83
#Mann= 15 ,-1 , 0
    2216     .16       0  2502.5     .05       0  2904.9     .16       0
  3365.3     .12       0  4083.7     .05       0  4094.2     .08       0
  4202.8     .05       0  4275.6     .12       0  4996.5     .07       0
  5002.5     .12       0  5202.7     .16       0  6158.7     .05       0
  6484.1     .16       0    6897     .05       0  7080.1     .16       0
Bank Sta=3365.3,5694.2
XS Rating Curve= 0 ,0
Exp/Cntr=0.3,0.1

Type RM Length L Ch R = 1 ,123421  ,2837,2837,2837
BEGIN DESCRIPTION:
UPPER KEECHI CREEK 27.0
END DESCRIPTION:
XS GIS Cut Line= 3
      3688002.12     10534360.36       3685853.7     10531925.49
      3684291.21     10529698.93
#Sta/Elev= 30
  2180.2  289.81  2302.2  288.68  2543.2  265.65  2926.4  242.25  3271.9  233.38
 3372.16  230.94  3696.5  226.65  3808.1  227.56  4966.8  226.08  4973.5  220.89
  4991.4  219.92  4994.1  219.42  4997.4  219.92  5022.8  225.87  5548.8  224.21
  5665.8  228.66  5691.7  230.26  5807.6  234.48  5893.9  245.99  6066.5  248.72
  6166.9   266.2  6570.7  271.55  6661.7   272.1  6948.7  252.73  7143.7  247.39
  7450.5  258.25  7555.4  267.51  7568.2  268.98  7810.4  286.12  8147.5  299.68
#Mann= 10 ,-1 , 0
  2180.2     .16       0  3271.9     .12       0  3696.5     .05       0
  3808.1     .12       0  4991.4     .07       0  4997.4     .12       0
  5665.8     .05       0  6570.7     .16       0  7555.4     .12       0
  7568.2     .16       0
Bank Sta=3372.16,5691.7
XS Rating Curve= 0 ,0
Exp/Cntr=0.3,0.1

Type RM Length L Ch R = 1 ,120584  ,1934,1934,1934
BEGIN DESCRIPTION:
UPPER KEECHI CREEK 26.0
END DESCRIPTION:
XS GIS Cut Line= 3
      3687999.61     10534310.16      3687699.61     10531310.19
      3685699.58     10529310.16
#Sta/Elev= 30
    1985  291.06  2567.9  243.99  2869.4  228.31  2894.8   227.5  3133.5  225.45
  3312.2  226.09  3580.9  225.97  3693.7  225.41  3995.4  223.92  4084.2  224.67
  4678.3  225.79  4846.7  221.35  4959.7  224.45  4986.9  218.67  4989.6  218.17
  4992.9  218.67  5056.5  224.08  5254.5  221.17  5395.9  224.63  5523.2  219.94
  5622.2  228.04  5637.1  229.47  5777.8  241.07  6713.3  238.41  6839.2  236.63
  7008.1  239.52  7226.6  249.34  7319.2  250.68  7732.8   271.2  7828.4  276.83
#Mann= 15 ,-1 , 0
    1985     .16       0  2894.8     .12       0  3133.5     .05       0
  3312.2     .12       0  3580.9     .05       0  3693.7     .12       0
  3995.4     .05       0  4084.2     .12       0  4986.9     .07       0
  4992.9     .12       0  5637.1     .16       0  6713.3     .12       0
  6839.2     .16       0  7226.6     .05       0  7732.8     .16       0
Bank Sta=2869.4,5622.2
XS Rating Curve= 0 ,0
Exp/Cntr=0.3,0.1

Type RM Length L Ch R = 1 ,118650  ,1319,1319,1319
BEGIN DESCRIPTION:
UPPER KEECHI CREEK 25.0
END DESCRIPTION:
XS GIS Cut Line= 3
      3689960.47       10535001.      3688799.61     10531010.19
       3685799.6     10529210.18
#Sta/Elev= 30
   845.5  306.98  1054.6     293  1460.8  277.32  1904.1  246.81  2134.6  238.92
  2486.8  231.18  2785.4  232.42  3377.5  227.46  3484.8   223.7  4616.4  223.54
  4637.2  218.74  4657.2  223.32  4946.2  223.91    5022  217.54  5024.8  217.04
    5028  217.54  5036.7  223.74  5258.3  221.19    5577  227.67  5796.7  230.44
  6043.5  228.72  6202.9  239.23  6347.4  238.44  6513.6  231.89  6684.9   229.3
  7349.9  237.41  7683.2   237.1  7943.8  245.06  8392.2  270.67  8500.3  279.41
#Mann= 14 ,-1 , 0
   845.5     .16       0  2134.6     .12       0  2486.8     .16       0
  2785.4     .05       0  3484.8     .12       0    5022     .07       0
    5028     .12       0  5796.7     .16       0  6347.4     .05       0
  6513.6     .16       0  7349.9     .12       0  7683.2     .16       0
  7943.8     .05       0  8392.2     .16       0
Bank Sta=3377.5,5577
XS Rating Curve= 0 ,0
Exp/Cntr=0.3,0.1

Type RM Length L Ch R = 1 ,117331  ,911,911,911
BEGIN DESCRIPTION:
UPPER KEECHI CREEK 24.0
END DESCRIPTION:
XS GIS Cut Line= 3
      3692147.99     10532459.35      3689199.61     10530360.19
      3686499.62     10528560.19
#Sta/Elev= 30
    1369   306.2  1382.2  306.17  1500.3   302.6  1725.1  281.87  1754.6  271.99
  1972.8  272.98  2098.9  275.02  2170.4  267.12  2584.3  240.55  2739.2  233.41
 2889.69  225.96  3040.2  221.48  3179.1   216.7  3181.9   216.2  3185.1   216.7
  3856.1  220.92    4217  221.79  4348.1  222.11  4516.1  223.48  4659.4  223.13
  5166.8     221 5455.81  226.31  5537.8  228.43  5792.1  228.31  6827.1   224.6
  7267.3  234.39  7390.5  230.13  7938.8  247.37  8054.7  253.59  8233.3  266.34
#Mann= 20 ,-1 , 0
    1369     .08       0  1382.2     .05       0  1500.3     .16       0
  1972.8     .05       0  2170.4     .16       0  2584.3     .05       0
  2739.2     .16       0  3040.2     .12       0  3179.1     .07       0
  3185.1     .12       0  3856.1     .05       0    4217     .07       0
  4348.1     .12       0  4516.1     .07       0  4659.4     .12       0
  5166.8     .05       0  5537.8      .1       0  5792.1     .05       0
  7938.8     .08       0  8054.7     .05       0
Bank Sta=2889.69,5455.81
XS Rating Curve= 0 ,0
Exp/Cntr=0.3,0.1

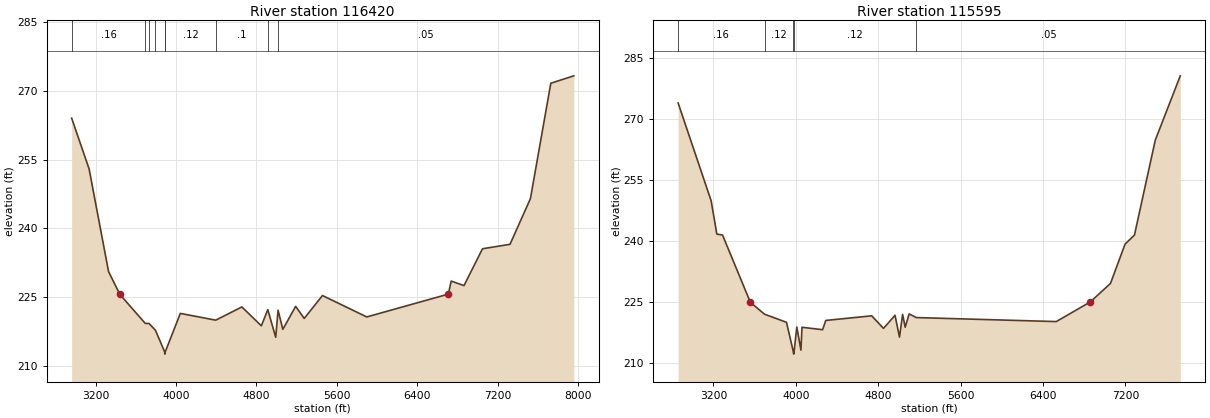
Type RM Length L Ch R = 1 ,116420  ,825,825,825
BEGIN DESCRIPTION:
UPPER KEECHI CREEK 23.0
END DESCRIPTION:
XS GIS Cut Line= 3
      3691099.56      10529110.2      3689099.61     10529510.19
      3686399.63      10528310.2
#Sta/Elev= 30
  2962.2  264.04  3135.5  252.99  3329.3  230.58  3441.5   225.6  3694.4  219.27
  3731.2  219.26  3795.1  217.79  3887.2  213.07  3889.9  212.57  3893.2  213.07
  4043.1  221.45  4395.2  219.98    4655  222.86  4848.8  218.74  4912.9  222.28
  4991.6  216.24  5015.1  222.14  5062.6  217.98  5189.8  222.99  5275.3  220.36
  5456.6  225.35  5897.1  220.68  6708.2  225.66  6736.9   228.5  6864.2  227.52
  7048.1  235.55  7321.7  236.52  7524.8  246.49  7727.3  271.65  7956.4  273.27
#Mann= 9 ,-1 , 0
  2962.2     .16       0  3694.4     .12       0  3731.2     .05       0
  3795.1     .12       0  3887.2     .07       0  3893.2     .12       0
  4395.2      .1       0  4912.9     .12       0  5015.1     .05       0
Bank Sta=3441.5,6708.2
XS Rating Curve= 0 ,0
Exp/Cntr=0.3,0.1

Type RM Length L Ch R = 1 ,115595  ,1224,1224,1224
BEGIN DESCRIPTION:
UPPER KEECHI CREEK 22.0
END DESCRIPTION:
XS GIS Cut Line= 3
      3691199.66     10529010.19      3689102.31     10528870.45
       3686499.6     10527910.19
#Sta/Elev= 30
    2857  273.98  3177.8  249.87    3233  241.67    3288  241.45  3558.6  224.86
    3696  221.93  3909.4  219.93  3976.5  212.59  3979.3  212.09  3982.5  212.59
  4009.6  218.76  4049.7  213.08  4059.7  218.71  4260.2  218.11  4290.6  220.39
  4736.8  221.53  4851.5  218.44  4963.1  221.66  5006.5  216.29  5036.9  221.88
    5062  218.72  5100.4     222  5170.3   221.1  6528.7  220.11  6859.2  224.95
  7055.3  229.51  7196.8   239.2  7288.1  241.43  7490.5  264.85  7733.2  280.67
#Mann= 5 ,-1 , 0
    2857     .16       0    3696     .12       0  3976.5     .07       0
  3982.5     .12       0  5170.3     .05       0
Bank Sta=3558.6,6859.2
XS Rating Curve= 0 ,0
Exp/Cntr=0.3,0.1