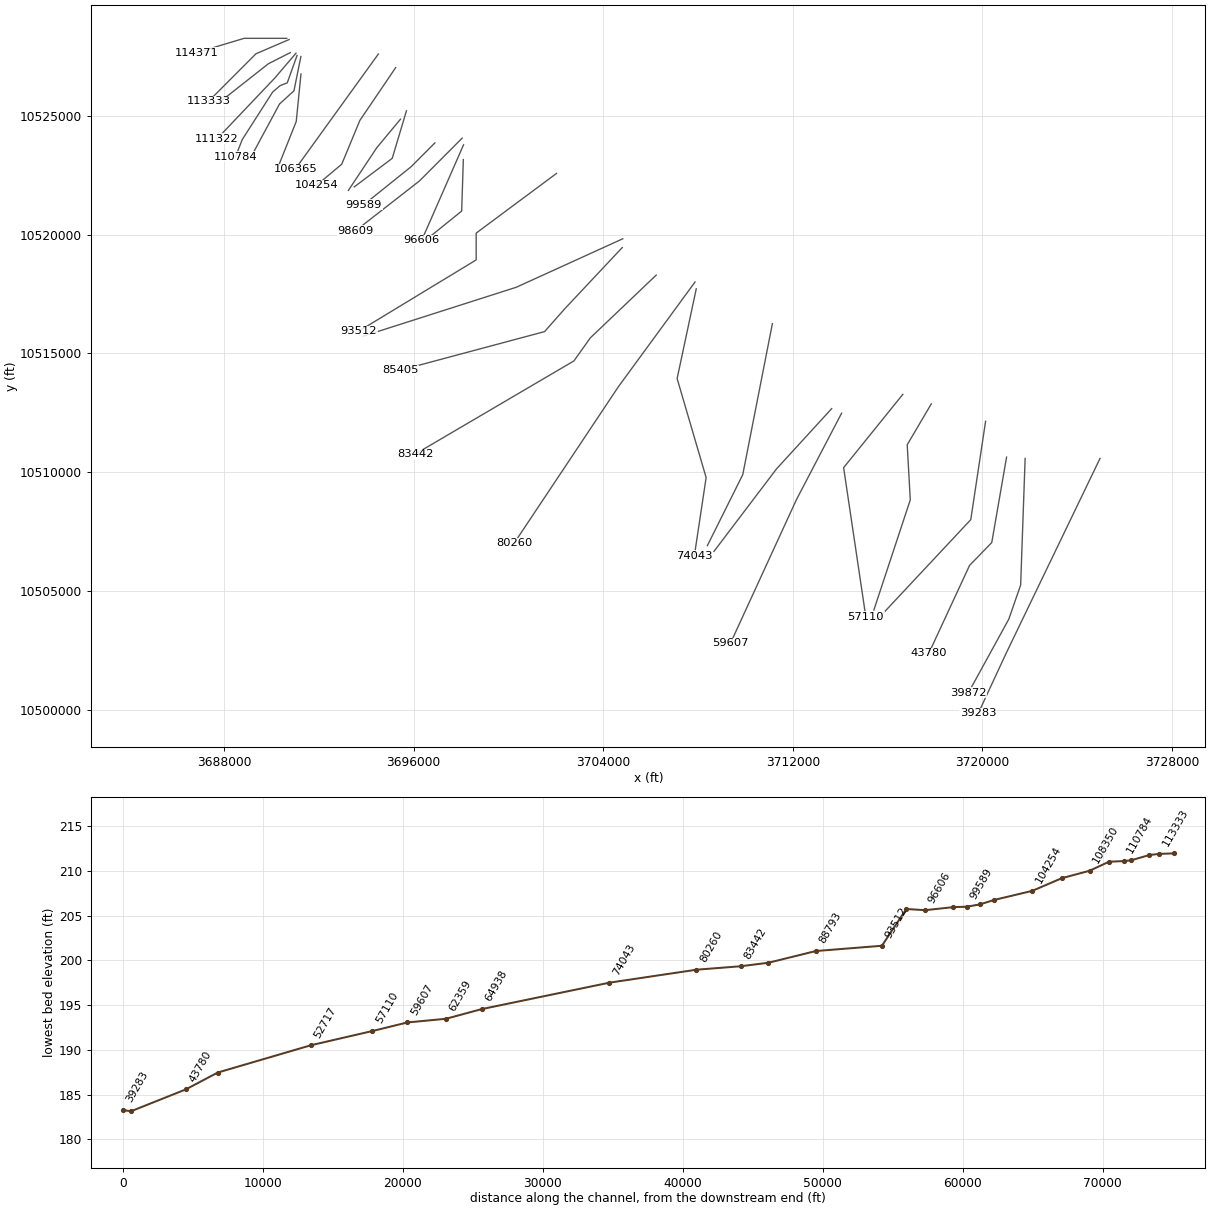
HEC-RAS study UPPER KEECHI CREEK.prj: UPPER KEECHI CREEK Base Level Engineering

--- UPPER KEECHI CREEK.g01 (geometry) --- (continued)

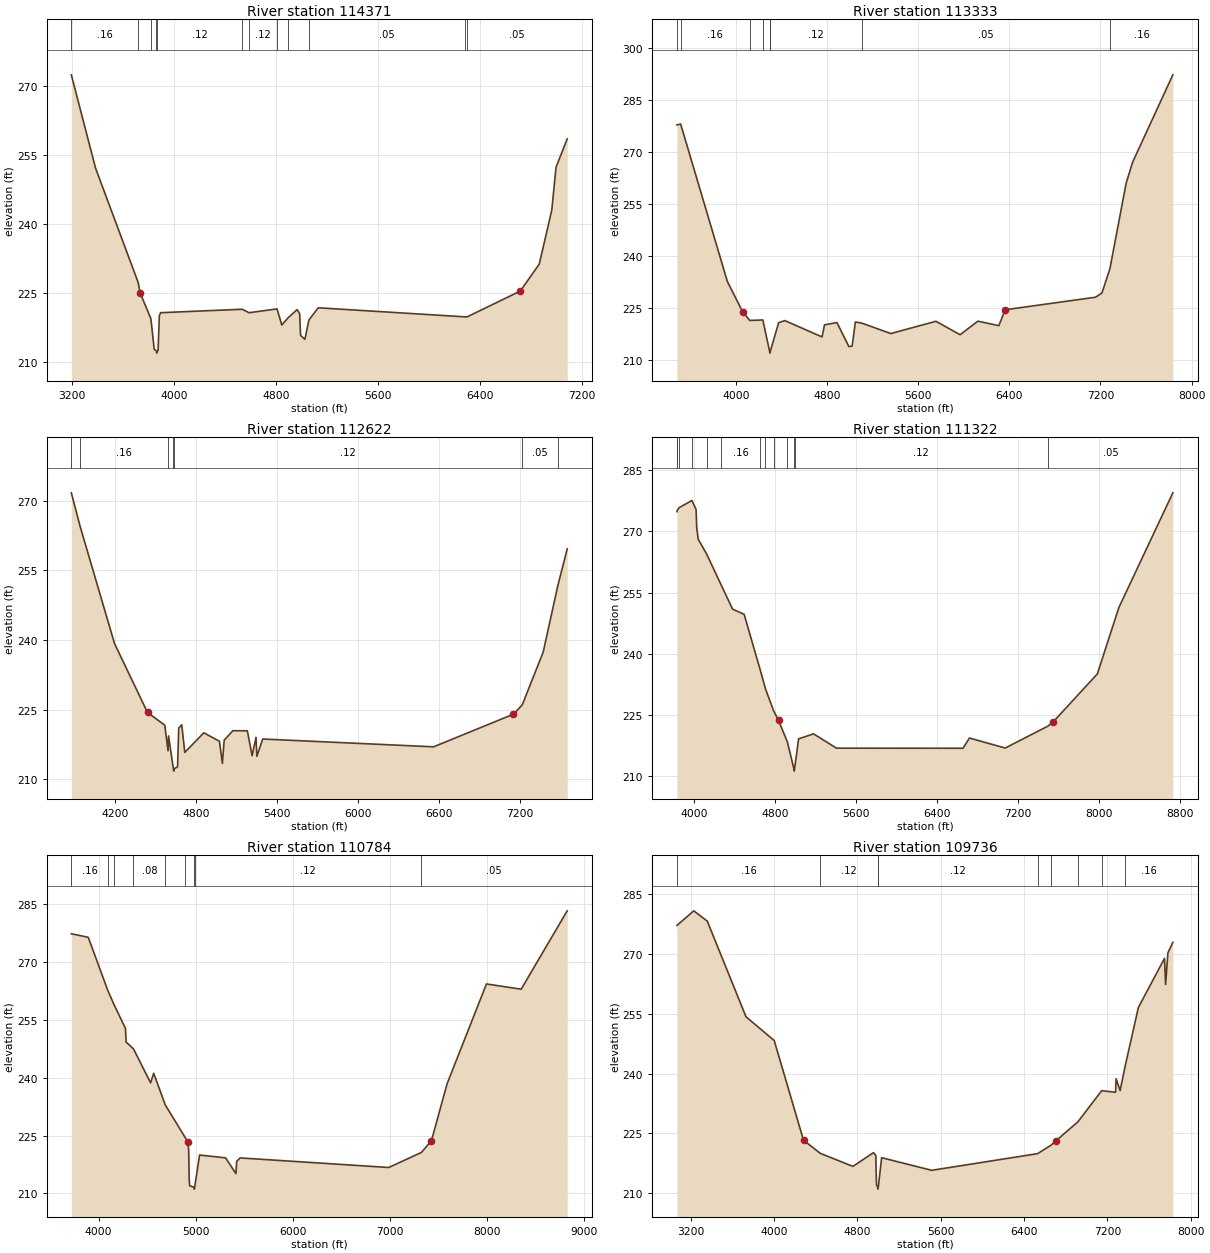
Type RM Length L Ch R = 1 ,114371  ,1038,1038,1038
BEGIN DESCRIPTION:
UPPER KEECHI CREEK 21.0
END DESCRIPTION:
XS GIS Cut Line= 3
      3690649.59     10528260.19      3688849.61     10528260.19
      3686849.65      10527660.2
#Sta/Elev= 30
  3194.6  272.49  3384.6  252.19  3718.9  227.32  3734.6  225.03  3818.3  219.47
  3844.6  212.79  3861.6  212.47  3864.3  211.97  3867.6  212.47  3874.6  212.53
  3884.6  220.07  3894.6  220.76  4532.8  221.51  4589.1  220.76  4807.5  221.59
  4844.6   218.1  4896.4  219.72  4964.6  221.42  4984.6  220.57  4992.1  215.82
  5025.9  214.97  5057.3  219.16  5130.3  221.83  6281.2  219.86  6294.8  219.82
  6714.6  225.46  6863.4  231.33  6961.7  243.09  6994.8  252.38  7082.6  258.57
#Mann= 12 ,-1 , 0
  3194.6     .16       0  3718.9     .05       0  3818.3     .12       0
  3861.6     .07       0  3867.6     .12       0  4532.8     .07       0
  4589.1     .12       0  4807.5     .05       0  4896.4     .12       0
  5057.3     .05       0  6281.2     .07       0  6294.8     .05       0
Bank Sta=3734.6,6714.6
XS Rating Curve= 0 ,0
Exp/Cntr=0.3,0.1

Type RM Length L Ch R = 1 ,113333  ,711,711,711
BEGIN DESCRIPTION:
UPPER KEECHI CREEK 20.0
END DESCRIPTION:
XS GIS Cut Line= 3
      3690749.63      10528210.2      3689349.61     10527610.19
      3687349.61     10525610.19
#Sta/Elev= 30
  3483.5  277.77  3515.7  278.04    3926  232.57  4060.1  223.84  4122.4  221.35
  4237.1  221.49  4296.5  212.42  4299.2  211.92  4302.5  212.42  4375.7  220.71
  4430.1  221.31  4756.4   216.6  4778.2  220.07    4887  220.75  4992.2  213.81
  5020.8  213.96  5049.1  220.92  5106.9  220.56  5360.2  217.57  5756.2  221.11
  5968.3  217.23  6123.9  221.14  6307.8  219.85  6364.3  224.44  7156.3  228.05
  7212.8  229.26  7282.9   236.3    7425  260.92  7481.5  266.98  7835.1  292.23
#Mann= 8 ,-1 , 0
  3483.5     .05       0  3515.7     .16       0  4122.4     .05       0
  4237.1     .12       0  4296.5     .07       0  4302.5     .12       0
  5106.9     .05       0  7282.9     .16       0
Bank Sta=4060.1,6364.3
XS Rating Curve= 0 ,0
Exp/Cntr=0.3,0.1

Type RM Length L Ch R = 1 ,112622  ,1300,1300,1300
BEGIN DESCRIPTION:
UPPER KEECHI CREEK 19.0
END DESCRIPTION:
XS GIS Cut Line= 3
      3690799.62     10527660.19      3689873.14      10527189.9
      3687799.64     10525560.21
#Sta/Elev= 30
  3873.6  271.69  3938.2  264.52  4193.6  239.27  4438.5  224.41  4566.4  221.68
  4590.7  216.16  4594.3  219.38  4630.2  212.29    4633  211.79  4636.2  212.29
  4661.1  212.72  4669.9  221.07  4692.3  221.76  4714.7  215.82  4855.8  220.04
  4971.6  218.22  4993.4  213.47  5006.8  218.44    5071  220.49  5178.5  220.47
  5213.8   215.1  5242.7  219.06    5249  214.98  5292.4   218.7  6559.5  217.02
  7151.4  224.05  7216.5  226.05  7371.9  237.42  7480.3  251.73  7549.9  259.62
#Mann= 7 ,-1 , 0
  3873.6     .05       0  3938.2     .16       0  4590.7     .12       0
  4630.2     .07       0  4636.2     .12       0  7216.5     .05       0
  7480.3     .16       0
Bank Sta=4438.5,7151.4
XS Rating Curve= 0 ,0
Exp/Cntr=0.3,0.1

Type RM Length L Ch R = 1 ,111322  ,538,538,538
BEGIN DESCRIPTION:
Mapping XS b79fc7a9
END DESCRIPTION:
XS GIS Cut Line= 3
      3691040.24     10527636.07      3690139.64     10526583.56
      3687709.81     10524034.41
#Sta/Elev= 30
  3826.7  274.84  3829.4  275.11  3848.4  275.83  3974.9  277.57    4016  275.34
  4022.6  270.79  4036.9  268.09  4120.3  264.45  4265.8  256.76  4377.2  250.93
  4491.3  249.65  4649.7   236.1  4702.3  231.39  4783.3  225.99  4831.6  223.65
  4919.1  218.37  4984.5   211.7  4987.2   211.2  4990.5   211.7  5030.3  219.12
  5178.5  220.34  5405.4  216.83  6657.2  216.81    6721  219.32  7074.5  216.86
  7496.7  222.23  7548.6  223.25    7987  235.06  8199.3  251.32  8733.6  279.45
#Mann= 13 ,-1 , 0
  3826.7     .16       0  3829.4     .05       0  3848.4     .16       0
  3974.9     .08       0  4120.3     .05       0  4265.8     .16       0
  4649.7     .05       0  4702.3     .16       0  4783.3     .05       0
  4919.1     .12       0  4984.5     .07       0  4990.5     .12       0
  7496.7     .05       0
Bank Sta=4831.6,7548.6
XS Rating Curve= 0 ,0
Exp/Cntr=0.3,0.1

Type RM Length L Ch R = 1 ,110784  ,1048,1048,1048
BEGIN DESCRIPTION:
UPPER KEECHI CREEK 18.0
END DESCRIPTION:
XS GIS Cut Line= 6
      3691083.66     10527538.45      3690671.32     10526388.25
       3690367.5     10526268.89      3690052.83     10525997.62
      3688772.45     10524001.09      3688490.36     10523285.03
#Sta/Elev= 30
  3719.2  277.31  3893.4   276.4  4094.5  262.63  4157.9  258.99  4277.2  252.73
  4282.6  249.26  4358.9  247.47  4535.3  238.66  4567.2  241.15  4686.3  232.95
  4887.7  224.65  4917.8  223.36  4927.2  221.32  4932.5  213.71  4937.4  211.97
  4982.9  211.61  4985.6  211.11  4988.9  211.61  5039.6  219.95  5307.4  219.22
  5413.8  215.14  5421.4  218.31  5456.6   219.2  6986.7  216.72  7323.1  220.62
  7426.6  223.65  7587.1  238.38  7992.9   264.3  8350.2  262.94  8824.4  283.26
#Mann= 9 ,-1 , 0
  3719.2     .16       0  4094.5     .08       0  4157.9     .05       0
  4358.9     .08       0  4686.3     .05       0  4887.7     .12       0
  4982.9     .07       0  4988.9     .12       0  7323.1     .05       0
Bank Sta=4917.8,7426.6
XS Rating Curve= 0 ,0
Exp/Cntr=0.3,0.1

Type RM Length L Ch R = 1 ,109736  ,1386,1386,1386
BEGIN DESCRIPTION:
UPPER KEECHI CREEK 17.0
END DESCRIPTION:
XS GIS Cut Line= 4
       3691246.4     10527494.99      3690953.44     10526051.88
       3690345.8     10525498.49      3689174.28     10523329.01
#Sta/Elev= 30
  3068.1  277.23  3229.5  280.88  3358.7  278.31  3730.9  254.29  4001.6  248.33
  4282.8  223.31  4444.7  220.01    4757  216.75    4955   220.2  4976.6  219.49
  4983.3  212.17  4994.5  211.54  4997.3  211.04  5000.5  211.54  5032.8  218.93
  5513.2  215.76  6529.6  219.94  6659.9  222.09  6701.6  223.07  6916.9  227.94
  7144.7  235.74  7277.9  235.35  7283.6  238.73  7321.7  235.78  7372.5  242.17
  7497.2  256.63  7748.1  268.95  7758.6   262.4  7780.5  270.33  7828.1  272.97
#Mann= 9 ,-1 , 0
  3068.1     .16       0  4444.7     .12       0  4994.5     .07       0
  5000.5     .12       0  6529.6     .05       0  6659.9     .12       0
  6916.9     .16       0  7144.7     .12       0  7372.5     .16       0
Bank Sta=4282.8,6701.6
XS Rating Curve= 0 ,0
Exp/Cntr=0.3,0.1

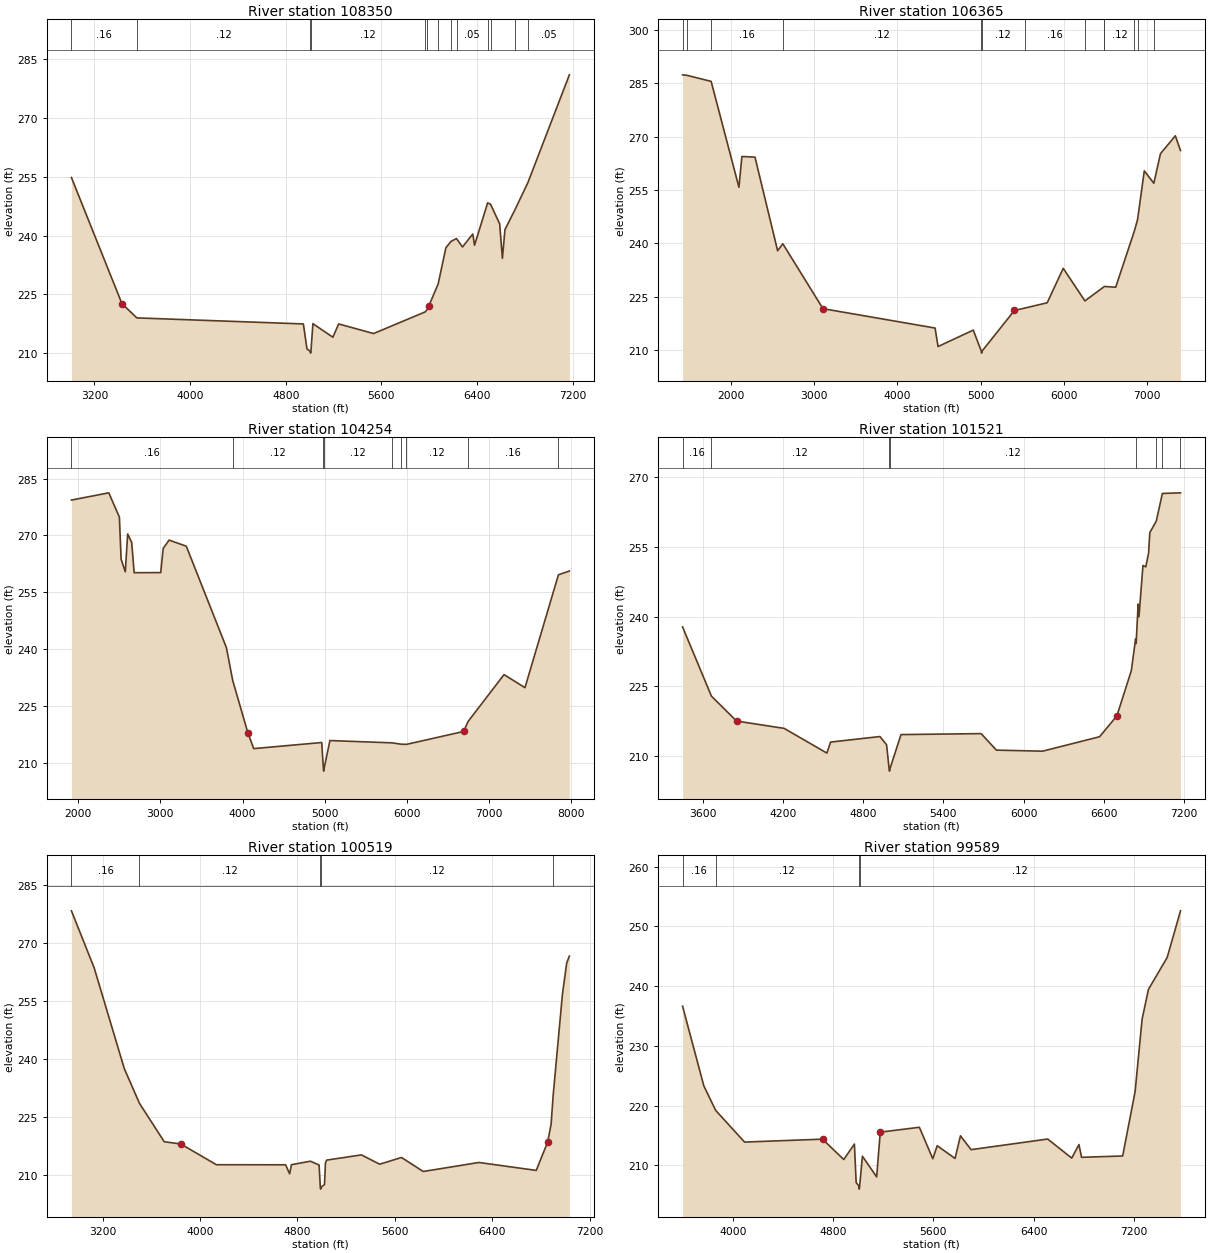
Type RM Length L Ch R = 1 ,108350  ,1985,1985,1985
BEGIN DESCRIPTION:
UPPER KEECHI CREEK 16.0
END DESCRIPTION:
XS GIS Cut Line= 3
      3691249.61     10526760.17      3691049.61     10524760.19
      3690249.62     10522760.21
#Sta/Elev= 30
    3008  254.78  3430.1  222.66    3555  219.01  4947.6  217.47  4977.8  211.09
  5004.9  210.53  5007.7  210.03  5010.9  210.53  5027.4  217.54  5194.3  214.08
  5242.8  217.47  5534.9  215.02  5967.4  220.55  5985.4  221.28  5996.7  222.05
  6074.7  227.65  6139.4  236.89    6182   238.5  6228.1  239.24  6278.1  237.09
  6364.2  240.39  6379.1  237.53  6488.5  248.33  6513.4  247.95  6589.1  242.97
    6612  234.19  6633.5  241.52  6718.7  246.68    6826  253.55    7172  280.96
#Mann= 13 ,-1 , 0
    3008     .16       0    3555     .12       0  5004.9     .07       0
  5010.9     .12       0  5967.4     .16       0  5985.4     .07       0
  6074.7     .12       0    6182     .16       0  6228.1     .05       0
  6488.5     .16       0  6513.4     .12       0  6718.7     .16       0
    6826     .05       0
Bank Sta=3430.1,5996.7
XS Rating Curve= 0 ,0
Exp/Cntr=0.3,0.1

Type RM Length L Ch R = 1 ,106365  ,2111,2111,2111
BEGIN DESCRIPTION:
Mapping XS edba4047
END DESCRIPTION:
XS GIS Cut Line= 2
      3694514.62     10527599.15      3691007.68     10522755.42
#Sta/Elev= 30
  1419.9  287.31  1471.4  287.18  1762.9  285.47  2096.7  255.76  2132.3  264.39
  2289.3  264.21  2561.5  237.93  2623.5   239.9  3105.9  221.68  4452.3  216.24
  4487.9  211.04  4910.9  215.66  5008.3   209.7    5011   209.2  5014.3   209.7
  5405.1  221.17  5528.8  221.84  5798.7  223.33  5991.3     233  6251.7  223.86
  6477.2  227.75  6486.2  227.91  6621.6   227.7  6845.4  243.46    6884  246.66
  6964.9  260.35  7079.4  256.88  7159.4  265.19  7337.7  270.19  7399.9  266.08
#Mann= 13 ,-1 , 0
  1419.9     .16       0  1471.4      .1       0  1762.9     .16       0
  2623.5     .12       0  5008.3     .07       0  5014.3     .12       0
  5528.8     .16       0  6251.7     .12       0  6477.2     .16       0
  6486.2     .12       0  6845.4     .16       0    6884     .07       0
  7079.4     .05       0
Bank Sta=3105.9,5405.1
XS Rating Curve= 0 ,0
Exp/Cntr=0.3,0.1

Type RM Length L Ch R = 1 ,104254  ,2733,2733,2733
BEGIN DESCRIPTION:
Mapping XS a810e56b
END DESCRIPTION:
XS GIS Cut Line= 4
      3695243.78     10527026.23      3693733.39     10524804.05
       3692969.5     10522963.77      3691910.48     10522078.36
#Sta/Elev= 30
  1917.5  279.31  2372.2  281.22  2501.1   274.8  2522.1  263.71    2573  260.38
  2601.9  270.37  2650.9  268.11  2680.7  260.14  3004.1  260.17    3034  266.55
  3105.8  268.75  3315.3  267.13  3803.3  240.38  3880.3  231.69  4063.7  217.96
  4135.6  213.72  4963.4  215.33  4984.3  208.28    4987  207.78  4990.3  208.28
  5063.3  215.85  5818.5  215.24    5925   214.9  5994.8  214.84  6691.4  218.25
  6744.5  220.87    7182  233.25    7437   229.8  7844.2  259.59  7977.3  260.58
#Mann= 9 ,-1 , 0
  1917.5     .16       0  3880.3     .12       0  4984.3     .07       0
  4990.3     .12       0  5818.5     .16       0    5925     .05       0
  5994.8     .12       0  6744.5     .16       0  7844.2     .05       0
Bank Sta=4063.7,6691.4
XS Rating Curve= 0 ,0
Exp/Cntr=0.3,0.1

Type RM Length L Ch R = 1 ,101521  ,1002,1002,1002
BEGIN DESCRIPTION:
UPPER KEECHI CREEK 15.0
END DESCRIPTION:
XS GIS Cut Line= 3
      3695449.58     10524860.15      3694449.61     10523660.19
      3693249.63     10521860.22
#Sta/Elev= 30
  3449.2  237.78  3664.8   222.9  3853.3  217.53  4208.7  215.96  4528.9  210.64
  4556.3  213.01  4925.9   214.2  4975.4  212.43  4994.5  207.26  4997.3  206.76
  5000.5  207.26  5083.3  214.62  5682.7  214.83  5796.9  211.28  6142.4  211.05
  6569.1  214.16  6698.3  218.64  6806.5  228.38  6838.4   235.2  6842.5   234.2
  6857.5  242.71  6863.6  239.96  6893.6     251  6914.6   250.7  6935.7  253.69
  6944.7  258.05  6993.5  260.58  7038.7  266.49  7171.4  266.63  7174.5  266.63
#Mann= 8 ,-1 , 0
  3449.2     .16       0  3664.8     .12       0  4994.5     .07       0
  5000.5     .12       0  6838.4     .16       0  6993.5     .12       0
  7038.7     .16       0  7171.4     .12       0
Bank Sta=3853.3,6698.3
XS Rating Curve= 0 ,0
Exp/Cntr=0.3,0.1

Type RM Length L Ch R = 1 ,100519  ,930,930,930
BEGIN DESCRIPTION:
UPPER KEECHI CREEK 14.0
END DESCRIPTION:
XS GIS Cut Line= 3
       3695699.6     10525210.16      3695099.61     10523210.19
      3693499.63     10522010.21
#Sta/Elev= 30
  2944.2  278.22  3131.2  263.45  3378.3  237.42  3502.8  228.45  3706.3  218.52
    3842  217.94  4134.4  212.58  4702.5  212.56  4735.6  210.22  4750.3  212.58
  4906.1  213.49  4977.4   212.5  4987.5  206.77  4990.2  206.27  4993.5  206.77
  5021.8  207.44  5029.6  212.99  5039.5  213.77  5324.9  215.12  5474.9  212.71
  5654.1  214.45  5832.2  210.83  6289.5  213.16  6760.4  211.11  6854.1  218.45
  6882.2  223.06  6899.1  230.47  6974.9  256.56  7010.4  264.76  7032.2  266.51
#Mann= 5 ,-1 , 0
  2944.2     .16       0  3502.8     .12       0  4987.5     .07       0
  4993.5     .12       0  6899.1     .16       0
Bank Sta=3842,6854.1
XS Rating Curve= 0 ,0
Exp/Cntr=0.3,0.1

Type RM Length L Ch R = 1 ,99589   ,980,980,980
BEGIN DESCRIPTION:
UPPER KEECHI CREEK 13.0
END DESCRIPTION:
XS GIS Cut Line= 3
      3696899.61     10523860.19      3695899.61     10522860.19
      3693899.58     10521260.16
#Sta/Elev= 30
  3598.2  236.64  3767.9   223.3  3862.3   219.2  4093.2  213.89  4715.4  214.38
  4885.1  210.97    4970  213.56  4984.1  207.12  5005.9  206.51  5008.6  206.01
  5011.9  206.51    5034  211.52  5147.7  208.06  5176.5  215.55  5488.6  216.37
  5595.9   211.1  5631.1  213.28  5773.6  211.15  5816.8  214.94  5901.6  212.62
  6513.1   214.4  6705.2  211.21  6762.9  213.47  6783.7  211.34  7111.8  211.56
  7211.1  222.33  7267.1  234.48  7317.5  239.45  7467.2  244.81  7573.7  252.62
#Mann= 4 ,-1 , 0
  3598.2     .16       0  3862.3     .12       0  5005.9     .07       0
  5011.9     .12       0
Bank Sta=4715.4,5176.5
XS Rating Curve= 0 ,0
Exp/Cntr=0.3,0.1

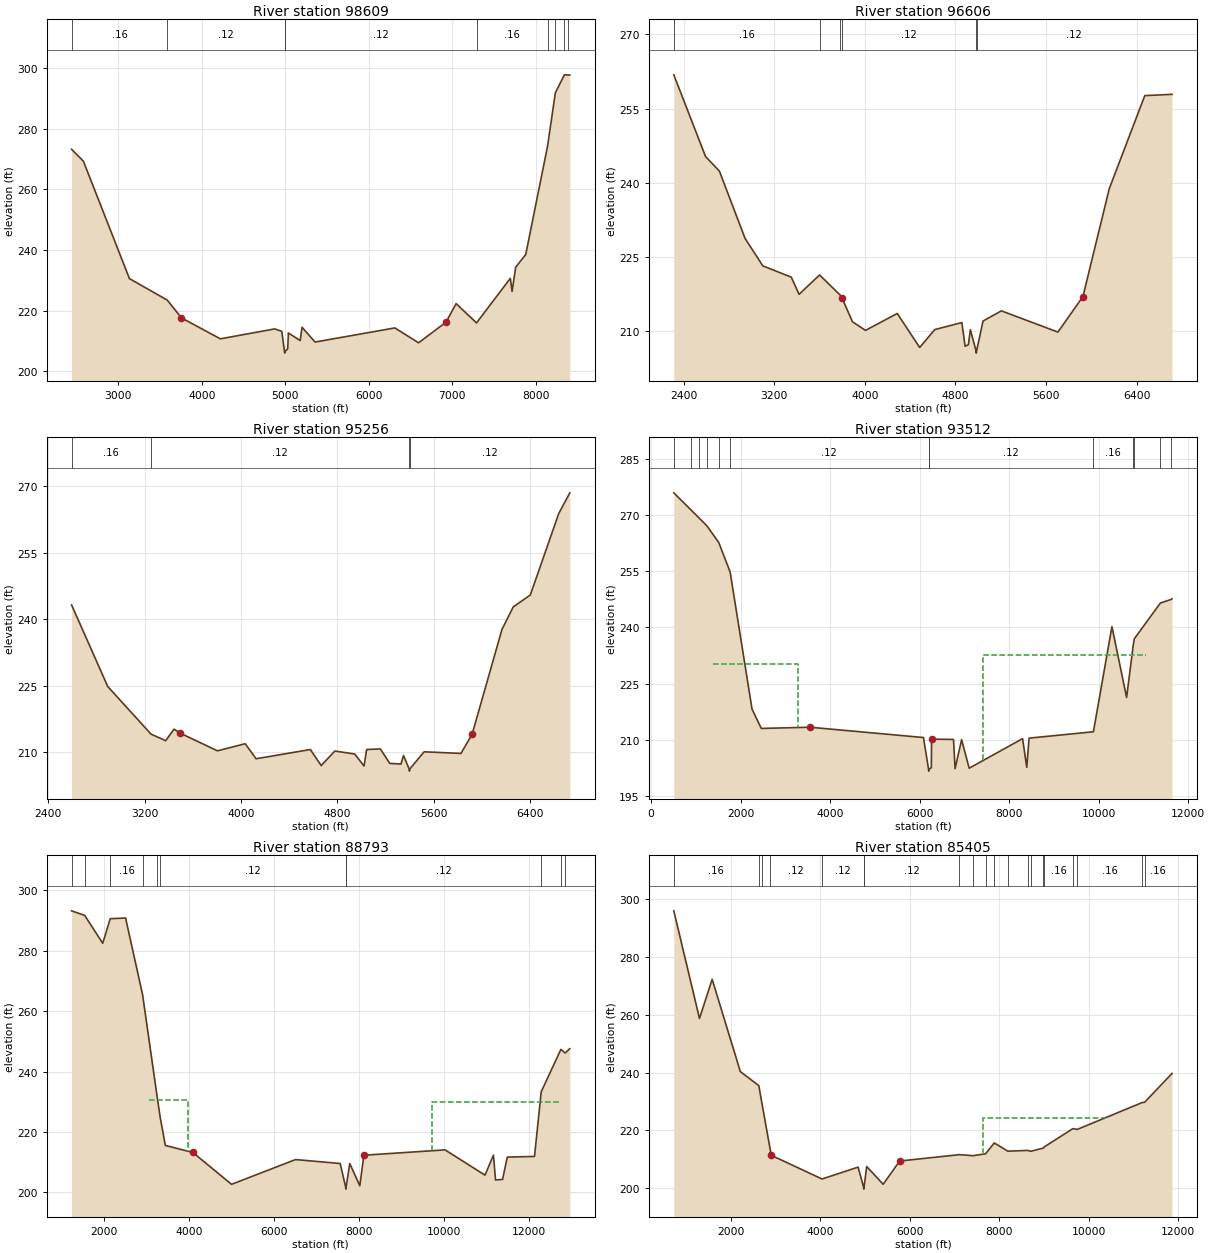
Type RM Length L Ch R = 1 ,98609   ,2003,2003,2003
BEGIN DESCRIPTION:
UPPER KEECHI CREEK 12.0
END DESCRIPTION:
XS GIS Cut Line= 3
      3698049.64     10524060.21      3696249.61     10522260.19
      3693549.65     10520160.22
#Sta/Elev= 30
  2440.7  273.25  2582.2  269.33  3133.7  230.56  3586.8  223.46    3756   217.6
  4222.6  210.68  4873.2  213.96    4958  213.14  4990.6  206.46  4993.3  205.96
  4996.6  206.46  5028.9  207.39    5037  212.62  5178.2  210.11  5200.8   214.5
  5356.4  209.62    6312  214.28  6596.1  209.37  6924.6  216.18  7045.9   222.3
    7290  215.93  7694.7  230.65  7715.5  226.31  7758.9  234.32  7879.3  238.53
  8140.4  274.26  8233.9  291.91  8342.3  297.84  8381.1   297.8  8406.8  297.78
#Mann= 9 ,-1 , 0
  2440.7     .16       0  3586.8     .12       0  4990.6     .07       0
  4996.6     .12       0    7290     .16       0  8140.4     .12       0
  8233.9     .16       0  8342.3     .12       0  8381.1     .16       0
Bank Sta=3756,6924.6
XS Rating Curve= 0 ,0
Exp/Cntr=0.3,0.1

Type RM Length L Ch R = 1 ,96606   ,1350,1350,1350
BEGIN DESCRIPTION:
UPPER KEECHI CREEK 11.0
END DESCRIPTION:
XS GIS Cut Line= 3
      3698108.37     10523779.69      3696858.39     10520932.52
      3696338.25     10519753.54
#Sta/Elev= 30
  2313.7  261.83  2594.2  245.33  2716.4  242.38    2943  228.78  3099.6  223.25
  3350.7  220.96  3419.6  217.49  3600.4  221.41  3785.2  217.28  3797.8  216.79
  3798.5  216.77  3890.8  211.96    4006  210.21  4286.4  213.63  4484.2  206.76
  4617.5  210.38  4856.4  211.79  4885.2  207.01    4914  207.33  4931.9  210.36
  4981.1  206.12  4983.9  205.62  4987.1  206.12  5043.5   212.1  5205.3  214.16
  5704.7  209.87  5925.5  217.05    6158  238.84  6471.3  257.63  6711.8  257.89
#Mann= 6 ,-1 , 0
  2313.7     .16       0  3600.4     .12       0  3785.2     .16       0
  3797.8     .12       0  4981.1     .07       0  4987.1     .12       0
Bank Sta=3798.5,5925.5
XS Rating Curve= 0 ,0
Exp/Cntr=0.3,0.1

Type RM Length L Ch R = 1 ,95256   ,1744,1744,1744
BEGIN DESCRIPTION:
UPPER KEECHI CREEK 10.0
END DESCRIPTION:
XS GIS Cut Line= 3
      3698099.61     10523160.24      3698029.69     10520991.46
      3696499.59     10519760.17
#Sta/Elev= 30
  2594.6  243.23  2894.8  224.83  3254.1  214.09  3375.3  212.62  3445.1  215.22
  3495.1  214.32  3805.3  210.33  4035.4  211.93  4125.4  208.54  4575.7  210.62
  4665.7  207.01  4779.2  210.28  4943.9  209.61  5021.3   206.9  5043.1  210.64
  5156.7  210.75  5235.1  207.49  5327.9  207.35  5348.7  209.28  5395.3  206.25
    5398  205.75  5401.3  206.25  5519.8  210.11  5825.4  209.74  5918.2  214.08
  6166.2  237.74    6259  242.77  6401.3  245.49  6636.5  263.82  6728.5  268.51
#Mann= 4 ,-1 , 0
  2594.6     .16       0  3254.1     .12       0  5395.3     .07       0
  5401.3     .12       0
Bank Sta=3495.1,5918.2
XS Rating Curve= 0 ,0
Exp/Cntr=0.3,0.1

Type RM Length L Ch R = 1 ,93512   ,4719,4719,4719
BEGIN DESCRIPTION:
UPPER KEECHI CREEK 9.0
END DESCRIPTION:
XS GIS Cut Line= 4
       3702029.7      10522574.8      3698641.37     10520064.46
      3698641.37     10518935.99      3693694.02     10515941.54
#Sta/Elev= 30
   508.7  275.94   889.5  271.41  1071.1  269.25  1248.3  267.14  1513.7  262.65
  1766.7  254.82  2256.2   218.2  2462.8  213.04  3550.1  213.36  6085.8  210.61
  6199.1  202.14  6201.9  201.64  6205.1  202.14  6260.3  202.54  6266.2  210.18
  6756.2   210.1  6791.3  202.31  6937.3  210.03    7106  202.42  8299.2  210.31
  8392.7  202.65  8444.4  210.45  9881.3  212.15 10294.8  240.21 10622.6  221.31
 10771.6  235.33 10794.2  236.95 11375.8  246.51 11620.1  247.49 11637.1  247.65
#Mann= 13 ,-1 , 0
   508.7     .16       0   889.5     .12       0  1071.1     .16       0
  1248.3     .12       0  1513.7     .16       0  1766.7     .12       0
  6199.1     .07       0  6205.1     .12       0  9881.3     .16       0
 10771.6     .12       0 10794.2     .16       0 11375.8      .1       0
 11620.1     .12       0
#XS Ineff= 2 ,-1
 1384.09 3293.18  230.32    742511052.27  232.55
Permanent Ineff=
       F       T
Bank Sta=3550.1,6266.2
XS Rating Curve= 0 ,0
Exp/Cntr=0.3,0.1

Type RM Length L Ch R = 1 ,88793   ,3388,3388,3388
BEGIN DESCRIPTION:
Mapping XS ebe2e9c4
END DESCRIPTION:
XS GIS Cut Line= 3
      3704826.26     10519825.74      3700334.08     10517785.82
      3693868.62     10515724.68
#Sta/Elev= 30
  1231.4  293.23  1541.2  291.71  1963.7  282.48  2140.7  290.62  2501.7  290.85
  2901.1  265.51  3248.1  231.28  3313.4  225.05  3437.2  215.52  4082.2  213.21
  4994.8  202.64  6498.4  210.84  7549.9  209.54    7681  201.55  7683.8  201.05
    7687  201.55  7775.4  209.53  8011.3  202.16  8107.9  212.28 10017.8  214.05
 10955.9  205.68 11155.3   212.3 11203.5  204.09 11369.8  204.25 11480.6  211.65
 12120.9  211.88 12278.3  233.28 12741.8  247.33 12841.6  246.14 12951.1  247.58
#Mann= 11 ,-1 , 0
  1231.4     .16       0  1541.2     .05       0  2140.7     .16       0
  2901.1     .12       0  3248.1     .16       0  3313.4     .12       0
    7681     .07       0    7687     .12       0 12278.3     .16       0
 12741.8     .16       0 12841.6     .16       0
#XS Ineff= 2 ,-1
 3046.59 3961.36  230.42 9704.5512751.14  230.04
Permanent Ineff=
       F       F
Bank Sta=4082.2,8107.9
XS Rating Curve= 0 ,0
Exp/Cntr=0.3,0.1

Type RM Length L Ch R = 1 ,85405   ,1963,1963,1963
BEGIN DESCRIPTION:
UPPER KEECHI CREEK 8.0
END DESCRIPTION:
XS GIS Cut Line= 4
      3704804.54     10519456.79      3702374.01     10516874.36
      3701527.66      10515919.5      3695429.52     10514291.88
#Sta/Elev= 30
   731.3   295.9  1305.3   258.7  1588.5  272.24    2218  240.36  2630.8   235.5
  2706.9  228.86  2878.9  214.02  2911.1  211.42  4043.5  203.24  4850.4  207.34
  4975.1  200.24  4977.8  199.74  4981.1  200.24  5041.9  207.55  5409.9  201.42
  5779.3  209.45  7111.7  211.65  7417.9  211.29    7698  211.95    7893   215.7
  8196.3  212.85  8644.6  213.11  8708.1  212.82  8991.2  213.92  9002.4  214.26
    9650  220.64    9748  220.38 11200.7  229.67 11252.7  229.75 11865.2  239.71
#Mann= 20 ,-1 , 0
   731.3     .16       0  2630.8     .12       0  2706.9     .16       0
  2878.9     .12       0  4043.5     .12       0  4975.1     .07       0
  4981.1     .12       0  7111.7     .16       0  7417.9     .12       0
    7698     .16       0    7893     .12       0  8196.3     .16       0
  8644.6     .12       0  8708.1     .16       0  8991.2     .12       0
  9002.4     .16       0    9650     .12       0    9748     .16       0
 11200.7     .05       0 11252.7     .16       0
#XS Ineff= 1 ,-1
 7643.1810390.91  224.26
Permanent Ineff=
       F
Bank Sta=2911.1,5779.3
XS Rating Curve= 0 ,0
Exp/Cntr=0.3,0.1

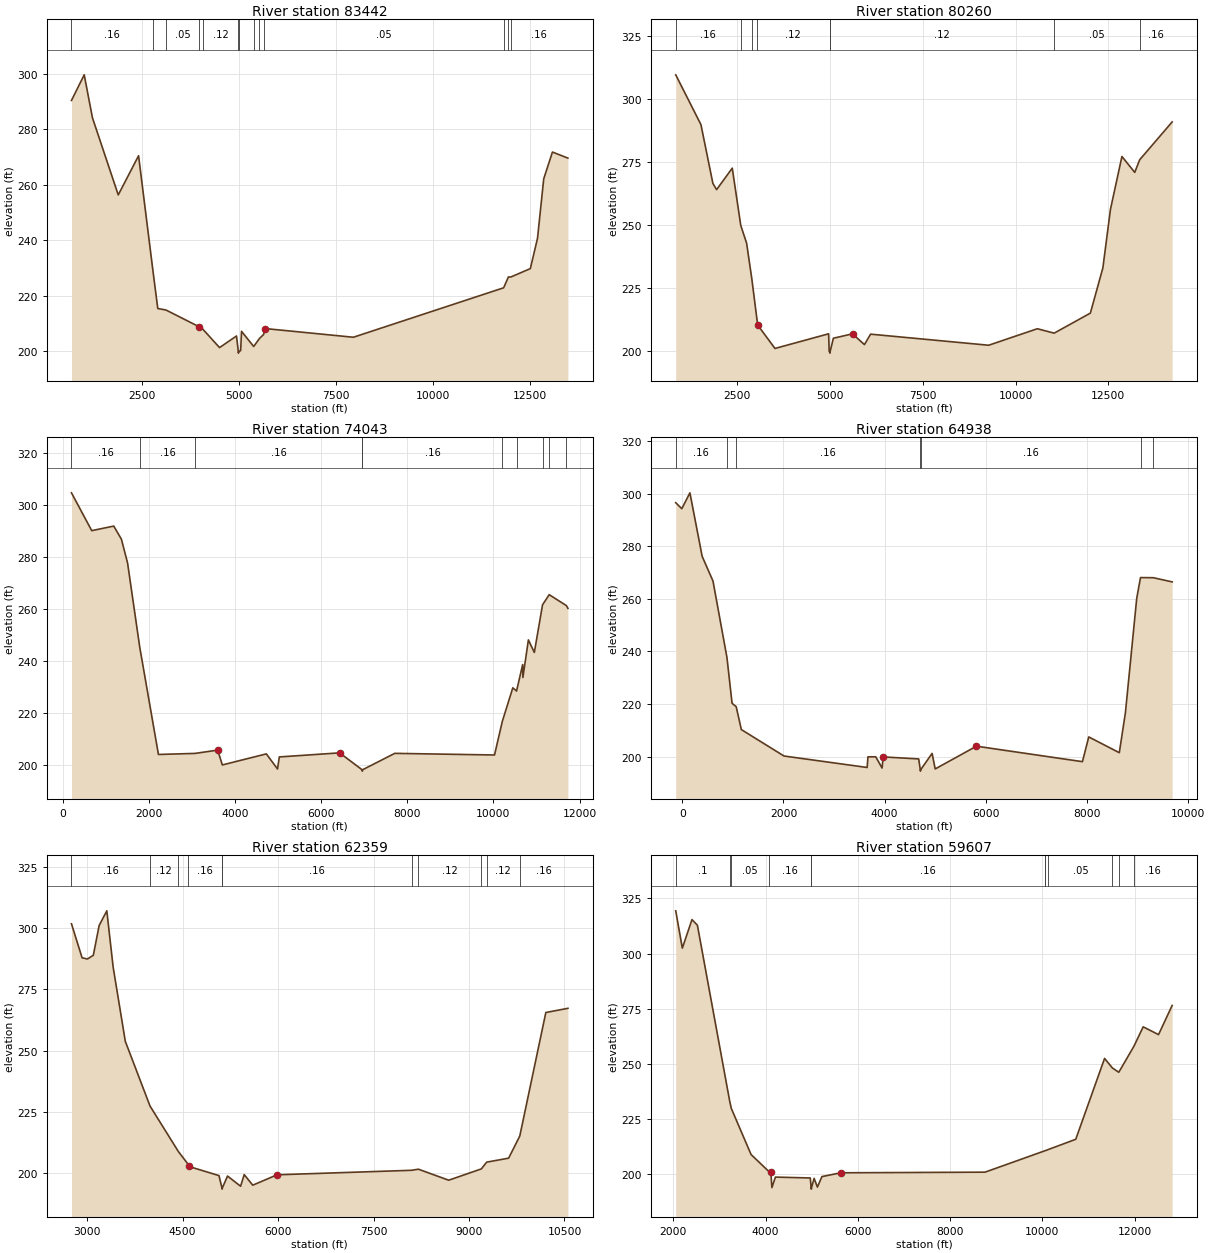
Type RM Length L Ch R = 1 ,83442   ,3182,3182,3182
BEGIN DESCRIPTION:
Mapping XS 7a6ec129
END DESCRIPTION:
XS GIS Cut Line= 4
      3706236.87     10518296.53      3703459.08     10515657.63
      3702764.64     10514685.41      3696063.96     10510762.22
#Sta/Elev= 30
   680.1  290.37  1007.9  299.59  1220.2  284.12  1885.2  256.33  2408.6  270.45
  2775.5  229.41  2903.7  215.42  3115.1  214.88  3973.1  208.82  4056.8   208.1
  4495.3  201.34  4932.3  205.53  4979.6  199.85  4982.4  199.35  4985.6  199.85
  5039.2  200.27  5061.4  207.21  5374.7  201.74  5524.2  204.63  5630.3  206.06
    5677  208.19    7943  205.07 11815.1  222.88 11938.2  226.79 11998.4  226.76
 12502.7  229.79 12687.8   240.7   12848  262.13 13072.8  271.78   13471  269.59
#Mann= 13 ,-1 , 0
   680.1     .16       0  2775.5     .12       0  3115.1     .05       0
  3973.1     .16       0  4056.8     .12       0  4979.6     .07       0
  4985.6     .12       0  5374.7     .05       0  5524.2     .16       0
  5630.3     .05       0 11815.1     .16       0 11938.2     .05       0
 11998.4     .16       0
Bank Sta=3973.1,5677
XS Rating Curve= 0 ,0
Exp/Cntr=0.3,0.1

Type RM Length L Ch R = 1 ,80260   ,6217,6217,6217
BEGIN DESCRIPTION:
Mapping XS 27f90f77
END DESCRIPTION:
XS GIS Cut Line= 3
      3707874.31     10518006.21      3704645.15     10513605.17
      3700244.37     10507017.03
#Sta/Elev= 30
   839.6  309.72  1519.1  289.91    1841  266.52  1941.3  264.03  2363.5  272.58
  2592.5   249.8  2750.1  242.73    2889  228.71  3023.4  213.07  3051.1  210.09
  3514.9  200.82  4961.2  206.65  4975.8  199.58  4993.7  199.46  4996.4  198.96
  4999.7  199.46  5088.9  204.89  5604.8  206.64  5926.7  202.35  6091.8  206.51
  9275.2   202.1 10587.7  208.67 11040.2  206.91 12016.5  214.88 12353.7  232.89
 12557.6  256.16 12867.3  277.22 13212.7   270.9 13345.4  275.91   14221  290.98
#Mann= 8 ,-1 , 0
   839.6     .16       0  2592.5     .05       0    2889     .16       0
  3023.4     .12       0  4993.7     .07       0  4999.7     .12       0
 11040.2     .05       0 13345.4     .16       0
Bank Sta=3051.1,5604.8
XS Rating Curve= 0 ,0
Exp/Cntr=0.3,0.1

Type RM Length L Ch R = 1 ,74043   ,9105,9105,9105
BEGIN DESCRIPTION:
Mapping XS 799e2fb5
END DESCRIPTION:
XS GIS Cut Line= 4
      3707926.39     10517719.73       3707119.1     10513943.71
      3708343.06     10509777.05      3707848.27     10506495.81
#Sta/Elev= 30
   207.4  304.62   677.3  290.06  1188.6  291.82  1365.7  286.79  1509.1  277.65
  1790.6  245.33  2225.7  203.92  3075.9  204.33    3602   205.6  3708.5  199.89
  4730.6  204.14  4989.6  198.33  5031.3  202.97  6431.6  204.54  6955.2  198.01
    6958  197.51  6961.2  198.01  7711.2  204.35 10026.4  203.72 10207.6  216.66
 10451.1  229.58 10538.1  228.33   10680  238.54   10685  233.53 10812.8  248.02
 10950.6  243.19   11141  261.51 11295.4  265.43 11695.3  261.21 11729.8  260.18
#Mann= 10 ,-1 , 0
   207.4     .16       0  1790.6     .16       0  3075.9     .16       0
  6955.2     .07       0  6961.2     .16       0 10207.6     .12       0
 10538.1     .16       0   11141     .12       0 11295.4     .16       0
 11695.3     .12       0
Bank Sta=3602,6431.6
XS Rating Curve= 0 ,0
Exp/Cntr=0.3,0.1

Type RM Length L Ch R = 1 ,64938   ,2579,2579,2579
BEGIN DESCRIPTION:
UPPER KEECHI CREEK 7.0
END DESCRIPTION:
XS GIS Cut Line= 3
      3711138.21     10516252.76       3709888.2     10509898.57
      3708395.84     10506913.85
#Sta/Elev= 30
    -130  296.51   -10.2  294.23   150.3  300.26   392.4  276.14   606.4  266.77
   882.9  237.68   983.5  220.33    1065  219.04    1167  210.34  2010.3   200.3
  3653.7  195.95  3669.8  199.98    3824     200  3949.3  195.73  3969.7  199.96
  4672.9  199.19  4704.7  195.06  4707.4  194.56  4710.7  195.06  4937.9  201.29
    4999  195.39  5814.4  204.03  7909.4  198.15  8034.5  207.55  8638.3  201.56
  8759.1  216.76  8982.7  260.19  9057.5  268.07  9310.7  268.02    9683  266.43
#Mann= 7 ,-1 , 0
    -130     .16       0   882.9     .12       0    1065     .16       0
  4704.7     .07       0  4710.7     .16       0  9057.5     .12       0
  9310.7     .16       0
Bank Sta=3969.7,5814.4
XS Rating Curve= 0 ,0
Exp/Cntr=0.3,0.1

Type RM Length L Ch R = 1 ,62359   ,2752,2752,2752
BEGIN DESCRIPTION:
UPPER KEECHI CREEK 6.0
END DESCRIPTION:
XS GIS Cut Line= 3
      3713638.18     10512676.33      3711311.81     10510141.63
      3708673.74     10506670.48
#Sta/Elev= 30
  2753.8  301.79    2920  287.93  3005.1  287.41    3097  288.94  3188.8  301.11
  3309.1  307.08  3408.3  284.14  3599.5  253.81  3987.7   227.4  4433.5  208.81
  4581.9  203.79  4597.1  202.74  5071.3  198.99  5118.2  193.97    5121  193.47
  5124.2  193.97  5205.7  198.81    5411  194.65  5467.7  199.39  5602.2  195.08
  5984.4  199.32  8100.1  201.16  8204.6  201.61  8680.9  197.11    9194  201.73
  9277.5  204.48  9622.9  206.11  9798.2  215.16 10207.3  265.57 10554.1  267.28
#Mann= 11 ,-1 , 0
  2753.8     .16       0  3987.7     .12       0  4433.5     .16       0
  4581.9     .16       0  5118.2     .07       0  5124.2     .16       0
  8100.1     .16       0  8204.6     .12       0    9194     .05       0
  9277.5     .12       0  9798.2     .16       0
Bank Sta=4597.1,5984.4
XS Rating Curve= 0 ,0
Exp/Cntr=0.3,0.1

Type RM Length L Ch R = 1 ,59607   ,2497,2497,2497
BEGIN DESCRIPTION:
UPPER KEECHI CREEK 5.0
END DESCRIPTION:
XS GIS Cut Line= 3
      3714058.56     10512486.26      3712148.83     10508840.41
      3709371.05     10502807.42
#Sta/Elev= 30
  2054.6  319.38  2197.5  302.44  2406.9  315.41  2524.3  312.83  3225.8  232.79
  3260.1  229.64    3687  208.78  4072.7  201.06  4116.1  200.61  4138.6  193.76
  4215.1  198.52  4970.4  198.12  4989.5  193.56  4992.3  193.06  4995.5  193.56
    5053  197.94  5124.9  193.99  5222.3  198.74  5628.7  200.47  8757.5  200.76
 10060.4  210.51 10127.4  211.03 10723.1  215.68 11347.7  252.39 11516.6  248.07
 11655.6   246.1 11983.7  257.91 12184.5  266.72   12517  263.19 12812.1  276.43
#Mann= 12 ,-1 , 0
  2054.6      .1       0  3225.8     .16       0  3260.1     .05       0
  4072.7     .16       0  4989.5     .07       0  4995.5     .16       0
 10060.4     .05       0 10060.4     .08       0 10127.4     .05       0
 11516.6     .16       0 11655.6     .12       0 11983.7     .16       0
Bank Sta=4116.1,5628.7
XS Rating Curve= 0 ,0
Exp/Cntr=0.3,0.1

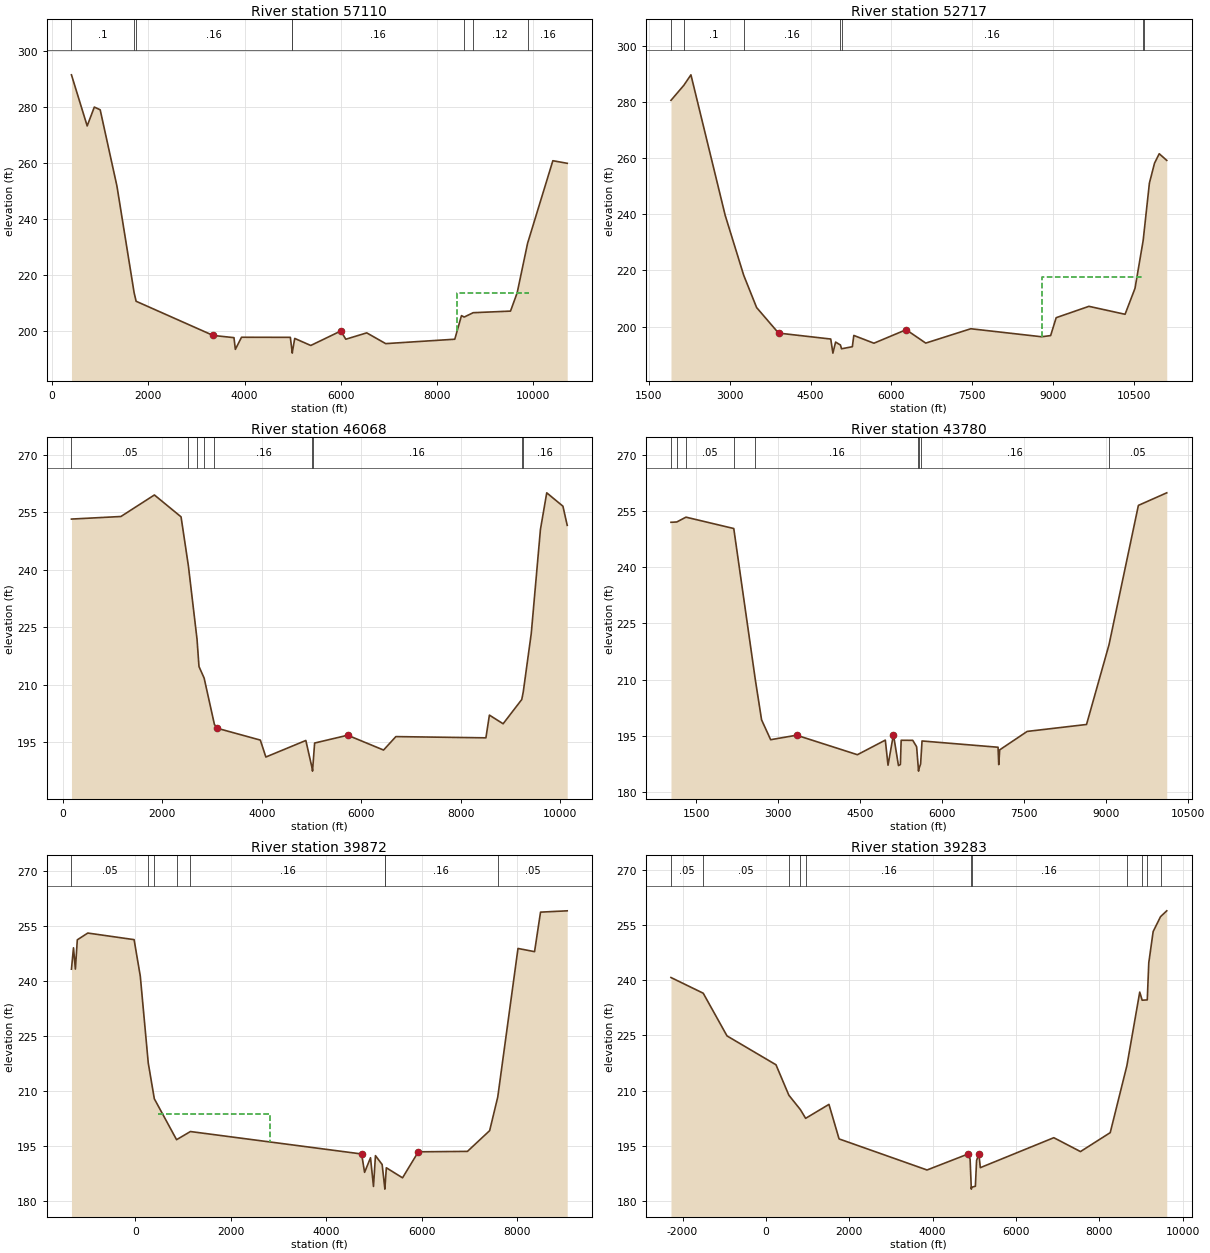
Type RM Length L Ch R = 1 ,57110   ,4393,4393,4393
BEGIN DESCRIPTION:
UPPER KEECHI CREEK 4.0
END DESCRIPTION:
XS GIS Cut Line= 3
      3716641.02     10513278.35      3714143.83     10510193.86
      3715078.53     10503929.34
#Sta/Elev= 30
   400.6  291.38   727.5  273.15   876.2  279.88   997.7   278.9  1346.2  251.66
  1702.5   213.7  1744.3   210.6  3344.5  198.41  3777.8  197.62  3806.6  193.44
  3934.5  197.76  4949.3  197.73  4986.7   192.6  4989.4   192.1  4992.7   192.6
  5040.3  197.34  5373.9  194.83  5998.3     200  6101.9  197.06  6536.6  199.33
    6931  195.49  8366.7  197.06  8505.6  205.48  8562.6  204.97  8748.3  206.52
  9524.5  207.09    9663  213.61    9879  231.26 10404.7  260.74 10703.1  259.82
#Mann= 8 ,-1 , 0
   400.6      .1       0  1702.5     .05       0  1744.3     .16       0
  4986.7     .07       0  4992.7     .16       0  8562.6     .16       0
  8748.3     .12       0    9879     .16       0
#XS Ineff= 1 ,-1
 8413.64 9906.82  213.61
Permanent Ineff=
       F
Bank Sta=3344.5,5998.3
XS Rating Curve= 0 ,0
Exp/Cntr=0.3,0.1

Type RM Length L Ch R = 1 ,52717   ,6649,6649,6649
BEGIN DESCRIPTION:
Mapping XS d46948ad
END DESCRIPTION:
XS GIS Cut Line= 4
      3717841.74     10512876.15      3716826.12      10511157.4
      3716956.33     10508839.69      3715420.02     10504204.73
#Sta/Elev= 30
  1909.6  280.72  2148.6   286.1  2279.9  289.83  2915.4  239.71  3259.2  218.31
  3499.1  206.77    3906  197.66  4874.7  195.54  4914.5  190.51  4964.9  194.46
    5055   193.4    5075  192.06  5275.4   192.8  5302.8  196.82    5676  194.05
  6273.8  198.87  6637.7  194.09  7473.8  199.21  8786.8  196.35  8955.4  196.77
  9058.5  203.16    9666  207.21 10336.8  204.37 10521.7  213.65 10672.6  230.69
 10680.5  232.09 10788.5   251.2 10883.3  258.28 10970.7  261.67 11110.3   259.3
#Mann= 7 ,-1 , 0
  1909.6     .05       0  2148.6      .1       0  3259.2     .16       0
    5055     .07       0    5075     .16       0 10672.6     .12       0
 10680.5     .16       0
#XS Ineff= 1 ,-1
 8795.4510677.27  217.72
Permanent Ineff=
       F
Bank Sta=3906,6273.8
XS Rating Curve= 0 ,0
Exp/Cntr=0.3,0.1

Type RM Length L Ch R = 1 ,46068   ,2288,2288,2288
BEGIN DESCRIPTION:
Mapping XS 56e74f69
END DESCRIPTION:
XS GIS Cut Line= 3
      3720133.41     10512146.98      3719508.41     10508006.36
       3715550.1     10503787.63
#Sta/Elev= 30
     170  253.24  1164.9  253.91  1838.7  259.53  2374.7  253.82  2522.7  240.99
  2696.4  221.83  2735.5  214.75  2839.1  211.74  3045.7  199.65  3107.3  198.63
  3969.3  195.56  4080.6  191.14  4884.7  195.46    5016  187.96  5018.8  187.46
    5022  187.96  5061.5  194.79  5726.3  196.83  6448.2  192.96  6695.9  196.47
    8507  196.15  8577.4  202.08  8853.3  199.82  9228.4  206.16  9258.7  208.17
  9419.4  223.41  9603.6  250.51  9730.6  260.09 10056.3   256.6 10142.5  251.61
#Mann= 9 ,-1 , 0
     170     .05       0  2522.7     .16       0  2696.4     .12       0
  2839.1     .16       0  3045.7     .16       0    5016     .07       0
    5022     .16       0  9228.4     .05       0  9258.7     .16       0
Bank Sta=3107.3,5726.3
XS Rating Curve= 0 ,0
Exp/Cntr=0.3,0.1

Type RM Length L Ch R = 1 ,43780   ,3908,3908,3908
BEGIN DESCRIPTION:
Mapping XS f0915579
END DESCRIPTION:
XS GIS Cut Line= 4
      3721018.82     10510636.53      3720393.83     10507042.82
      3719456.33     10506079.27       3717737.6      10502381.4
#Sta/Elev= 30
  1037.2  251.93  1144.4  252.02  1311.6   253.3    2186  250.27  2580.3  209.94
  2694.5  199.26  2860.5  193.95  3335.2  195.15  4447.9  189.95  4958.4  193.84
    5008  187.15    5107  195.33  5198.9  187.05  5234.1  187.33  5248.3   193.8
  5460.5  193.78  5531.2  192.07  5563.7  186.07  5566.4  185.57  5569.7  186.07
  5603.9  187.46  5630.2  193.61  7020.7  191.94  7033.5   187.3  7050.9  191.24
  7553.6  196.16  8639.6  198.01  9050.8  219.28  9588.3  256.44   10107  259.79
#Mann= 9 ,-1 , 0
  1037.2     .05       0  1144.4      .1       0  1311.6     .05       0
    2186     .05       0  2580.3     .16       0  5563.7     .07       0
  5569.7     .12       0  5603.9     .16       0  9050.8     .05       0
Bank Sta=3335.2,5107
XS Rating Curve= 0 ,0
Exp/Cntr=0.3,0.1

Type RM Length L Ch R = 1 ,39872   ,589,589,589
BEGIN DESCRIPTION:
Mapping XS b4aa6a02
END DESCRIPTION:
XS GIS Cut Line= 4
      3721801.47     10510582.73      3721612.58     10505256.36
      3721112.58     10503818.86      3719404.58      10500715.3
#Sta/Elev= 30
 -1340.5  243.21 -1297.9  249.04 -1257.9  243.23 -1217.9  251.22  -997.7  253.07
   -27.1  251.27     103  241.28   269.6   217.6   396.9  207.81   863.4  196.63
  1153.6  198.86  4743.1  192.73  4805.3  187.71  4929.7   191.7  4991.9  183.86
  5033.3  192.28  5173.2  189.86  5227.1  183.63  5229.9  183.13  5233.1  183.63
  5261.2  188.96    5601  186.22    5932  193.32  6961.9  193.44  7427.3   199.1
  7597.3  208.28  8021.6  248.86  8369.1  247.99  8494.1  258.78  9053.7  259.14
#Mann= 8 ,-1 , 0
 -1340.5     .05       0   269.6     .16       0   396.9     .05       0
   863.4     .05       0  1153.6     .16       0  5227.1     .07       0
  5233.1     .16       0  7597.3     .05       0
#XS Ineff= 1 ,-1
  481.82 2827.27  203.73
Permanent Ineff=
       F
Bank Sta=4743.1,5932
XS Rating Curve= 0 ,0
Exp/Cntr=0.3,0.1

Type RM Length L Ch R = 1 ,39283   ,1213,1213,1213
BEGIN DESCRIPTION:
Mapping XS 5d76b81e
END DESCRIPTION:
XS GIS Cut Line= 3
       3724961.2     10510582.76      3721002.86      10502388.3
      3719822.67     10499854.38
#Sta/Elev= 30
 -2276.6  240.74 -1502.8  236.48  -931.8  224.88   243.1  217.04   551.5  208.78
   828.9  204.85   954.8  202.49  1513.9  206.28    1757   196.9  3867.6  188.46
    4841  192.75  4900.5  191.44  4928.4  183.76  4931.1  183.26  4934.4  183.76
  5027.4  184.04  5055.9  191.01  5111.5  192.86  5145.9  189.09  6909.4  197.23
  7549.1  193.46  8262.9   198.6  8662.8   216.8  8971.2  236.78  9029.4  234.58
  9151.8  234.66  9188.1  244.74  9292.8  253.22  9470.3  257.28  9619.1  258.86
#Mann= 11 ,-1 , 0
 -2276.6     .05       0 -1502.8     .05       0   551.5     .16       0
   828.9     .16       0   954.8     .16       0  4928.4    .033       0
  4934.4     .16       0  8662.8     .16       0  9029.4     .05       0
  9151.8     .16       0  9470.3     .05       0
Bank Sta=4841,5111.5
XS Rating Curve= 0 ,0
Exp/Cntr=0.3,0.1