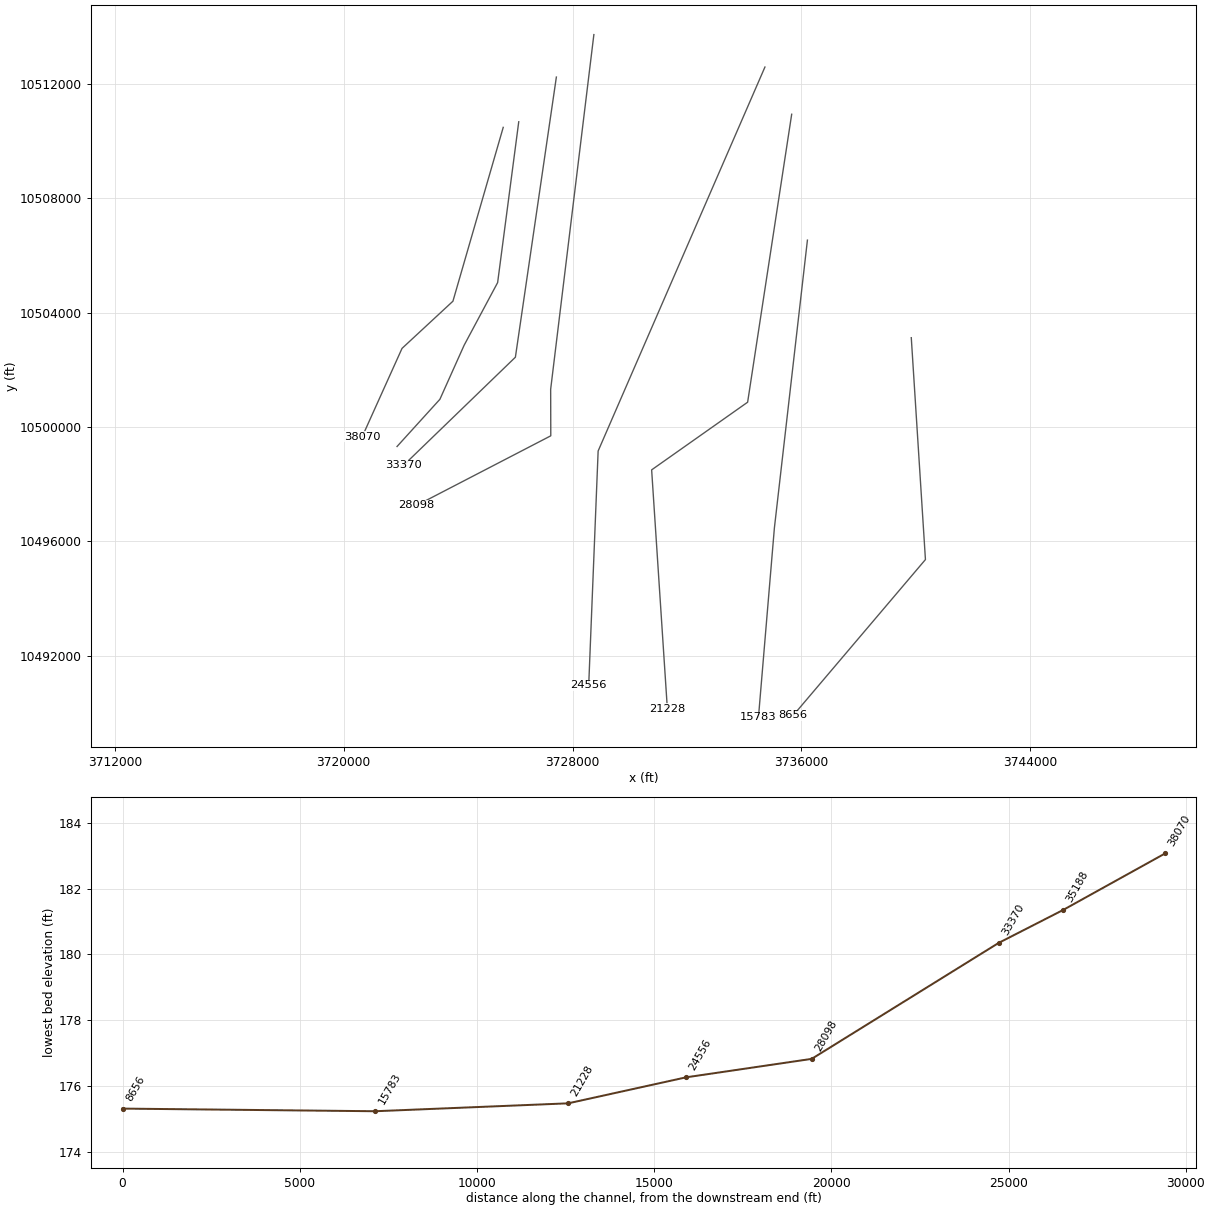
HEC-RAS study UPPER KEECHI CREEK.prj: UPPER KEECHI CREEK Base Level Engineering

--- UPPER KEECHI CREEK.g01 (geometry) --- (continued)

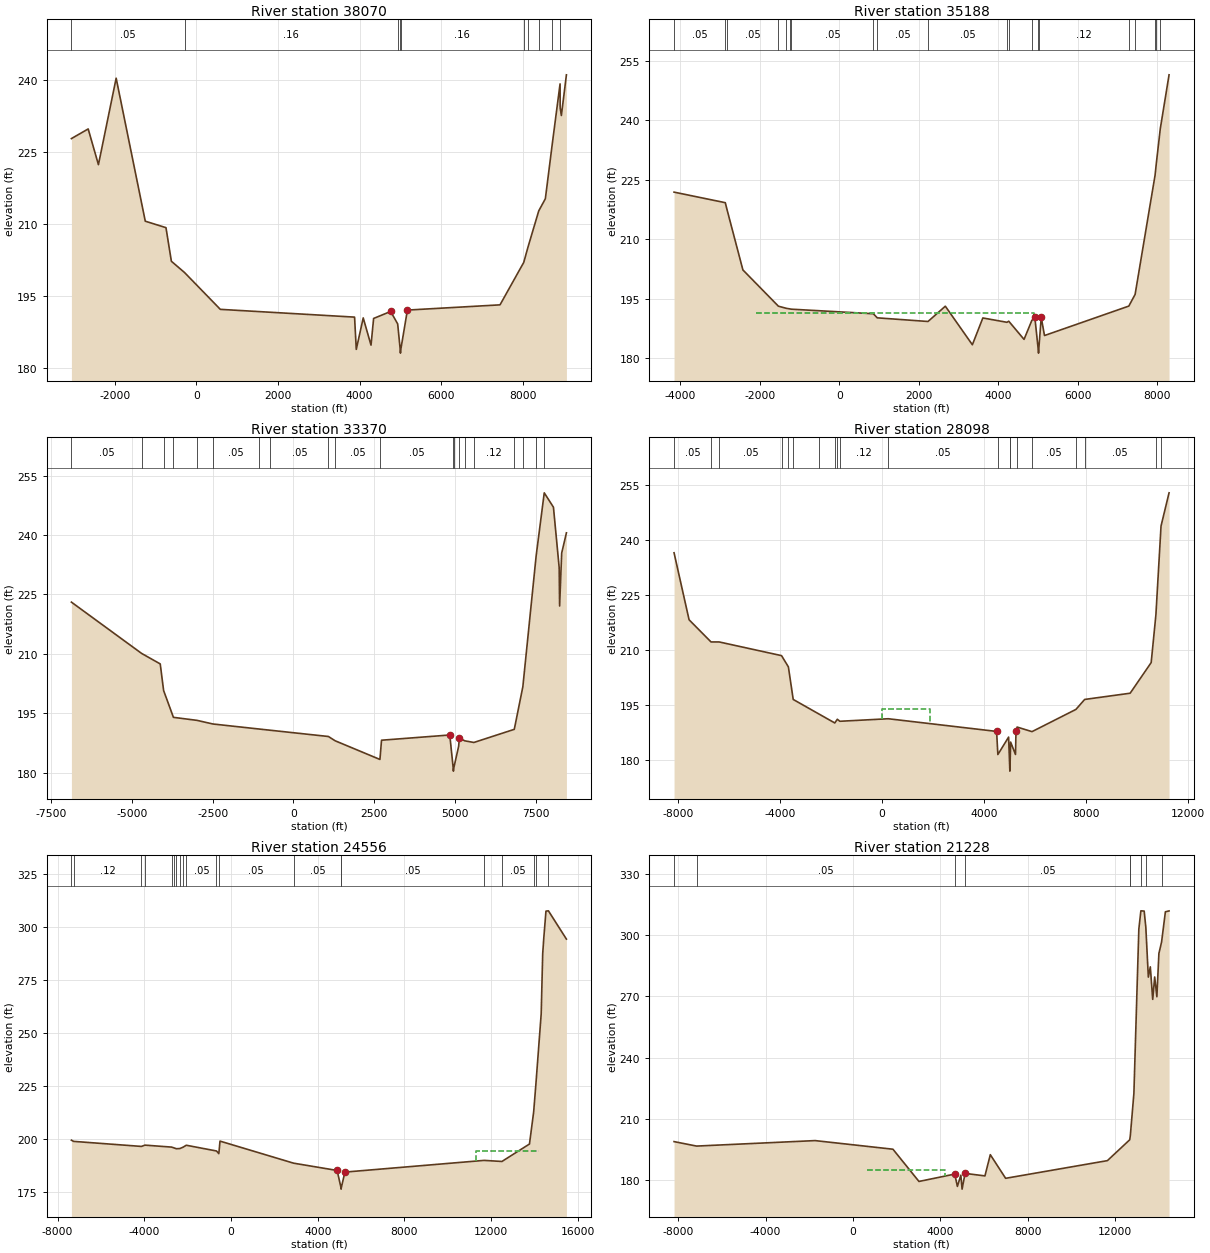
Type RM Length L Ch R = 1 ,38070   ,2882,2882,2882
BEGIN DESCRIPTION:
Mapping XS 6392ecce
END DESCRIPTION:
XS GIS Cut Line= 4
      3725577.88     10510473.73      3723820.07     10504397.37
      3722040.56     10502748.06      3720651.68     10499666.49
#Sta/Elev= 30
 -3064.8  227.82 -2653.6  229.83 -2402.7  222.38 -1968.1  240.42 -1254.4  210.59
  -747.4  209.24  -614.8  202.23    -292  199.88   584.5   192.2  3874.9  190.58
  3916.9  183.85    4087  190.42    4278  184.74  4341.6   190.3  4759.4  191.76
  4931.6  189.16  4996.8  183.57  4999.5  183.07  5002.8  183.57  5169.9  192.05
  7439.7  193.14    8021  201.99    8126  205.21  8388.5  212.73  8550.9  215.28
  8724.1  226.95  8911.4  239.23  8914.5  234.22  8943.1  232.64  9067.1  241.12
#Mann= 10 ,-1 , 0
 -3064.8     .05       0    -292     .16       0  4931.6     .12       0
  4996.8     .07       0  5002.8     .16       0    8021     .05       0
    8126     .16       0  8388.5     .12       0  8724.1     .16       0
  8911.4     .05       0
Bank Sta=4759.4,5169.9
XS Rating Curve= 0 ,0
Exp/Cntr=0.3,0.1

Type RM Length L Ch R = 1 ,35188   ,1818,1818,1818
BEGIN DESCRIPTION:
Mapping XS a86bcfa6
END DESCRIPTION:
XS GIS Cut Line= 5
      3726120.42     10510669.08      3725382.57     10505048.41
       3724210.7     10502856.57      3723364.34     10500968.55
      3721866.97     10499319.26
#Sta/Elev= 30
 -4159.3  221.91 -2870.5  219.25 -2827.2  217.52 -2427.5  202.31 -1534.2  193.17
 -1335.3  192.64 -1235.9  192.47 -1206.8  192.42   852.9  191.27   952.3  190.24
  2228.5  189.32  2664.2  193.17  3344.6  183.46    3608  190.21  4212.8  189.12
  4259.7  189.39  4644.3  184.81  4840.2  189.59  4915.8  190.37  5005.5  181.85
  5008.2  181.35  5011.5  181.85    5076  190.35  5158.5  185.78  7279.6   193.2
  7438.1  196.15  7940.3   226.2  7973.2  229.32  8070.7  237.86  8291.7  251.46
#Mann= 20 ,-1 , 0
 -4159.3     .05       0 -2870.5     .08       0 -2827.2     .05       0
 -1534.2     .08       0 -1335.3     .05       0 -1235.9     .07       0
 -1206.8     .05       0   852.9     .08       0   952.3     .05       0
  2228.5     .05       0  4212.8     .08       0  4259.7     .05       0
  4840.2     .12       0  5005.5     .07       0  5011.5     .12       0
  7279.6     .05       0  7438.1     .12       0  7940.3     .16       0
  7973.2     .12       0  8070.7     .16       0
#XS Ineff= 1 ,-1
-2098.48 4903.98  191.53
Permanent Ineff=
       T
Bank Sta=4915.8,5076
XS Rating Curve= 0 ,0
Exp/Cntr=0.3,0.1

Type RM Length L Ch R = 1 ,33370   ,5272,5272,5272
BEGIN DESCRIPTION:
Mapping XS ff4831de
END DESCRIPTION:
XS GIS Cut Line= 3
      3727435.52     10512231.55      3726003.23      10502439.9
      3722097.66     10498664.51
#Sta/Elev= 30
 -6875.7  223.05 -4701.7  210.09 -4125.4  207.44 -4020.5  200.71   -3717  193.94
 -2988.3  193.18 -2493.5  192.26 -1056.7  190.98  -714.9  190.68  1082.2   189.1
  1290.2  188.02  2677.9   183.3  2726.8  188.16    4840  189.48  4950.2  180.85
    4953  180.35  4956.2  180.85  5114.5  186.61  5137.1  188.66  5309.3     188
  5586.7  187.59  6837.7  190.91  7102.8  201.66  7515.1  234.76  7765.6  250.67
  8050.7  247.03  8227.5   231.8  8241.6  222.08  8305.4  235.44  8452.2  240.56
#Mann= 20 ,-1 , 0
 -6875.7     .05       0 -4701.7     .05       0 -4020.5     .12       0
   -3717     .05       0 -2988.3     .05       0 -2493.5     .05       0
 -1056.7     .12       0  -714.9     .05       0  1082.2     .07       0
  1290.2     .05       0  2677.9     .05       0  4950.2     .07       0
  4956.2     .12       0  5114.5     .16       0  5309.3     .05       0
  5586.7     .12       0  6837.7     .16       0  7102.8     .12       0
  7515.1     .16       0  7765.6     .16       0
#XS Ineff= 1 ,-1
-1471.64 4801.94  189.43
Permanent Ineff=
       T
Bank Sta=4840,5137.1
XS Rating Curve= 0 ,0
Exp/Cntr=0.3,0.1

Type RM Length L Ch R = 1 ,28098   ,3542,3542,3542
BEGIN DESCRIPTION:
Mapping XS 6f173627
END DESCRIPTION:
XS GIS Cut Line= 4
      3728746.29     10513715.98      3727235.87     10501320.11
      3727240.21      10499692.5      3722553.64     10497262.43
#Sta/Elev= 30
   -8147  236.44 -7558.1  218.15 -6698.9   212.1 -6380.2   212.1   -3935  208.36
 -3667.4  205.29 -3478.2   196.4 -2451.7  192.35 -1849.5  189.98 -1750.2  190.99
 -1650.9  190.44   246.9  191.13  4490.5  187.67  4539.9  181.36  4960.5  186.12
  5007.5  177.33  5010.2  176.83  5013.5  177.33  5040.5  184.76  5230.5  181.38
  5250.5  187.69  5294.7  188.86  5877.9  187.61  7598.6  193.68  7941.2   196.4
  9723.1   198.1   10547  206.47 10731.9   219.5 10933.3  243.76 11247.3  252.81
#Mann= 20 ,-1 , 0
   -8147     .05       0 -6698.9     .07       0 -6380.2     .05       0
   -3935     .16       0 -3667.4     .16       0 -3478.2     .12       0
 -2451.7     .05       0 -1849.5     .08       0 -1750.2     .05       0
 -1650.9     .12       0   246.9     .05       0  4539.9     .12       0
  5007.5     .07       0  5013.5     .12       0  5294.7     .05       0
  5877.9     .05       0  7598.6     .12       0  7941.2     .05       0
 10731.9     .16       0 10933.3     .05       0
#XS Ineff= 2 , 0
       0 1864.91  193.72               0
Permanent Ineff=
       T       F
Bank Sta=4490.5,5250.5
XS Rating Curve= 0 ,0
Exp/Cntr=0.3,0.1

Type RM Length L Ch R = 1 ,24556   ,3328,3328,3328
BEGIN DESCRIPTION:
Mapping XS cf2e912a
END DESCRIPTION:
XS GIS Cut Line= 3
      3734725.46     10512582.03      3728895.47     10499162.05
      3728565.47     10490967.02
#Sta/Elev= 30
 -7361.9  199.39   -7257  198.83 -4129.4  196.45   -3971  197.06 -2737.4  196.13
 -2628.6  195.74 -2519.8  195.36 -2352.7  195.46 -2193.5  196.18 -2064.9  197.01
  -670.3   194.3  -561.5  193.04  -507.8  198.96    2889  188.53  4894.9  185.09
  5077.3  176.77    5080  176.27  5083.3  176.77  5254.7  184.32 11674.9  189.85
 12495.7  189.34 13766.9  197.58   13960  212.73 14058.4  225.18 14307.3  259.03
 14377.3  287.52 14427.4  294.89 14527.5  307.63 14640.7  307.78 15471.4  294.42
#Mann= 20 ,-1 , 0
 -7361.9     .05       0   -7257     .12       0 -4129.4     .05       0
   -3971     .05       0 -2737.4     .07       0 -2628.6     .12       0
 -2519.8     .07       0 -2352.7     .07       0 -2193.5     .12       0
 -2064.9     .05       0  -670.3     .08       0  -561.5     .05       0
    2889     .05       0  5077.3     .03       0  5083.3     .05       0
 11674.9     .05       0 12495.7     .05       0   13960     .12       0
 14058.4     .16       0 14640.7     .05       0
#XS Ineff= 2 ,-1
-1068.18  2187.5  188.8711306.8214221.59  194.17
Permanent Ineff=
       T       T
Bank Sta=4894.9,5254.7
XS Rating Curve= 0 ,0
Exp/Cntr=0.3,0.1

Type RM Length L Ch R = 1 ,21228   ,5445,5445,5445
BEGIN DESCRIPTION:
Mapping XS 7d7a46f3
END DESCRIPTION:
XS GIS Cut Line= 4
      3735660.47     10510932.03      3734120.47     10500867.05
      3730765.47     10498502.05      3731315.37     10490143.62
#Sta/Elev= 30
 -8193.9  198.79 -7163.4   196.6 -1737.2  199.29  1828.4  195.06  3019.3  179.24
  4656.5  182.87  4778.8  176.81  4936.9  182.32  4993.3  175.48  5130.2   183.2
  6040.3  181.97  6285.3  192.38  6986.8  180.79 11646.8  189.46   12669  199.69
 12697.2  201.83 12859.5  222.41   13086  303.09 13179.6  312.02 13330.5   311.9
 13406.3  303.89 13520.9   279.5 13611.1  284.54 13721.3  268.57 13811.5  279.56
 13911.7  269.88 14003.9  291.06   14127  296.73 14301.6  311.55 14469.5  311.98
#Mann= 9 ,-1 , 0
 -8193.9     .12       0 -7163.4     .05       0  4656.5     .03       0
  5130.2     .05       0   12669     .05       0 12697.2     .16       0
 13179.6     .05       0 13406.3     .16       0   14127     .05       0
#XS Ineff= 2 ,-1
  640.96 4220.53  184.87 6447.2713292.55189.6397
Permanent Ineff=
       T       T
Bank Sta=4656.5,5130.2
XS Rating Curve= 0 ,0
Exp/Cntr=0.3,0.1

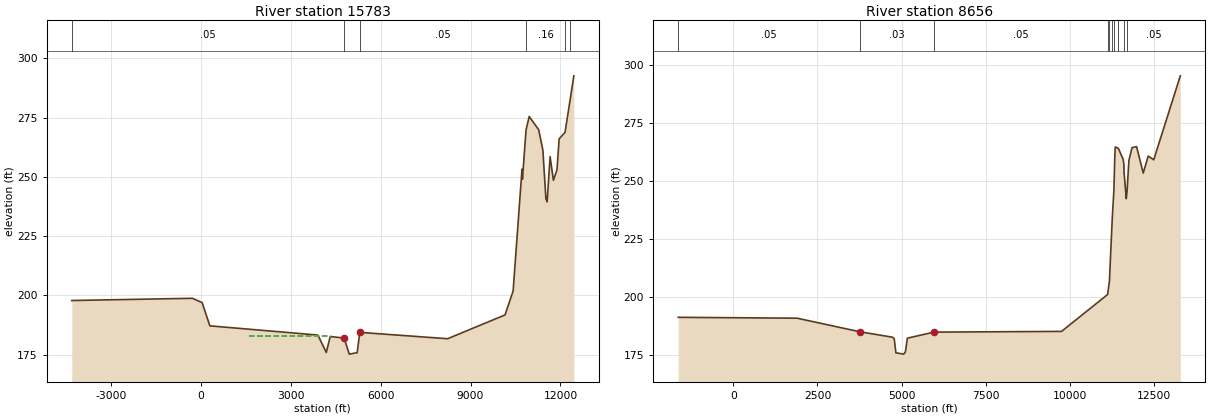
Type RM Length L Ch R = 1 ,15783   ,7127,7127,7127
BEGIN DESCRIPTION:
UPPER KEECHI CREEK 3.0
END DESCRIPTION:
XS GIS Cut Line= 3
      3736210.47     10506532.07      3735055.47     10496467.05
      3734499.61     10489860.17
#Sta/Elev= 30
 -4312.5  197.86  -284.4   198.8    39.9  196.96   297.3  187.17  3902.9  183.28
  4184.8  175.95  4315.6  182.67  4768.6  182.03  4773.6  182.24  4951.6  175.24
  5214.3  175.85  5303.5  184.42  8233.9  181.74 10150.7  191.77 10421.6  201.85
 10718.5  253.25 10732.7  249.06 10853.2  269.82 10958.2   275.5 11274.6  269.93
 11415.1   261.3 11515.5  240.85 11557.4  239.48   11656  258.57 11766.4  248.57
 11886.8  253.08   11957  266.05 12154.4  268.79 12319.1  282.09 12448.8  292.66
#Mann= 6 ,-1 , 0
 -4312.5     .05       0  4768.6     .03       0  5303.5     .05       0
 10853.2     .16       0 12154.4      .1       0 12319.1     .16       0
#XS Ineff= 1 ,-1
 1588.46  4310.6   182.8
Permanent Ineff=
       T
Bank Sta=4773.6,5303.5
XS Rating Curve= 0 ,0
Exp/Cntr=0.3,0.1

Type RM Length L Ch R = 1 ,8656    ,0,0,0
BEGIN DESCRIPTION:
UPPER KEECHI CREEK 2.0
END DESCRIPTION:
XS GIS Cut Line= 3
      3739840.47     10503122.08      3740335.47     10495367.05
      3735715.48     10489922.06
#Sta/Elev= 30
 -1634.9  191.19  1894.2  190.82  3757.9  184.97  4729.9  182.62    4780  181.94
  4830.1  175.88  5060.3  175.32  5110.7  176.24  5170.8   182.2  5961.4  184.81
  9749.5  185.12 11118.2  201.03 11171.2  206.77 11254.5  233.48 11304.2  245.94
 11331.2  260.58 11345.5  264.66   11437  264.03 11579.4  259.34 11600.6  257.18
 11606.3   253.6 11671.7  242.36 11695.6  245.64 11749.7  258.75 11841.9  264.34
 11977.1  264.82 12175.9  253.39 12324.1  260.73 12487.8  259.12 13276.8  295.33
#Mann= 10 ,-1 , 0
 -1634.9     .05       0  3757.9     .03       0  5961.4     .05       0
 11118.2     .12       0 11171.2     .16       0 11254.5     .12       0
 11304.2     .16       0   11437     .05       0 11606.3     .16       0
 11695.6     .05       0
Bank Sta=3757.9,5961.4
XS Rating Curve= 0 ,0
Exp/Cntr=0.3,0.1

Chan Stop Cuts=-1
Use User Specified Reach Order=0
Composite Channel Slope=5