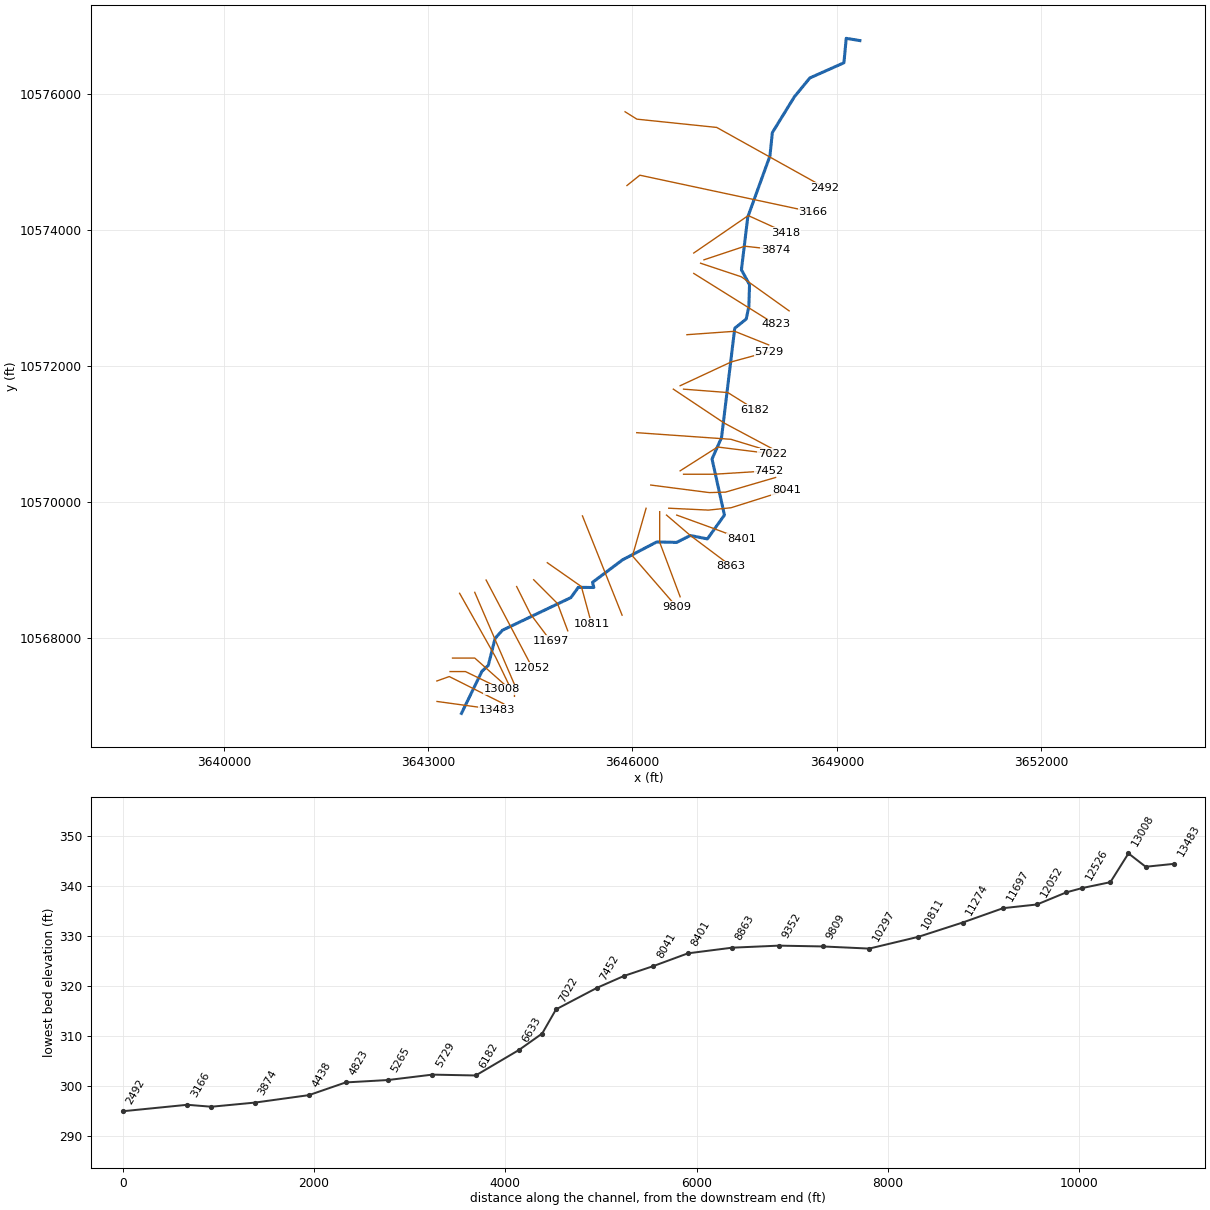
--- YARD BRANCH.prj (project) ---

Proj Title=YARD BRANCH Base Level Engineering
Current Plan=p01
Default Exp/Contr=0.3,0.1
English Units
Geom File=g01
Flow File=f01
Plan File=p01
Y Axis Title=Elevation
X Axis Title(PF)=Main Channel Distance
X Axis Title(XS)=Station
BEGIN DESCRIPTION:
YARD BRANCH
END DESCRIPTION:
DSS Export Rating Curves= 0
DSS Export Rating Curve Sorted= 0
DSS Export Volume Flow Curves= 0
DXF OffsetX= 0
DXF OffsetY= 0
DXF ScaleX= 1
DXF ScaleY= 10

--- YARD BRANCH.p01 (plan) ---

Plan Title=Multiple Run
Short Identifier=Multiple
Geom File=g01
Flow File=f01
Subcritical Flow
K Sum by GR= 0
Std Step Tol= 0.01
Critical Tol= 0.01
Num of Std Step Trials= 20
Max Error Tol= 0.3
Flow Tol Ratio= 0.001
Split Flow NTrial= 30
Split Flow Tol= 0.02
Split Flow Ratio= 0.02
Log Output Level= 0
Friction Slope Method= 1
Unsteady Friction Slope Method= 2
Unsteady Bridges Friction Slope Method= 1
Parabolic Critical Depth
Global Vel Dist=  1 , 1 , 1
Global Log Level= 0
CheckData=True
Encroach Param= -1, 0, 0, 0
BEGIN DESCRIPTION:
Multiple Run
END DESCRIPTION:

--- YARD BRANCH.f01 (steady flow) ---

Flow Title=Multiple
Program Version=4.10
Number of Profiles= 7
Profile Names=10-year,25-year,50-year,1pct_min,100-year,1pct_plu,500-year
River Rch & RM=YARD BRANCH,Reach-1         ,13483
    1127    1562    1925    1733    2344    3170    3462
River Rch & RM=YARD BRANCH,Reach-1         ,12526
    2007    2882    3638    3350    4530    6126    7019
River Rch & RM=YARD BRANCH,Reach-1         ,11697
    2007    2882    3638    3350    4530    6126    7019
River Rch & RM=YARD BRANCH,Reach-1         ,5729
    1950    2788    3509    3222    4358    5893    6724
Boundary for River Rch & Prof#=YARD BRANCH,Reach-1         , 1
Up Type= 0
Dn Type= 3
Dn Slope=0.005
Boundary for River Rch & Prof#=YARD BRANCH,Reach-1         , 2
Up Type= 0
Dn Type= 3
Dn Slope=0.005
Boundary for River Rch & Prof#=YARD BRANCH,Reach-1         , 3
Up Type= 0
Dn Type= 3
Dn Slope=0.005
Boundary for River Rch & Prof#=YARD BRANCH,Reach-1         , 4
Up Type= 0
Dn Type= 3
Dn Slope=0.005
Boundary for River Rch & Prof#=YARD BRANCH,Reach-1         , 5
Up Type= 0
Dn Type= 3
Dn Slope=0.005
Boundary for River Rch & Prof#=YARD BRANCH,Reach-1         , 6
Up Type= 0
Dn Type= 3
Dn Slope=0.005
Boundary for River Rch & Prof#=YARD BRANCH,Reach-1         , 7
Up Type= 0
Dn Type= 3
Dn Slope=0.005
DSS Import GetInterval= 0
DSS Import GetPeak= 0
DSS Import FillOption= 0

--- YARD BRANCH.g01 (geometry) ---

Geom Title=Existing Conditions
Program Version=4.10

River Reach=YARD BRANCH     ,Reach-1
Reach XY= 30
       3643489.5       10566897.        3643790.       10567515.
       3643883.5       10567603.        3643983.       10567999.
       3644090.5       10568118.        3645096.       10568598.
        3645205.       10568749.      3645432.25       10568746.
       3645413.5       10568822.        3645853.       10569152.
      3646354.75       10569415.      3646648.75       10569409.
      3646849.61     10569510.19      3647099.61     10569460.19
      3647349.61     10569810.19        3647168.       10570634.
       3647307.5       10570950.      3647501.25       10572555.
      3647669.25       10572690.      3647708.75       10572875.
        3647718.       10573195.      3647599.25       10573414.
       3647692.5       10574189.      3648017.75       10575086.
      3648053.25       10575429.      3648375.25       10575953.
      3648603.75       10576232.        3649104.       10576455.
      3649137.75       10576814.      3649337.75       10576781.

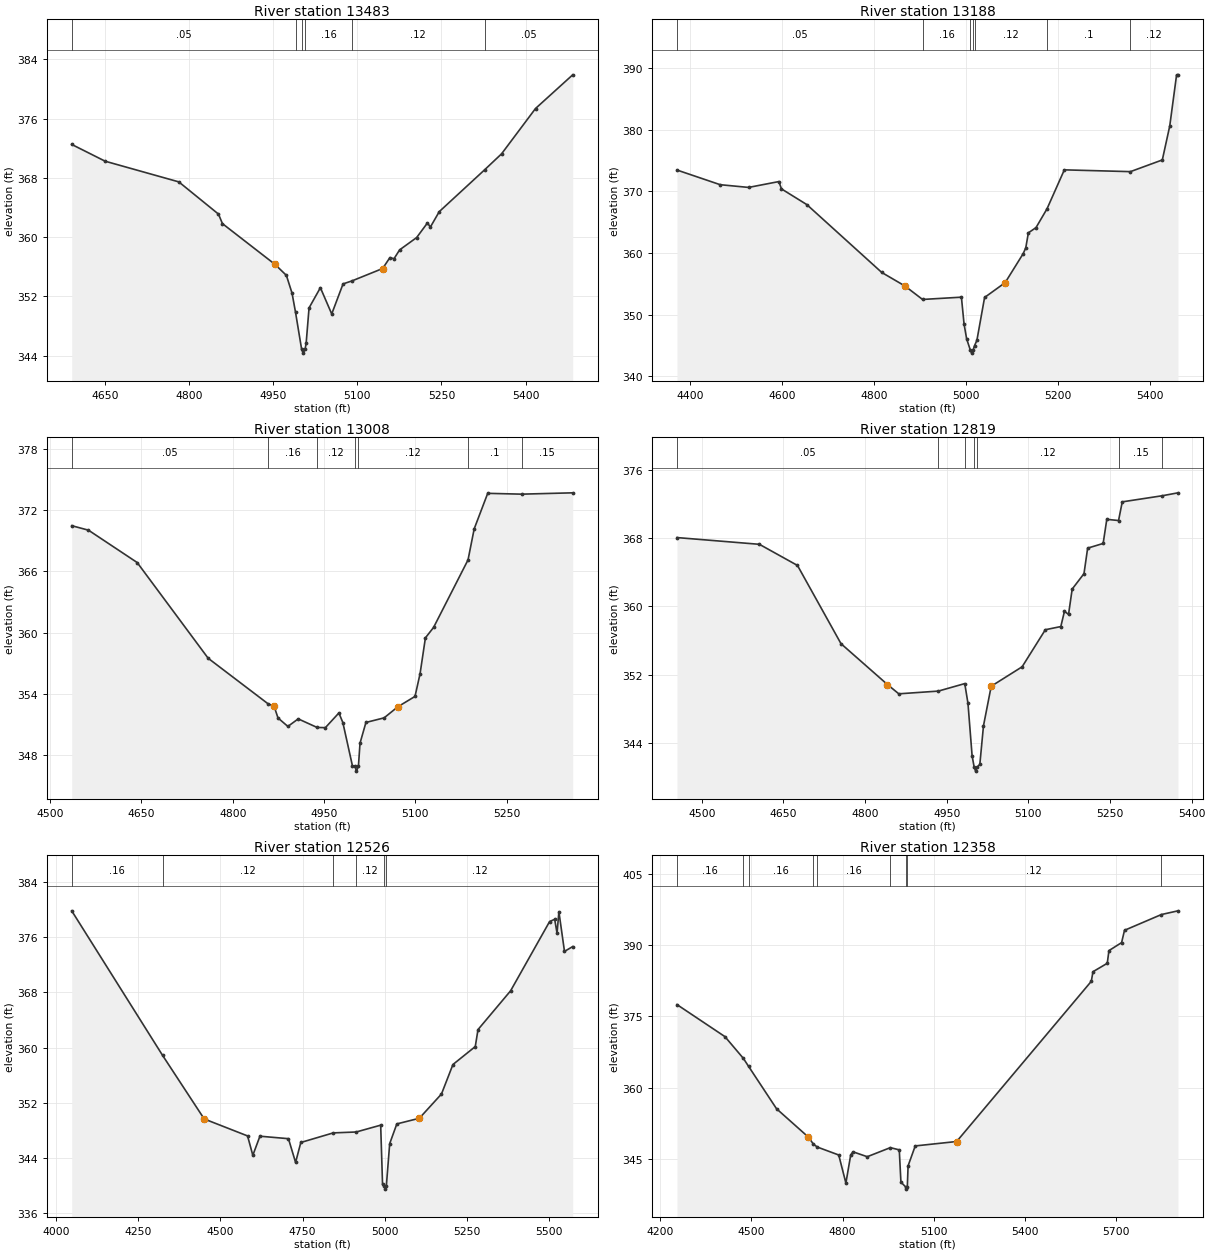
Type RM Length L Ch R = 1 ,13483   ,295,295,295
BEGIN DESCRIPTION:
YARD BRANCH 25.0
END DESCRIPTION:
XS GIS Cut Line= 2
      3643130.45       10567072.      3644015.25     10566950.56
#Sta/Elev= 30
  4590.8  372.52  4650.5  370.25  4781.7  367.46  4852.4  363.11  4859.5  361.82
  4953.3  356.31  4973.5  354.83  4983.6  352.42  4989.8  349.84  5000.7  344.83
  5003.4  344.33  5006.7  344.83  5008.7  345.64  5013.9  350.44  5034.1  353.17
  5054.3  349.62  5074.5  353.68  5090.2  354.08  5145.1  355.76    5158  357.23
  5165.3  357.08  5175.4  358.28  5205.7  359.94    5225  361.92  5230.1  361.35
    5246  363.44    5327   369.1  5357.1  371.25  5417.6  377.37  5483.9  381.92
#Mann= 6 ,-1 , 0
  4590.8     .05       0  4989.8     .16       0  5000.7     .07       0
  5006.7     .16       0  5090.2     .12       0    5327     .05       0
Bank Sta=4953.3,5145.1
XS Rating Curve= 0 ,0
Exp/Cntr=0.3,0.1

Type RM Length L Ch R = 1 ,13188   ,180,180,180
BEGIN DESCRIPTION:
Mapping XS 0ab61d9a
END DESCRIPTION:
XS GIS Cut Line= 3
      3643128.24     10567372.84      3643310.53     10567437.95
      3644110.02      10567036.9
#Sta/Elev= 30
    4372  373.46  4465.9  371.08  4527.5  370.64  4593.3  371.59  4598.9   370.4
    4654  367.85  4816.7  356.84  4866.9  354.65  4905.3  352.46  4989.7  352.83
  4995.4  348.49    5001  346.08    5009  344.25  5011.8  343.75    5015  344.25
  5018.2  344.96  5023.3  345.82    5040  352.78  5084.7  355.19  5123.8  359.89
  5129.4  360.82  5135.1  363.27  5151.7  364.12  5175.6  367.17  5213.2  373.49
  5356.7   373.2    5426   375.1  5442.1   380.6    5457  388.91    5460  388.91
#Mann= 7 ,-1 , 0
    4372     .05       0  4905.3     .16       0    5009     .07       0
    5015     .16       0  5018.2     .12       0  5175.6      .1       0
  5356.7     .12       0
Bank Sta=4866.9,5084.7
XS Rating Curve= 0 ,0
Exp/Cntr=0.3,0.1

Type RM Length L Ch R = 1 ,13008   ,189,189,189
BEGIN DESCRIPTION:
Mapping XS a3163fc4
END DESCRIPTION:
XS GIS Cut Line= 3
      3643322.08      10567511.3      3643547.73      10567511.3
      3644085.26      10567251.2
#Sta/Elev= 30
  4535.5  370.47    4563  370.03    4643  366.86  4759.6  357.48  4857.7  353.03
  4867.9  352.77  4874.3  351.63  4890.5   350.8  4907.5  351.54  4938.5   350.7
  4952.1  350.68  4974.3  352.12  4980.8  351.18  4996.5  346.95  5000.4  346.92
  5003.2  346.42  5006.4  346.92    5009  349.16  5018.7  351.19  5048.6  351.64
  5071.2  352.73  5099.3  353.74  5107.6  355.96  5116.4  359.48  5129.8   360.5
  5186.4  367.12  5196.5  370.16  5218.7  373.64  5274.4  373.56  5358.3  373.69
#Mann= 7 ,-1 , 0
  4535.5     .05       0  4857.7     .16       0  4938.5     .12       0
  5000.4     .07       0  5006.4     .12       0  5186.4      .1       0
  5274.4     .15       0
Bank Sta=4867.9,5071.2
XS Rating Curve= 0 ,0
Exp/Cntr=0.3,0.1

Type RM Length L Ch R = 1 ,12819   ,293,293,293
BEGIN DESCRIPTION:
Mapping XS a9f00e6a
END DESCRIPTION:
XS GIS Cut Line= 3
      3643358.18     10567709.79      3643684.59     10567709.79
      3644128.31      10567314.6
#Sta/Elev= 30
  4454.3  368.07  4605.7  367.28  4675.7   364.8  4755.7  355.62    4841  350.83
  4861.9  349.74  4934.6  350.06  4983.1  350.94    4989  348.62  4996.6  342.46
  5000.3  341.17    5003  340.67  5006.3  341.17  5010.8  341.46  5017.5  345.99
  5031.7  350.63  5088.5  352.91  5131.2  357.26  5159.6  357.63  5166.3  359.42
  5173.8  359.06  5180.5  362.03  5202.2  363.84  5208.9  366.83  5237.4  367.38
  5244.1  370.21  5265.7  370.07  5272.5  372.26  5346.2  372.98  5374.9  373.32
#Mann= 7 ,-1 , 0
  4454.3     .05       0  4934.6     .16       0  4983.1     .12       0
  5000.3     .07       0  5006.3     .12       0  5265.7     .15       0
  5346.2     .12       0
Bank Sta=4841,5031.7
XS Rating Curve= 0 ,0
Exp/Cntr=0.3,0.1

Type RM Length L Ch R = 1 ,12526   ,168,168,168
BEGIN DESCRIPTION:
Mapping XS 999779e4
END DESCRIPTION:
XS GIS Cut Line= 3
      3643462.38     10568661.15      3643990.14     10567723.68
       3644184.6     10567320.88
#Sta/Elev= 30
    4048  379.83    4324   358.9  4450.8  349.67  4582.6  347.21  4598.6   344.4
  4620.2  347.17  4706.9  346.81  4728.6  343.37  4744.5  346.26  4843.2  347.65
  4912.9  347.78  4987.3  348.77    4993  340.18  4998.6     340  5001.3   339.5
  5004.6     340  5014.7  346.09  5036.4  348.95  5104.9  349.77  5172.1  353.28
    5207  357.56  5274.9  360.16  5283.2  362.62  5382.3  368.24  5500.9  378.28
  5516.3   378.6  5523.5  376.59  5529.1  379.71  5546.1  373.95  5571.1  374.65
#Mann= 6 ,-1 , 0
    4048     .16       0    4324     .12       0  4843.2     .16       0
  4912.9     .12       0  4998.6     .07       0  5004.6     .12       0
Bank Sta=4450.8,5104.9
XS Rating Curve= 0 ,0
Exp/Cntr=0.3,0.1

Type RM Length L Ch R = 1 ,12358   ,306,306,306
BEGIN DESCRIPTION:
Mapping XS 946789c5
END DESCRIPTION:
XS GIS Cut Line= 3
       3643684.6     10568675.04      3644267.92      10567320.9
      3644267.92     10567147.33
#Sta/Elev= 30
    4255  377.46  4412.7  370.72  4473.5  366.13  4490.3  364.48  4582.5  355.54
  4687.5  349.56  4703.8  348.09  4716.7  347.48  4787.1  345.81  4810.6   339.9
  4826.5  345.83  4834.1  346.48  4880.9  345.45  4956.8  347.36  4986.2  346.89
  4991.6  340.11  5006.7  339.13  5009.5  338.63  5012.7  339.13  5015.2  343.53
  5038.7  347.72  5174.9  348.65  5617.9  382.36  5623.4  384.38  5670.4  386.15
  5675.9  388.82  5717.5   390.5  5727.1  393.09  5848.5  396.41    5903  397.19
#Mann= 9 ,-1 , 0
    4255     .16       0  4473.5     .12       0  4490.3     .16       0
  4703.8     .12       0  4716.7     .16       0  4956.8     .12       0
  5006.7     .07       0  5012.7     .12       0  5848.5     .05       0
Bank Sta=4687.5,5174.9
XS Rating Curve= 0 ,0
Exp/Cntr=0.3,0.1

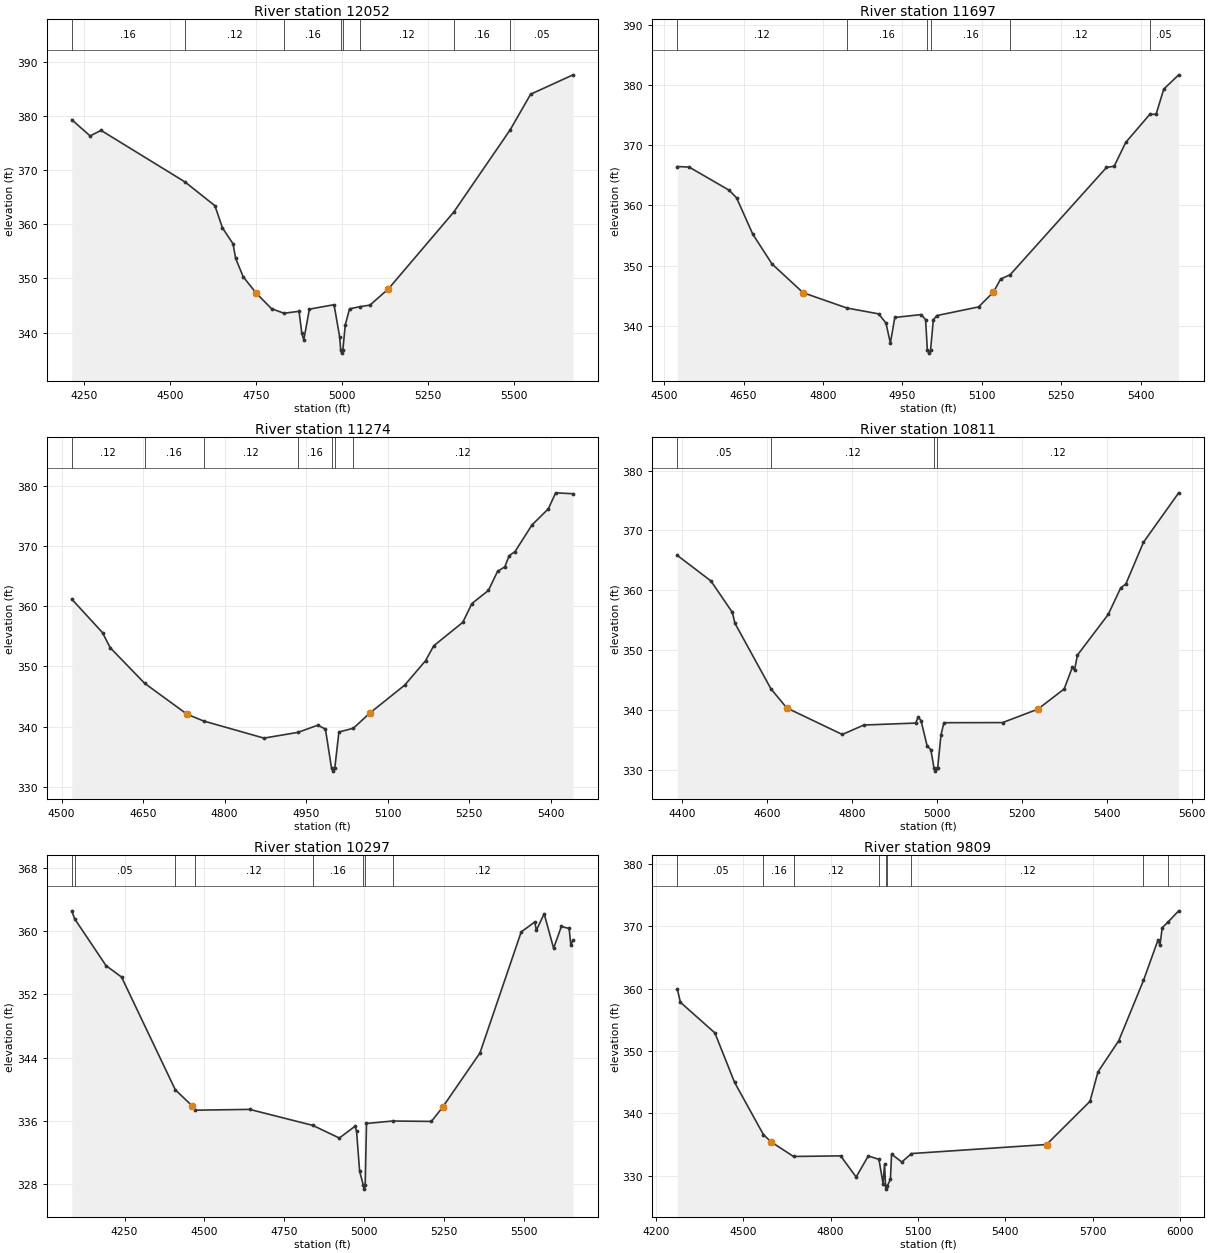
Type RM Length L Ch R = 1 ,12052   ,355,355,355
BEGIN DESCRIPTION:
YARD BRANCH 24.0
END DESCRIPTION:
XS GIS Cut Line= 2
      3643851.25     10568855.64      3644531.48     10567564.58
#Sta/Elev= 30
  4213.4   379.3    4267   376.3  4298.7  377.33  4543.1  367.81  4630.2  363.42
  4652.2  359.33    4683  356.38  4690.6  353.68  4712.6   350.3  4750.8  347.25
  4795.1  344.41  4831.3  343.57  4875.1  343.93  4883.2  339.85  4888.9  338.64
  4905.2  344.33    4977  345.15  4993.4  339.18  4996.5  336.71  4999.2  336.21
  5002.5  336.71  5009.7   341.4  5022.1  344.39  5051.4  344.77  5081.5  345.08
  5135.1  348.06  5325.6  362.26    5490  377.46  5549.2     384  5672.7  387.58
#Mann= 8 ,-1 , 0
  4213.4     .16       0  4543.1     .12       0  4831.3     .16       0
  4996.5     .07       0  5002.5     .16       0  5051.4     .12       0
  5325.6     .16       0    5490     .05       0
Bank Sta=4750.8,5135.1
XS Rating Curve= 0 ,0
Exp/Cntr=0.3,0.1

Type RM Length L Ch R = 1 ,11697   ,423,423,423
BEGIN DESCRIPTION:
YARD BRANCH 23.0
END DESCRIPTION:
XS GIS Cut Line= 3
      3644299.59     10568760.23      3644499.61     10568360.19
      3644799.63     10567960.16
#Sta/Elev= 30
  4524.7  366.45  4547.1  366.35  4622.6  362.51  4636.6  361.25  4667.3   355.2
  4703.6  350.27  4762.3   345.5  4845.1  342.96  4904.9  341.99  4918.9  340.47
  4927.2  337.14  4935.6  341.39  4985.5  341.87  4993.8  341.01  4997.1  335.97
  4999.8  335.47  5003.1  335.97  5008.4  340.99  5014.7   341.7  5093.8  343.14
    5122   345.6  5135.5  347.76  5153.7   348.5  5335.5  366.29  5350.1   366.5
    5372  370.46  5417.4  375.11  5429.3  375.12  5443.8   379.3    5472  381.67
#Mann= 6 ,-1 , 0
  4524.7     .12       0  4845.1     .16       0  4997.1     .07       0
  5003.1     .16       0  5153.7     .12       0  5417.4     .05       0
Bank Sta=4762.3,5122
XS Rating Curve= 0 ,0
Exp/Cntr=0.3,0.1

Type RM Length L Ch R = 1 ,11274   ,463,463,463
BEGIN DESCRIPTION:
YARD BRANCH 22.0
END DESCRIPTION:
XS GIS Cut Line= 3
      3644549.59     10568860.21      3644899.61     10568510.19
      3645049.61     10568110.19
#Sta/Elev= 30
  4518.8  361.15  4575.4  355.59  4589.5  353.09  4652.9  347.18    4731  342.04
  4761.4  340.92  4872.4  338.08  4934.7  339.03  4971.4  340.22  4985.5  339.58
  4996.7   333.1  4999.4   332.6  5002.7   333.1  5010.3  339.09  5036.9  339.72
  5067.2  342.24  5131.3  346.87  5169.6  350.92  5184.7   353.4  5238.1  357.29
    5255  360.42  5285.3  362.59  5302.2  365.76  5315.5  366.51  5323.5  368.36
  5334.2  369.03  5365.4  373.45  5395.6  376.14    5409  378.79    5441  378.64
#Mann= 7 ,-1 , 0
  4518.8     .12       0  4652.9     .16       0  4761.4     .12       0
  4934.7     .16       0  4996.7     .07       0  5002.7     .16       0
  5036.9     .12       0
Bank Sta=4731,5067.2
XS Rating Curve= 0 ,0
Exp/Cntr=0.3,0.1

Type RM Length L Ch R = 1 ,10811   ,514,514,514
BEGIN DESCRIPTION:
YARD BRANCH 21.0
END DESCRIPTION:
XS GIS Cut Line= 3
      3644749.62     10569110.18      3645249.61     10568760.19
      3645399.61     10568210.19
#Sta/Elev= 30
  4389.1  365.82    4468  361.56  4518.6   356.3  4524.7  354.47  4609.4  343.51
  4646.7  340.31  4777.5  335.87  4828.1  337.45  4950.1  337.78  4956.2  338.78
  4962.8   338.2  4977.2  333.96  4985.9  333.33  4993.4  330.24  4996.1  329.74
  4999.4  330.24    5002  330.24  5009.8  335.79  5016.7  337.84  5154.9  337.86
  5237.8   340.1    5300  343.49    5319   347.1  5324.2  346.62  5331.1  349.15
  5403.7  355.96    5433   360.4  5445.1  361.05  5486.6  368.02  5569.5  376.29
#Mann= 4 ,-1 , 0
  4389.1     .05       0  4609.4     .12       0  4993.4     .07       0
  4999.4     .12       0
Bank Sta=4646.7,5237.8
XS Rating Curve= 0 ,0
Exp/Cntr=0.3,0.1

Type RM Length L Ch R = 1 ,10297   ,488,488,488
BEGIN DESCRIPTION:
YARD BRANCH 20.0
END DESCRIPTION:
XS GIS Cut Line= 2
      3645265.84     10569797.66      3645847.43     10568339.36
#Sta/Elev= 30
  4084.6  362.57  4093.9  361.55  4192.1  355.64  4240.6   354.2  4408.9  339.95
  4461.6  337.92  4472.2  337.37  4641.7  337.47  4839.3  335.45  4922.6  333.85
  4971.1  335.32  4976.5  334.78  4986.2  329.66  4997.7  327.89  5000.5  327.39
  5003.7  327.89  5007.7  335.69  5089.3     336    5211  335.95    5246  337.74
    5363   344.6  5492.2   359.9  5534.5  361.16  5539.8  360.12  5564.1   362.2
  5593.7  357.84    5618  360.59  5642.3  360.34  5647.7  358.24  5654.6  358.87
#Mann= 8 ,-1 , 0
  4084.6      .1       0  4093.9     .05       0  4408.9     .16       0
  4472.2     .12       0  4839.3     .16       0  4997.7     .07       0
  5003.7     .16       0  5089.3     .12       0
Bank Sta=4461.6,5246
XS Rating Curve= 0 ,0
Exp/Cntr=0.3,0.1

Type RM Length L Ch R = 1 ,9809    ,457,457,457
BEGIN DESCRIPTION:
YARD BRANCH 19.0
END DESCRIPTION:
XS GIS Cut Line= 3
       3646199.6     10569910.16      3645999.61     10569210.19
      3646649.64     10568460.15
#Sta/Elev= 30
  4274.1  359.91  4284.5  357.81  4402.8   352.9  4470.4  344.96  4569.7  336.55
  4596.5  335.38  4672.8  333.06  4834.4  333.16  4887.7  329.76  4929.3  333.14
  4965.9   332.6    4980  328.72  4985.2  331.81  4988.7  328.32  4991.4  327.82
  4994.7  328.32  5005.4  329.42  5009.2  333.44  5044.3  332.17  5077.5  333.53
  5541.1  334.98  5690.2  341.91  5717.7  346.64  5788.9  351.64  5873.8  361.32
  5923.8  367.82  5930.4  366.98  5938.1  369.78  5957.1  370.65  5994.6  372.49
#Mann= 9 ,-1 , 0
  4274.1     .05       0  4569.7     .16       0  4672.8     .12       0
  4965.9     .16       0  4988.7     .07       0  4994.7     .16       0
  5077.5     .12       0  5873.8     .16       0  5957.1     .05       0
Bank Sta=4596.5,5541.1
XS Rating Curve= 0 ,0
Exp/Cntr=0.3,0.1

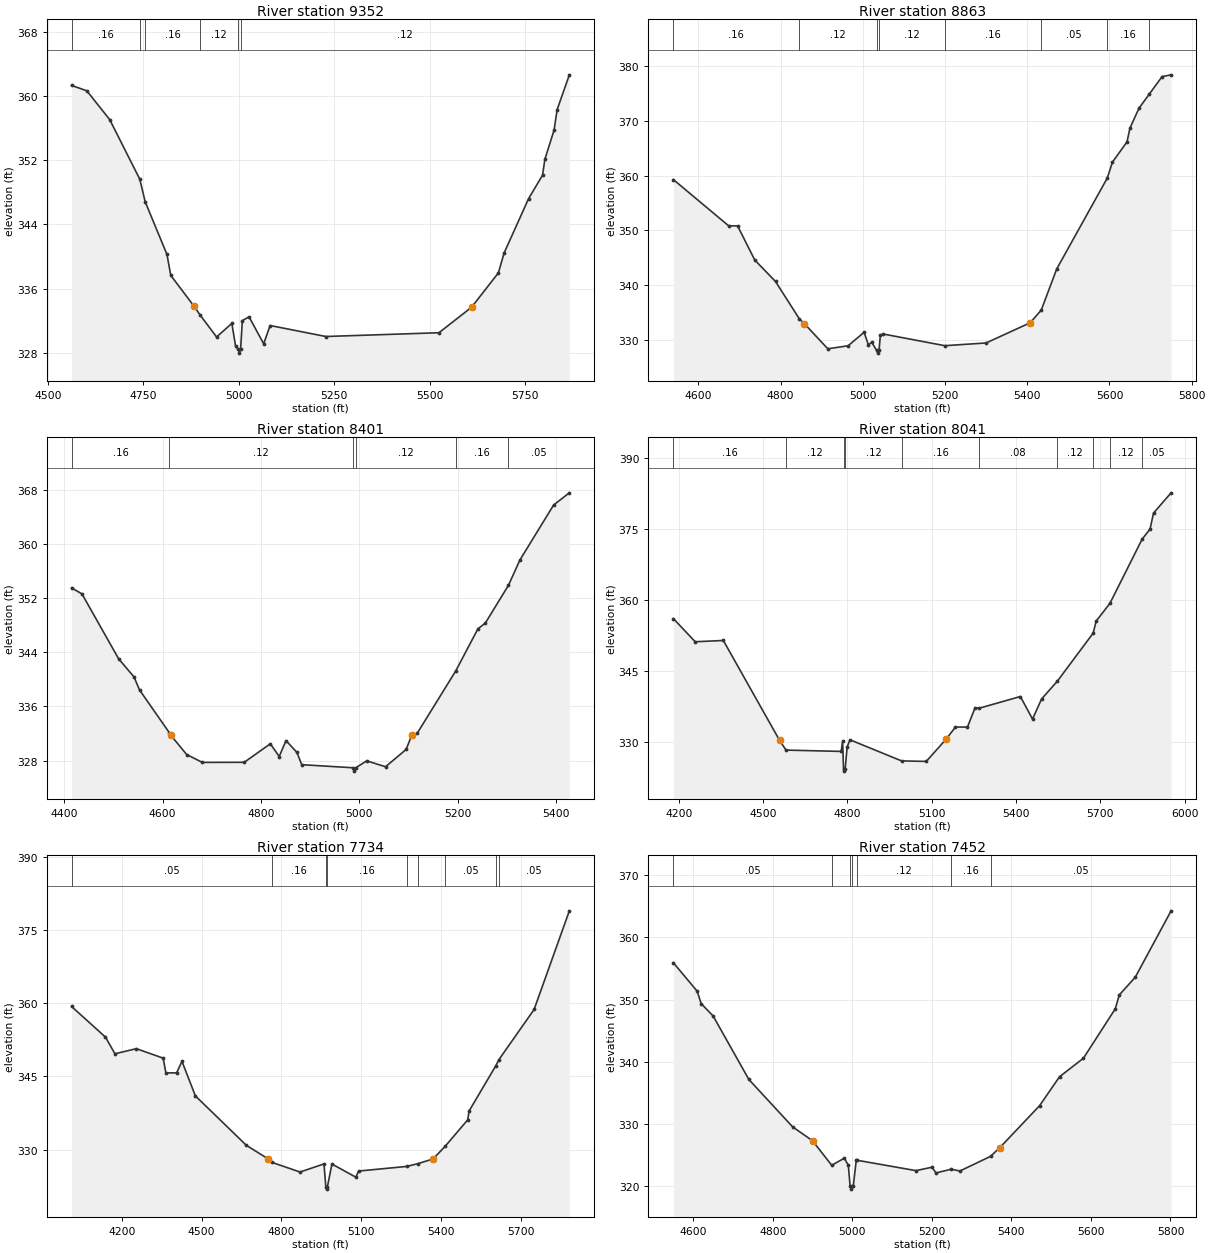
Type RM Length L Ch R = 1 ,9352    ,489,489,489
BEGIN DESCRIPTION:
YARD BRANCH 18.0
END DESCRIPTION:
XS GIS Cut Line= 3
      3646399.61      10569860.2      3646399.61     10569410.19
       3646699.6      10568610.2
#Sta/Elev= 30
  4561.7  361.32  4601.7  360.65  4661.7  357.06  4740.5  349.64  4754.6  346.83
  4811.7  340.27  4821.7  337.66  4881.7  333.88    4899   332.7  4941.7  329.99
  4981.7  331.68  4991.7  328.81  4998.7  328.48  5001.5  327.98  5004.7  328.48
  5009.2  332.03  5026.8   332.5  5065.1  329.14    5082  331.42    5228  330.05
  5524.4  330.52  5609.8  333.69  5680.1  337.97  5695.2  340.46  5759.3  347.22
  5795.8  350.14    5802  352.13  5826.1  355.76  5834.1   358.3  5866.1  362.64
#Mann= 6 ,-1 , 0
  4561.7     .16       0  4740.5     .12       0  4754.6     .16       0
    4899     .12       0  4998.7     .07       0  5004.7     .12       0
Bank Sta=4881.7,5609.8
XS Rating Curve= 0 ,0
Exp/Cntr=0.3,0.1

Type RM Length L Ch R = 1 ,8863    ,462,462,462
BEGIN DESCRIPTION:
YARD BRANCH 17.0
END DESCRIPTION:
XS GIS Cut Line= 3
      3646499.59      10569810.2      3646849.61     10569510.19
      3647449.61     10569060.19
#Sta/Elev= 30
    4539  359.31  4673.5  350.86  4695.4  350.83  4737.1   344.6  4787.6  340.67
  4845.6  333.84  4857.9  332.95  4914.9  328.36  4964.3  328.92  5003.1  331.38
  5013.5   329.1  5021.9  329.54  5033.5  328.07  5036.2  327.57  5039.5  328.07
  5042.7  330.81    5050  331.06  5199.5  328.93    5300  329.43  5407.3  333.13
  5434.1  335.44  5471.9  342.99  5594.8  359.59  5607.3   362.5  5642.7   366.2
    5650  368.74  5671.9  372.36  5697.1  374.95  5728.1  378.14    5750  378.46
#Mann= 8 ,-1 , 0
    4539     .16       0  4845.6     .12       0  5033.5     .07       0
  5039.5     .12       0  5199.5     .16       0  5434.1     .05       0
  5594.8     .16       0  5697.1     .05       0
Bank Sta=4857.9,5407.3
XS Rating Curve= 0 ,0
Exp/Cntr=0.3,0.1

Type RM Length L Ch R = 1 ,8401    ,360,360,360
BEGIN DESCRIPTION:
YARD BRANCH 16.0
END DESCRIPTION:
XS GIS Cut Line= 3
      3646649.64     10569810.18      3647199.61     10569610.19
      3647599.61     10569460.19
#Sta/Elev= 30
  4414.8  353.52    4436  352.62  4510.5  343.04  4541.8  340.36  4553.1  338.43
  4613.7  332.11  4616.9  331.72  4648.9  328.89  4680.8  327.73  4765.9  327.74
  4819.1  330.48  4837.1   328.6    4851  330.95    4873  329.22    4883  327.39
    4987  326.94  4989.8  326.44    4993  326.94  5015.1  327.96  5053.4  327.09
  5095.2  329.64  5106.8  331.77  5117.5     332  5196.2  341.25  5241.2  347.46
  5256.3  348.31  5303.4   353.9  5326.6  357.63  5395.2  365.76  5427.2  367.56
#Mann= 6 ,-1 , 0
  4414.8     .16       0  4613.7     .12       0    4987     .07       0
    4993     .12       0  5196.2     .16       0  5303.4     .05       0
Bank Sta=4616.9,5106.8
XS Rating Curve= 0 ,0
Exp/Cntr=0.3,0.1

Type RM Length L Ch R = 1 ,8041    ,307,307,307
BEGIN DESCRIPTION:
YARD BRANCH 15.0
END DESCRIPTION:
XS GIS Cut Line= 4
      3646531.84     10569911.18      3647115.14      10569883.4
      3647448.48     10569918.12      3648261.01     10570175.08
#Sta/Elev= 30
  4180.3  356.11  4258.2  351.21  4358.3  351.48  4558.5  330.39  4581.3  328.34
  4777.7  328.06  4782.7  330.19  4785.9   324.4  4788.6   323.9  4791.9   324.4
  4798.9  329.03    4809  330.51  4992.5  326.06  5080.4  325.95  5151.9  330.71
  5184.2  333.21    5227   333.2  5254.1  337.29  5268.9  337.18  5415.2  339.65
  5458.5  334.89  5490.8  339.14  5546.7  342.88  5674.5  353.05  5684.7  355.55
    5734  359.33  5848.5  372.87  5876.7     375    5889  378.38  5951.6  382.65
#Mann= 10 ,-1 , 0
  4180.3     .16       0  4581.3     .12       0  4785.9     .07       0
  4791.9     .12       0  4992.5     .16       0  5268.9     .08       0
  5546.7     .12       0  5674.5     .08       0    5734     .12       0
  5848.5     .05       0
Bank Sta=4558.5,5151.9
XS Rating Curve= 0 ,0
Exp/Cntr=0.3,0.1

Type RM Length L Ch R = 1 ,7734    ,282,282,282
BEGIN DESCRIPTION:
Mapping XS e800f95a
END DESCRIPTION:
XS GIS Cut Line= 4
       3646267.9     10570251.46      3647129.03     10570140.34
      3647365.14     10570147.29      3648101.23     10570362.56
#Sta/Elev= 30
  4011.1  359.33  4138.6  353.06  4174.1  349.65  4254.8  350.69  4355.6  348.75
  4365.7  345.72  4406.1  345.74  4426.2  348.09  4476.6  341.02  4668.2   330.9
  4748.9  328.16  4765.1   327.4  4869.9  325.43    4960  327.09    4967  322.43
  4969.7  321.93    4973  322.43    4990  327.07    5080  324.37    5090  325.63
  5271.5  326.58  5313.8  327.16  5370.3  328.11  5415.6   330.7  5500.3  336.11
  5505.7  337.94  5606.2  347.21  5617.6  348.44    5750  358.72  5882.5  378.92
#Mann= 9 ,-1 , 0
  4011.1     .05       0  4765.1     .16       0    4967     .07       0
    4973     .16       0  5271.5     .12       0  5313.8     .16       0
  5415.6     .05       0  5606.2     .16       0  5617.6     .05       0
Bank Sta=4748.9,5370.3
XS Rating Curve= 0 ,0
Exp/Cntr=0.3,0.1

Type RM Length L Ch R = 1 ,7452    ,430,430,430
BEGIN DESCRIPTION:
YARD BRANCH 14.0
END DESCRIPTION:
XS GIS Cut Line= 3
      3646749.61     10570410.19      3647199.61     10570410.19
      3647999.65     10570460.19
#Sta/Elev= 30
    4550  355.93    4610  351.35    4620  349.36    4650  347.38    4740  337.17
    4850  329.56    4900  327.33  4948.3  323.39    4980  324.53    4990   323.4
  4994.5  320.06  4997.3  319.56  5000.5  320.06  5002.5  320.06    5010  324.21
  5012.7  324.19  5160.3  322.53  5200.4  323.08  5210.4  322.16  5248.7  322.76
  5270.5  322.47  5347.5  324.82  5370.7  326.21  5470.9  332.96    5521  337.61
  5581.1  340.58  5661.3  348.53  5671.3  350.75  5711.4  353.59  5801.6  364.26
#Mann= 7 ,-1 , 0
    4550     .05       0  4948.3     .16       0  4994.5     .07       0
  5000.5     .16       0  5012.7     .12       0  5248.7     .16       0
  5347.5     .05       0
Bank Sta=4900,5370.7
XS Rating Curve= 0 ,0
Exp/Cntr=0.3,0.1

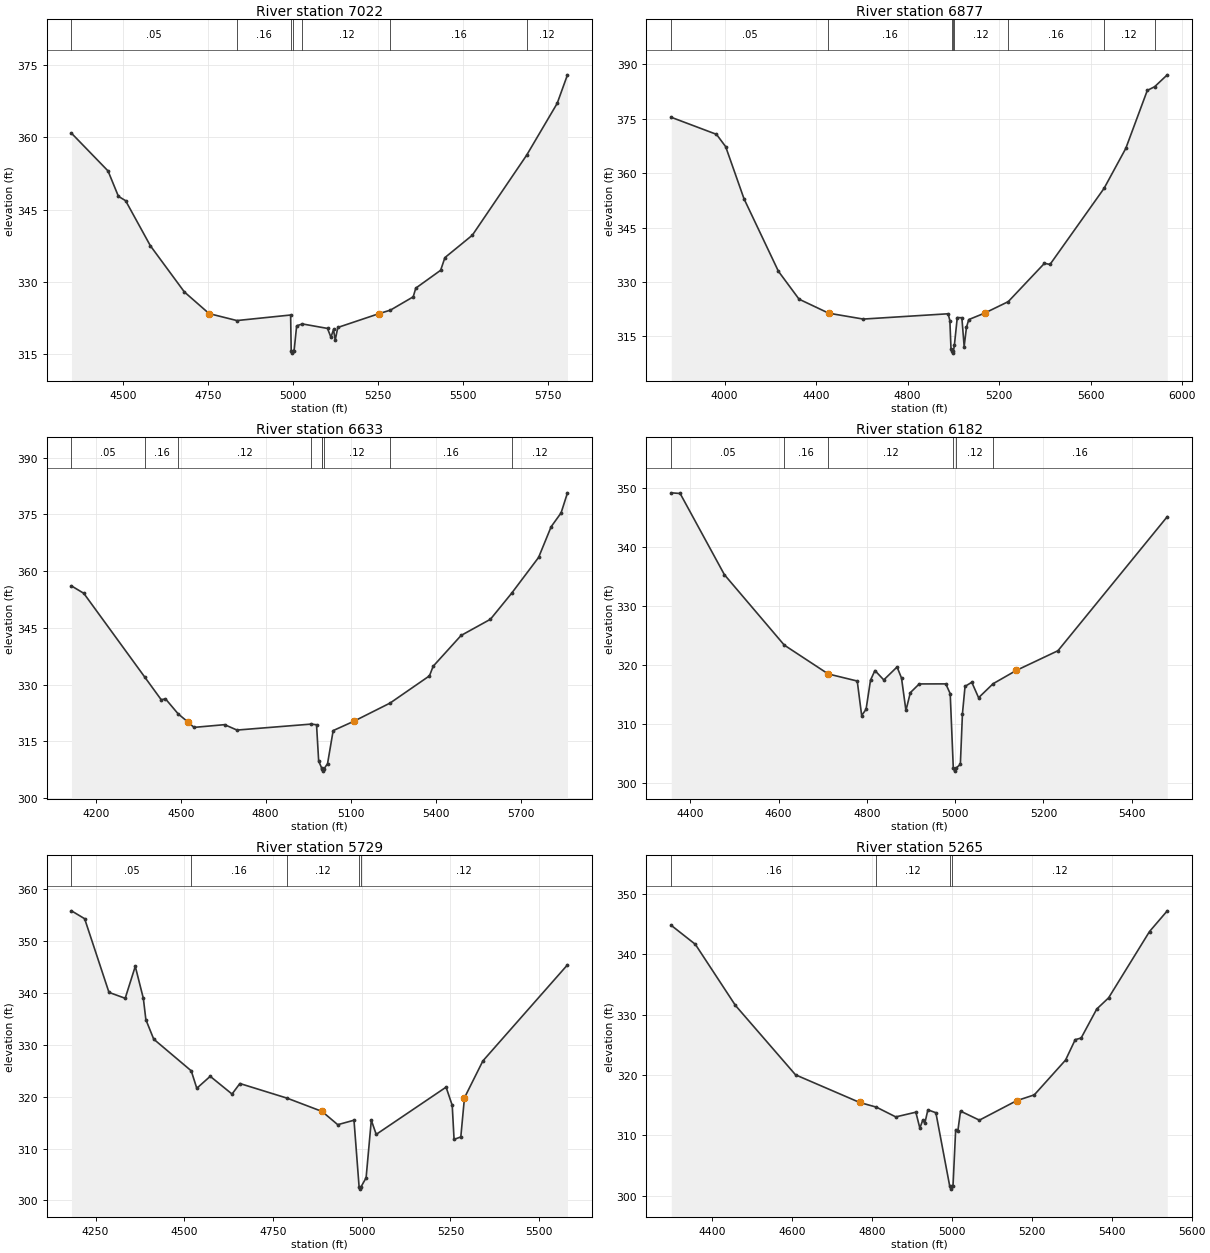
Type RM Length L Ch R = 1 ,7022    ,145,145,145
BEGIN DESCRIPTION:
YARD BRANCH 13.0
END DESCRIPTION:
XS GIS Cut Line= 3
      3646699.59     10570460.18      3647249.61     10570810.19
      3648049.64     10570710.18
#Sta/Elev= 30
  4348.6  360.82  4456.1     353  4486.6  347.74  4507.8  346.83  4580.6  337.49
  4680.5  327.92  4753.3  323.43  4834.9  321.99  4992.9  323.14  4994.6  315.74
  4997.3  315.24  5000.6  315.74  5003.1  315.74  5010.6   320.9  5027.5  321.29
  5101.3  320.36  5111.4  318.53    5119  320.14    5124  317.95  5131.6  320.56
  5252.5  323.42  5286.2  324.15  5353.3  326.91  5360.8  328.71  5433.9  332.41
  5446.5  335.04  5527.1  339.68  5686.8  356.27  5776.5     367  5806.8  372.92
#Mann= 7 ,-1 , 0
  4348.6     .05       0  4834.9     .16       0  4994.6     .07       0
  5000.6     .16       0  5027.5     .12       0  5286.2     .16       0
  5686.8     .12       0
Bank Sta=4753.3,5252.5
XS Rating Curve= 0 ,0
Exp/Cntr=0.3,0.1

Type RM Length L Ch R = 1 ,6877    ,244,244,244
BEGIN DESCRIPTION:
Mapping XS ffe2c99f
END DESCRIPTION:
XS GIS Cut Line= 3
      3646062.35     10571020.84       3647444.3     10570923.62
      3648193.06     10570694.83
#Sta/Elev= 30
  3766.6  375.42  3964.3  370.72  4004.4  367.33  4084.6  352.96    4235  332.97
  4325.2  325.28  4453.2  321.46  4455.6   321.4  4605.9  319.79  4976.8  321.25
  4984.5  319.39  4989.5   311.5  4993.9   310.9  4996.6   310.4  4999.9   310.9
  5004.2  312.53  5016.9  320.21    5037  320.15    5047  312.21    5057  317.48
  5067.1  319.65  5137.2  321.45  5239.8   324.6    5398  335.16  5422.3  334.85
  5658.4  355.81  5753.5  366.84  5847.6  382.83  5879.8  383.86  5934.9  387.13
#Mann= 8 ,-1 , 0
  3766.6     .05       0  4453.2     .16       0  4993.9     .07       0
  4999.9     .16       0  5004.2     .12       0  5239.8     .16       0
  5658.4     .12       0  5879.8     .05       0
Bank Sta=4455.6,5137.2
XS Rating Curve= 0 ,0
Exp/Cntr=0.3,0.1

Type RM Length L Ch R = 1 ,6633    ,451,451,451
BEGIN DESCRIPTION:
YARD BRANCH 12.0
END DESCRIPTION:
XS GIS Cut Line= 3
      3646599.64     10571660.16      3647349.61     10571160.19
      3648099.57     10570760.21
#Sta/Elev= 30
  4114.3  356.09  4157.8  354.13  4372.8     332  4431.2  325.98  4446.3  326.22
  4491.3  322.22  4524.4  320.17  4546.9  318.67  4655.1  319.39  4698.7  317.96
  4960.7  319.54  4979.6  319.37  4987.1  309.76  4998.2  307.83  4999.1   307.6
  5001.9   307.1  5005.1   307.6  5018.5  309.09  5038.3  317.82  5111.6   320.3
  5239.4  325.11  5378.3   332.3  5391.4  334.84  5489.9  342.98  5593.6  347.27
  5668.5  354.16  5763.6  363.62  5807.9  371.74    5843   375.4  5865.6  380.71
#Mann= 9 ,-1 , 0
  4114.3     .05       0  4372.8     .16       0  4491.3     .12       0
  4960.7     .16       0  4998.2     .12       0  4999.1     .07       0
  5005.1     .12       0  5239.4     .16       0  5668.5     .12       0
Bank Sta=4524.4,5111.6
XS Rating Curve= 0 ,0
Exp/Cntr=0.3,0.1

Type RM Length L Ch R = 1 ,6182    ,453,453,453
BEGIN DESCRIPTION:
YARD BRANCH 11.0
END DESCRIPTION:
XS GIS Cut Line= 3
      3646749.58     10571660.19      3647399.61     10571610.19
      3647799.57     10571360.22
#Sta/Elev= 30
  4356.9   349.1    4377  348.99  4477.3  335.25  4612.9  323.34  4712.4  318.46
  4778.2  317.26  4788.2  311.43  4798.2  312.48  4808.3  317.42  4818.3  319.04
  4838.3  317.45  4868.4  319.64  4878.5  317.76  4888.5  312.28  4898.5   315.3
  4918.6  316.77  4978.8  316.78  4988.8  315.12  4995.8  302.52  4998.6  302.02
  5001.8  302.52  5011.8  303.17  5016.5  311.72  5022.4  316.36  5037.7  317.05
  5053.1  314.44    5086  316.81  5138.6  319.06  5232.9  322.39  5480.5  345.07
#Mann= 6 ,-1 , 0
  4356.9     .05       0  4612.9     .16       0  4712.4     .12       0
  4995.8     .07       0  5001.8     .12       0    5086     .16       0
Bank Sta=4712.4,5138.6
XS Rating Curve= 0 ,0
Exp/Cntr=0.3,0.1

Type RM Length L Ch R = 1 ,5729    ,464,464,464
BEGIN DESCRIPTION:
YARD BRANCH 10.0
END DESCRIPTION:
XS GIS Cut Line= 3
      3646699.58     10571710.17      3647449.61     10572060.19
      3647999.64      10572210.2
#Sta/Elev= 30
  4182.2  355.87  4219.3  354.35  4287.9  340.14  4333.6     339    4362  345.16
  4384.8  338.97  4391.9  334.87    4414  331.12  4519.7  325.01  4535.4  321.64
  4573.2  323.95  4634.7  320.53  4656.8  322.56  4790.2  319.73  4888.5  317.17
  4932.6  314.62  4978.4  315.48  4992.7  302.69  4995.4  302.19  4998.7  302.69
  5012.5  304.37  5027.2  315.48    5041  312.75  5237.9  321.86  5255.2  318.35
  5260.4  311.78  5279.4  312.26  5289.7  319.81  5341.6  326.92    5580  345.45
#Mann= 5 ,-1 , 0
  4182.2     .05       0  4519.7     .16       0  4790.2     .12       0
  4992.7     .07       0  4998.7     .12       0
Bank Sta=4888.5,5289.7
XS Rating Curve= 0 ,0
Exp/Cntr=0.3,0.1

Type RM Length L Ch R = 1 ,5265    ,442,442,442
BEGIN DESCRIPTION:
YARD BRANCH 9.0
END DESCRIPTION:
XS GIS Cut Line= 3
      3646799.59     10572460.19      3647499.61     10572510.19
      3647999.59      10572310.2
#Sta/Elev= 30
  4298.7  344.82  4358.9  341.68  4459.1  331.56  4609.5  320.05  4769.9  315.47
  4811.5   314.7  4860.1  313.08  4910.3  313.86  4920.3  311.22  4927.8  312.57
  4932.8  312.05  4940.4  314.25  4960.4  313.77    4995  301.61  4997.7  301.11
    5001  301.61  5003.2  301.61  5009.9  310.98  5015.3  310.73    5022  314.04
  5069.2  312.54  5162.1  315.76  5206.5  316.73  5284.6  322.49  5308.8  325.88
  5323.6  326.15  5362.7  330.96  5392.3  332.81  5494.6   343.8    5539  347.23
#Mann= 4 ,-1 , 0
  4298.7     .16       0  4811.5     .12       0    4995     .07       0
    5001     .12       0
Bank Sta=4769.9,5162.1
XS Rating Curve= 0 ,0
Exp/Cntr=0.3,0.1

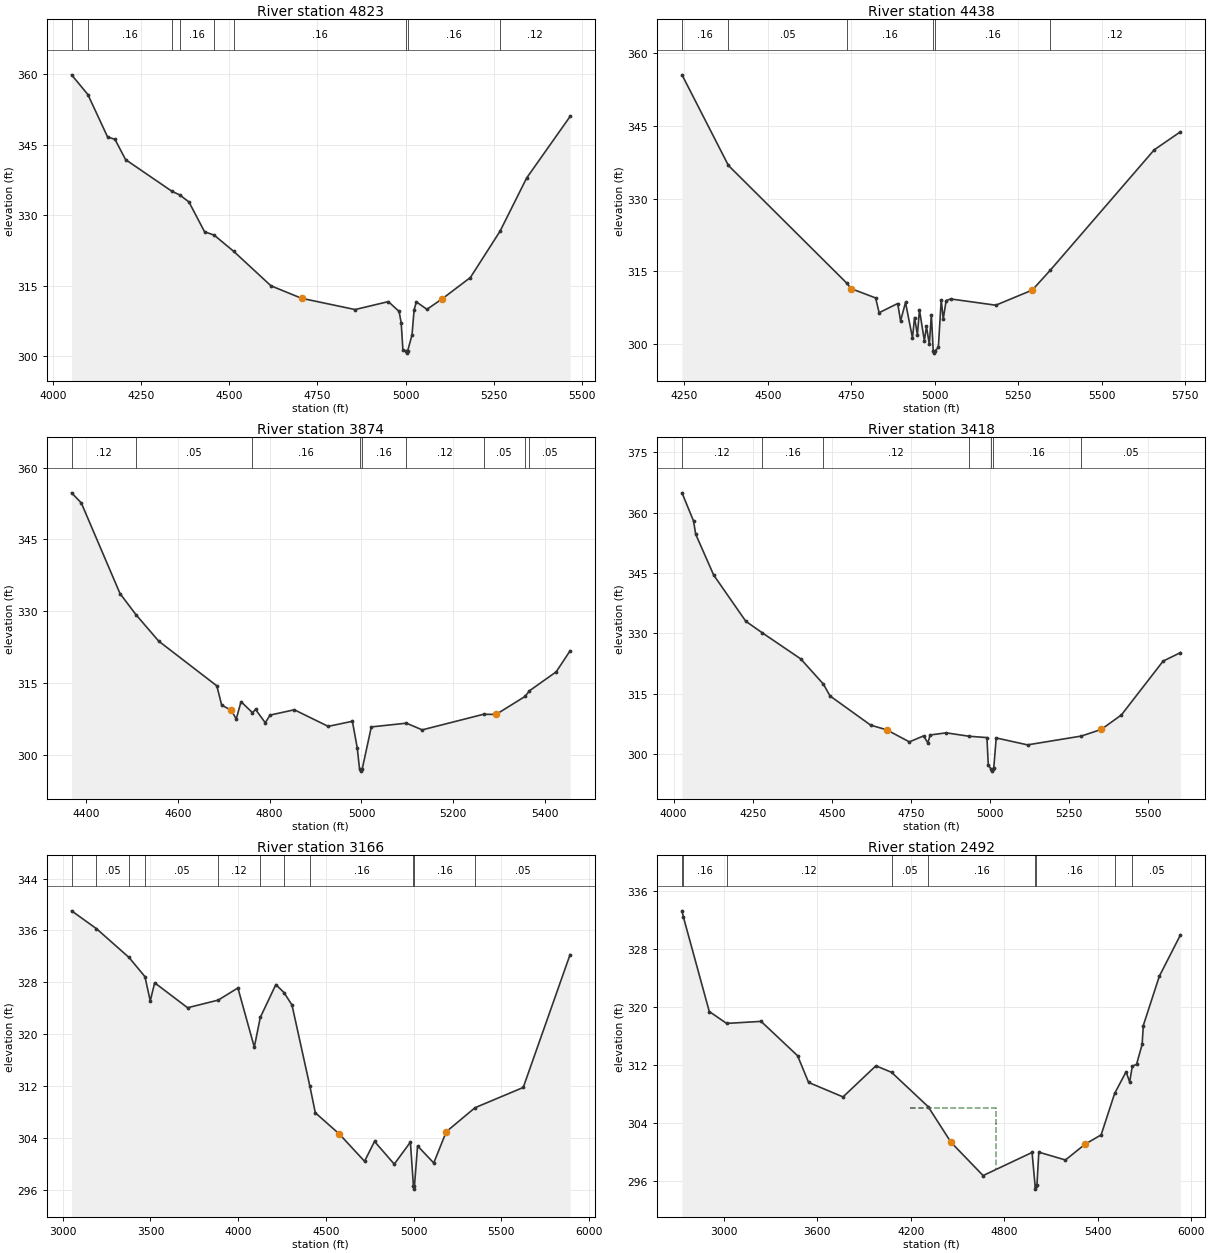
Type RM Length L Ch R = 1 ,4823    ,385,385,385
BEGIN DESCRIPTION:
YARD BRANCH 8.0
END DESCRIPTION:
XS GIS Cut Line= 3
      3646899.61     10573360.19      3647699.61     10572860.19
      3648099.61     10572610.19
#Sta/Elev= 30
  4052.1  359.84  4098.3  355.65  4154.1  346.65  4175.3   346.1  4205.4   341.8
  4337.4  335.04  4358.6  334.31  4385.2   332.8  4429.5  326.46  4456.9  325.73
  4512.2  322.29  4618.1  314.95  4704.8   312.3  4856.9   309.9  4951.3  311.59
  4981.9   309.5  4987.8  307.05  4992.6  301.38  5000.2  301.13  5002.9  300.63
  5006.2  301.13  5018.5  304.51  5024.4  309.83  5030.9  311.53  5060.9  309.95
  5103.4  312.14  5184.2  316.72  5268.2  326.55    5344   337.9  5467.2  350.98
#Mann= 9 ,-1 , 0
  4052.1     .05       0  4098.3     .16       0  4337.4     .05       0
  4358.6     .16       0  4456.9     .05       0  4512.2     .16       0
  5000.2     .07       0  5006.2     .16       0  5268.2     .12       0
Bank Sta=4704.8,5103.4
XS Rating Curve= 0 ,0
Exp/Cntr=0.3,0.1

Type RM Length L Ch R = 1 ,4438    ,564,564,564
BEGIN DESCRIPTION:
YARD BRANCH 7.0
END DESCRIPTION:
XS GIS Cut Line= 3
      3646999.64     10573510.18      3647599.61     10573310.19
      3648299.65     10572810.16
#Sta/Elev= 30
  4242.8  355.57  4381.8  336.85    4737  312.49  4748.7  311.43  4822.5  309.49
  4833.1  306.44  4888.7  308.34  4897.3  304.75  4912.1  308.55    4933  301.23
  4939.1  305.44  4947.7  301.92  4953.9  306.99  4968.6  300.65  4974.8  303.61
  4983.4  299.93  4989.5  306.02  4995.1  298.59  4997.9  298.09  5001.1  298.59
  5010.4  299.26    5019  309.09  5025.1  305.15  5033.8  308.95  5047.3  309.28
  5182.4  307.99  5291.8  311.12  5345.3  315.19  5656.8  340.08  5735.5  343.81
#Mann= 6 ,-1 , 0
  4242.8     .16       0  4381.8     .05       0    4737     .16       0
  4995.1     .07       0  5001.1     .16       0  5345.3     .12       0
Bank Sta=4748.7,5291.8
XS Rating Curve= 0 ,0
Exp/Cntr=0.3,0.1

Type RM Length L Ch R = 1 ,3874    ,456,456,456
BEGIN DESCRIPTION:
YARD BRANCH 6.0
END DESCRIPTION:
XS GIS Cut Line= 3
      3647049.64      10573560.2      3647649.61     10573760.19
      3648099.61     10573710.19
#Sta/Elev= 30
    4369  354.75  4390.1  352.64  4474.4  333.71  4508.9  329.32  4558.7  323.76
  4685.2  314.42  4695.7  310.39  4716.8   309.3  4727.4  307.48  4737.9  311.11
  4762.7  308.82  4769.5  309.49  4790.6  306.71  4801.1  308.31  4853.9  309.42
  4927.6  305.95  4980.3  307.02  4990.9  301.45  4995.8   297.1  4998.5   296.6
  5001.8   297.1  5021.5  305.84  5097.9  306.62  5132.2  305.22  5265.8  308.48
  5293.2  308.45  5356.2  312.21  5365.8  313.39    5424  317.35  5454.2  321.74
#Mann= 9 ,-1 , 0
    4369     .12       0  4508.9     .05       0  4762.7     .16       0
  4995.8     .07       0  5001.8     .16       0  5097.9     .12       0
  5265.8     .05       0  5356.2     .16       0  5365.8     .05       0
Bank Sta=4716.8,5293.2
XS Rating Curve= 0 ,0
Exp/Cntr=0.3,0.1

Type RM Length L Ch R = 1 ,3418    ,252,252,252
BEGIN DESCRIPTION:
YARD BRANCH 5.0
END DESCRIPTION:
XS GIS Cut Line= 3
      3646899.59     10573660.17      3647699.61     10574210.19
      3648249.61     10573960.19
#Sta/Elev= 30
  4026.3  364.97  4062.7  357.98  4069.6  354.69  4126.4  344.52  4227.9  333.03
  4280.2  330.15  4401.1   323.7    4473  317.42  4493.8  314.48  4622.3  307.21
  4673.1  306.04  4744.8  303.04  4789.5  304.53    4803   302.8  4810.4  304.76
  4861.2  305.29  4933.6  304.44  4989.7  304.11  4994.1  297.24  5002.9  296.27
  5005.7  295.77  5008.9  296.27  5011.4  296.66  5019.1  304.02    5118   302.3
    5288  304.49  5350.9  306.14  5414.6  309.74  5546.4  323.13  5601.3  325.24
#Mann= 7 ,-1 , 0
  4026.3     .12       0  4280.2     .16       0    4473     .12       0
  4933.6     .16       0  5002.9     .07       0  5008.9     .16       0
    5288     .05       0
Bank Sta=4673.1,5350.9
XS Rating Curve= 0 ,0
Exp/Cntr=0.3,0.1

Type RM Length L Ch R = 1 ,3166    ,674,674,674
BEGIN DESCRIPTION:
YARD BRANCH 4.0
END DESCRIPTION:
XS GIS Cut Line= 3
      3645919.19      10574651.9      3646107.97     10574803.45
      3648649.57      10574260.2
#Sta/Elev= 30
  3050.4  339.03  3192.1  336.28  3377.6  331.85  3468.5  328.89  3498.7  325.14
  3523.8  327.95  3711.5   324.1  3886.3  325.28  3998.2  327.15  4091.8  318.03
  4125.7   322.6  4214.5  327.67  4260.9  326.44  4306.5  324.52  4408.8  311.97
  4439.5  307.92  4576.7  304.64  4720.1  300.45  4776.9  303.51  4889.4  300.01
  4981.4   303.4  4998.6  296.66  5001.4  296.16  5004.6  296.66  5022.3  302.82
  5114.4  300.19    5186  305.01  5349.6   308.7  5624.5  311.82  5891.5  332.29
#Mann= 11 ,-1 , 0
  3050.4     .12       0  3192.1     .05       0  3377.6     .16       0
  3468.5     .05       0  3886.3     .12       0  4125.7     .16       0
  4260.9     .12       0  4408.8     .16       0  4998.6     .07       0
  5004.6     .16       0  5349.6     .05       0
Bank Sta=4576.7,5186
XS Rating Curve= 0 ,0
Exp/Cntr=0.3,0.1

Type RM Length L Ch R = 1 ,2492    ,383,383,383
BEGIN DESCRIPTION:
YARD BRANCH 3.0
END DESCRIPTION:
XS GIS Cut Line= 4
      3645891.42     10575735.26      3646064.44     10575626.69
      3647236.31     10575505.17      3648824.73     10574619.82
#Sta/Elev= 30
  2731.5  333.26  2740.1  332.44  2906.7  319.37    3018  317.73  3239.4  318.01
  3473.8  313.27  3544.2  309.59  3765.4  307.59  3976.5  311.88  4076.8  310.99
  4312.3  306.24  4459.2  301.32    4665  296.74  4979.3  299.93  5000.8  294.87
    5004  295.37  5010.7  295.45  5022.7  299.97  5193.8  298.89  5319.8  301.07
  5422.8  302.35  5509.6  308.07  5583.1  311.06    5606  309.64  5622.9  311.83
  5650.2  312.08  5686.1  314.84  5693.6  317.44  5796.5  324.24  5932.4  329.95
#Mann= 9 ,-1 , 0
  2731.5     .12       0  2740.1     .16       0    3018     .12       0
  4076.8     .05       0  4312.3     .16       0  5000.8     .07       0
    5004     .16       0  5509.6     .16       0  5622.9     .05       0
#XS Ineff= 1 ,-1
  4198.3 4747.16  306.08
Permanent Ineff=
       F
Bank Sta=4459.2,5319.8
XS Rating Curve= 0 ,0
Exp/Cntr=0.3,0.1