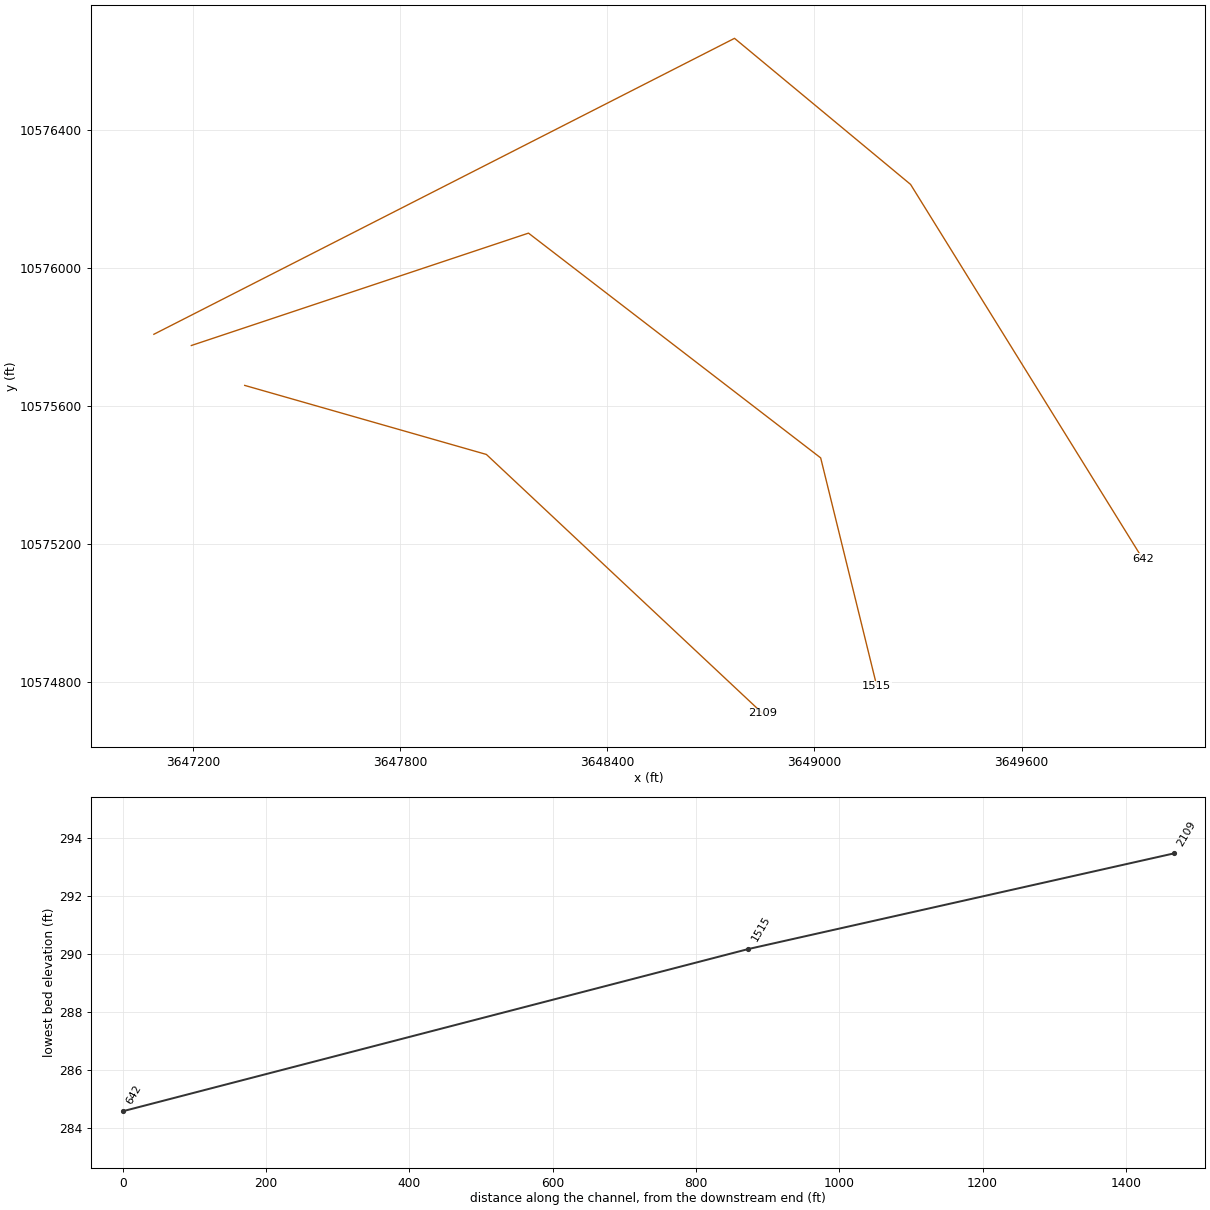
HEC-RAS study YARD BRANCH.prj: YARD BRANCH Base Level Engineering

--- YARD BRANCH.g01 (geometry) --- (continued)

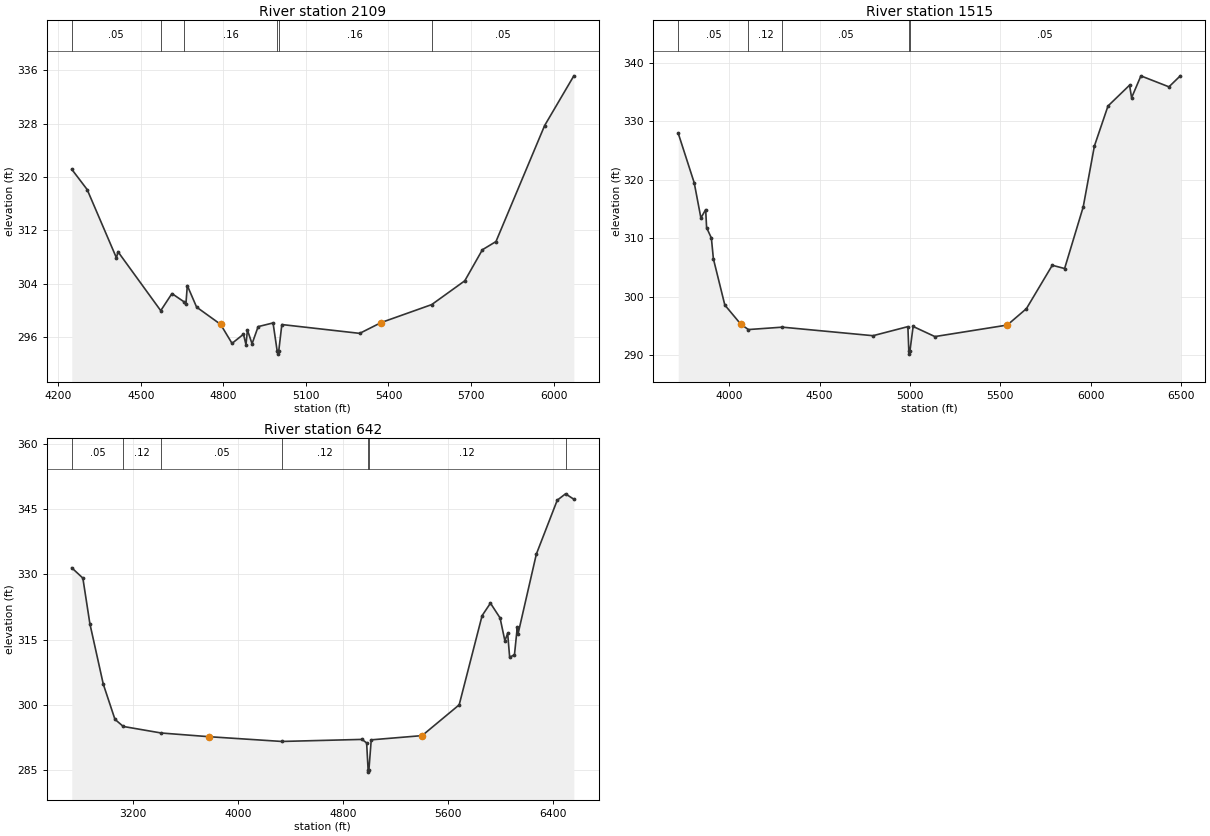
Type RM Length L Ch R = 1 ,2109    ,594,594,594
BEGIN DESCRIPTION:
YARD BRANCH 2.0
END DESCRIPTION:
XS GIS Cut Line= 3
      3647349.59     10575660.19      3648049.61     10575460.19
       3648849.6      10574710.2
#Sta/Elev= 30
  4249.1  321.14    4305  318.11  4411.6  307.86  4416.8  308.81  4572.4  299.97
  4613.1  302.53    4658  301.27  4663.8  300.91    4669  303.73  4702.8   300.5
  4789.9  297.92  4831.5  295.07  4873.1  296.44  4882.2  294.87  4887.4  297.08
  4904.3  295.01  4926.4  297.58  4980.6  298.13  4995.4  293.96  4998.1  293.46
  5001.4  293.96  5012.5  297.89  5295.4  296.57  5373.5  298.19  5557.2  300.88
  5677.3  304.44  5741.3  309.09  5790.7  310.32  5967.5  327.69  6073.7  335.14
#Mann= 6 ,-1 , 0
  4249.1     .05       0  4572.4     .12       0    4658     .16       0
  4995.4     .07       0  5001.4     .16       0  5557.2     .05       0
Bank Sta=4789.9,5373.5
XS Rating Curve= 0 ,0
Exp/Cntr=0.3,0.1

Type RM Length L Ch R = 1 ,1515    ,873,873,873
BEGIN DESCRIPTION:
Mapping XS 3023314e
END DESCRIPTION:
XS GIS Cut Line= 4
      3647194.98     10575775.75      3648171.57     10576101.28
      3649017.92     10575450.24      3649180.68     10574788.36
#Sta/Elev= 30
  3717.3  327.92  3805.8  319.45  3842.7  313.45  3869.1  314.87  3874.3  311.78
  3900.7  310.02  3911.9  306.46  3975.2  298.56  4064.1  295.27  4105.6  294.37
  4293.6  294.78  4795.3  293.32  4988.3  294.87  4993.5  290.67  4996.2  290.17
  4999.5  290.67  5017.3   294.9  5137.8  293.17  5538.4  295.14  5644.3  297.94
  5787.5  305.36  5855.7   304.8  5958.7  315.33  6020.5  325.73  6095.8  332.58
  6215.2  336.14  6226.5     334    6278  337.73  6433.2  335.86  6496.1  337.74
#Mann= 5 ,-1 , 0
  3717.3     .05       0  4105.6     .12       0  4293.6     .05       0
  4993.5     .03       0  4999.5     .05       0
Bank Sta=4064.1,5538.4
XS Rating Curve= 0 ,0
Exp/Cntr=0.3,0.1

Type RM Length L Ch R = 1 ,642     ,0,0,0
BEGIN DESCRIPTION:
YARD BRANCH 1.0
END DESCRIPTION:
XS GIS Cut Line= 4
      3647086.45     10575808.29      3648768.36     10576665.52
      3649278.34     10576242.34      3649951.06     10575157.31
#Sta/Elev= 30
  2733.2  331.48  2817.7  329.12  2871.4  318.63  2973.3  304.79  3062.3  296.71
  3125.9  295.07  3414.8  293.57  3779.2  292.72  4334.5  291.63  4945.6   292.1
  4980.8  291.29  4992.1  285.09  4994.9  284.59  4998.1  285.09  5015.9     292
  5403.7  292.97  5686.2  300.03  5860.9   320.5  5924.6  323.37  5997.9  319.98
  6034.5  314.75  6055.8  316.42  6071.1  310.93  6107.8  311.55    6129   317.8
  6134.9   316.3  6274.5  334.63  6433.8     347    6497  348.46  6560.3  347.22
#Mann= 7 ,-1 , 0
  2733.2     .05       0  3125.9     .12       0  3414.8     .05       0
  4334.5     .12       0  4992.1     .07       0  4998.1     .12       0
    6497     .05       0
Bank Sta=3779.2,5403.7
XS Rating Curve= 0 ,0
Exp/Cntr=0.3,0.1

Chan Stop Cuts=-1
Use User Specified Reach Order=0
Composite Channel Slope=5